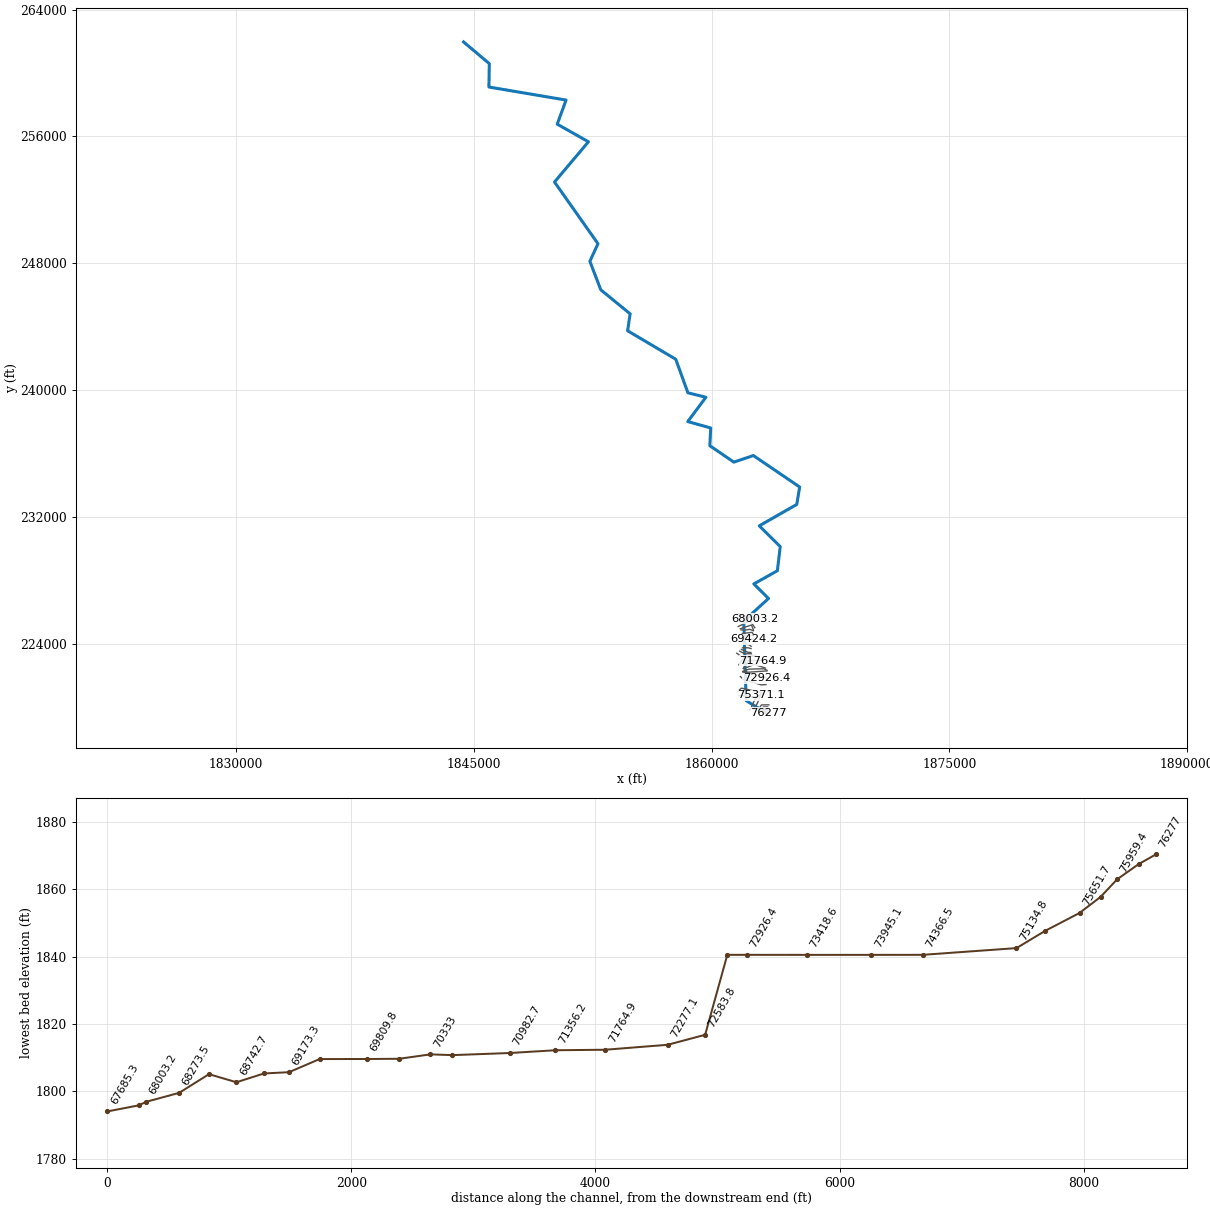
--- TETERCK.prj (project) ---

Proj Title=TETERCK
Current Plan=p01
Default Exp/Contr=0,0
English Units
Geom File=g01
Flow File=f01
Plan File=p01
BEGIN DESCRIPTION:
END DESCRIPTION:
DSS Export Rating Curves= 0
DSS Export Rating Curve Sorted= 0
DSS Export Volume Flow Curves= 0
DXF OffsetX= 0
DXF OffsetY= 0
DXF ScaleX= 0
DXF ScaleY= 0

--- TETERCK.p01 (plan) ---

Plan Title=Floodplain
Program Version=4.00
Geom File=g01
Flow File=f01
K Sum by GR=0
Std Step Tol=0.01
Critical Tol=0.01
Num of Std Step Trials=20
Max Error Tol=0.3
Flow Tol Ratio=0.001
Split Flow NTrial=30
Split Flow Tol=0.02
Split Flow Ratio=0.02
Log Output Level=0
Friction Slope Method=1
Unsteady Friction Slope Method=2
Unsteady Bridges Friction Slope Method=1
Global Log Level=0
CheckData=False
Run HTab=0
Run UNet=0
Run PostProcess=0
UNET Theta=0
UNET Theta Warmup=0
UNET ZTol=0
UNET ZSATol=0
UNET MxIter=0
UNET MaxInSteps=0
UNET DtIC=0
UNET DtMin=0
UNET MaxCRTS=0
UNET WFStab=0
UNET SFStab=0
UNET WFX=0
UNET SFX=0
UNET DSS MLevel=0
UNET DZMax Abort=0
UNET Convert EG Bridges=0
UNET Use Existing IB Tables=0
UNET Froude Limit=0
UNET Froude Power=0
Write IC File=0
Echo Input=False
Echo Output=False
Write Detailed=0

--- TETERCK.f01 (steady flow) ---

Flow Title=NFF Regression Equation
Program Version=5.03
Number of Profiles= 1
Profile Names=P100yr
River Rch & RM=TETERCK,Main            ,76277
512.9038
River Rch & RM=TETERCK,Main            ,75651.7
563.4895
River Rch & RM=TETERCK,Main            ,72926.4
624.4533
River Rch & RM=TETERCK,Main            ,70076.8
679.3286
River Rch & RM=TETERCK,Main            ,69173.3
754.7789
River Rch & RM=TETERCK,Main            ,68968.8
1254.848
River Rch & RM=TETERCK,Main            ,67297.8
1281.493
River Rch & RM=TETERCK,Main            ,65194.5
1406.499
River Rch & RM=TETERCK,Main            ,59494.3
 1471.44
River Rch & RM=TETERCK,Main            ,59010.6
1668.141
River Rch & RM=TETERCK,Main            ,55132.9
1705.526
River Rch & RM=TETERCK,Main            ,48874.1
1894.932
River Rch & RM=TETERCK,Main            ,44451
2082.441
River Rch & RM=TETERCK,Main            ,35423.9
2672.142
River Rch & RM=TETERCK,Main            ,35423.9
2241.679
River Rch & RM=TETERCK,Main            ,32432
2701.802
River Rch & RM=TETERCK,Main            ,31716.6
3257.908
River Rch & RM=TETERCK,Main            ,28407.4
 3512.56
River Rch & RM=TETERCK,Main            ,21717.9
3898.659
River Rch & RM=TETERCK,Main            ,21430.6
5498.681
River Rch & RM=TETERCK,Main            ,10077.6
5772.362
River Rch & RM=TETERCK,Main            ,9206.8
6646.167
River Rch & RM=TETERCK,Main            ,358.4
 7096.87
Boundary for River Rch & Prof#=TETERCK,Main            , 1
Up Type= 0
Dn Type= 3
Dn Slope=0.01878
DSS Import GetInterval= 0
DSS Import GetPeak= 0
DSS Import FillOption= 0

--- TETERCK.g01 (geometry) ---

Geom Title=USGS 10m DEM
Program Version=4.10

River Reach=TETERCK         ,Main
Reach XY= 30
     1863509.611      219589.378     1862183.301      220395.996
     1862035.039      225416.589     1863594.696      226843.506
     1862668.516      227760.338     1864155.278      228595.566
      1864334.76      230117.232     1863012.806      231426.702
     1865379.304      232778.941     1865560.448      233877.875
     1862639.446      235862.523     1861409.592       235446.69
     1859893.527      236481.831     1859949.816      237602.058
     1858502.119      238005.897     1859645.681      239540.862
      1858509.22      239820.339      1857744.03      241938.326
      1854705.68      243733.405     1854864.476      244803.223
     1853014.294      246316.282     1852324.391      248119.534
       1852835.4      249227.639     1850093.072       253120.84
     1852234.312      255659.257     1850265.517      256770.527
     1850821.638      258290.894     1845955.216      259112.919
     1845978.639      260590.086     1844354.719       261960.34

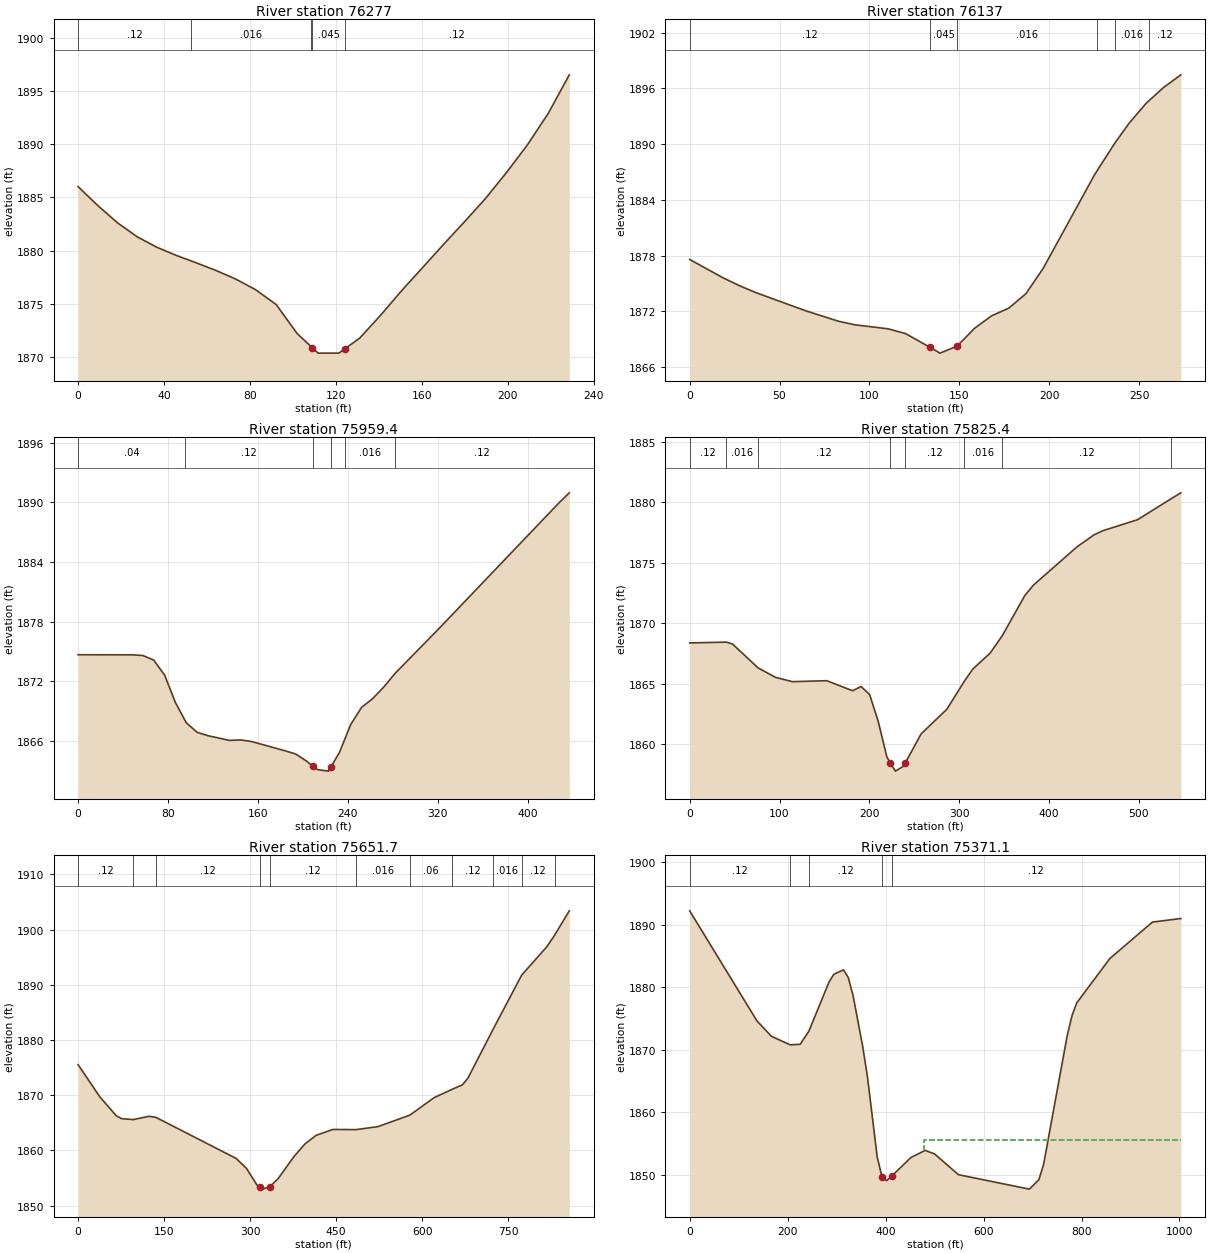
Type RM Length L Ch R = 1 ,76277   ,144.8,140,142.7
XS GIS Cut Line= 3
     1863466.953      219509.539     1863472.269      219591.792
      1863609.53      219642.007
#Sta/Elev= 29
       0 1886.02     9.2 1884.23    18.3 1882.62    27.5  1881.3    36.6 1880.32
    45.8 1879.54   52.581879.031      55 1878.85    64.1 1878.14    73.3 1877.33
    82.4 1876.35    92.2 1874.93   101.9 1872.21  108.611870.944     109 1870.87
   111.7 1870.36   121.4 1870.36   124.1 1870.76   131.1 1871.78   140.9 1873.95
   150.6 1876.24   160.4 1878.42   170.1 1880.59   179.9 1882.73   189.6  1884.9
   199.4 1887.35   209.1 1889.94   218.8  1892.9   228.6 1896.53
#Mann= 5 ,-1 , 0
       0     .12       0   52.58    .016       0  108.61     .12       0
     109    .045       0   124.1     .12       0
Bank Sta=109,124.1
XS Rating Curve= 0 ,0
Exp/Cntr=0.3,0.1

Type RM Length L Ch R = 1 ,76137   ,165.9,177.6,189.3
XS GIS Cut Line= 3
      1863380.73       219624.32     1863418.378      219717.981
     1863575.399      219788.687
#Sta/Elev= 25
       0 1877.59    18.4 1875.63    27.5 1874.78    36.7 1874.03    64.2 1872.09
    82.6 1870.95    91.8 1870.56   110.5 1870.12   120.1 1869.61   133.6 1868.14
   139.2 1867.51   148.7 1868.25   158.4 1870.17   167.9 1871.52   177.5 1872.35
     187  1873.9   196.6 1876.62   225.3 1886.73  226.791887.186  236.321890.054
   244.4 1892.24     254 1894.41  255.361894.648   263.6 1896.09   273.2 1897.45
#Mann= 6 ,-1 , 0
       0     .12       0   133.6    .045       0   148.7    .016       0
  226.79     .12       0  236.32    .016       0  255.36     .12       0
Bank Sta=133.6,148.7
XS Rating Curve= 0 ,0
Exp/Cntr=0.3,0.1

Type RM Length L Ch R = 1 ,75959.4 ,131.8,134,136.3
XS GIS Cut Line= 4
     1863292.578      219674.824     1863272.376       219807.97
     1863374.302      219899.795     1863534.996      219861.228
#Sta/Elev= 30
       0 1874.68    48.1 1874.67    57.7  1874.6    67.3 1874.14      77 1872.63
    86.6 1869.87   94.831868.138    96.2 1867.85   105.8 1866.88   115.4 1866.54
   134.7 1866.06   144.5 1866.11   154.3 1865.95   183.7 1865.03   193.5  1864.7
   203.3 1863.98  208.97 1863.47   213.1 1863.12   222.9 1862.97  225.06  1863.4
   232.7 1864.88   237.21866.147   242.5 1867.64   252.3 1869.39   262.1 1870.26
   271.9 1871.42  282.241872.827   320.5 1877.24   427.4  1889.9   437.1 1890.97
#Mann= 6 ,-1 , 0
       0     .04       0   94.83     .12       0  208.97    .045       0
  225.06     .12       0   237.2    .016       0  282.24     .12       0
Bank Sta=208.97,225.06
XS Rating Curve= 0 ,0
Exp/Cntr=0.3,0.1

Type RM Length L Ch R = 1 ,75825.4 ,167.1,173.6,179.6
XS GIS Cut Line= 3
     1863081.323      219797.611     1863282.061      220001.604
     1863542.477      220001.604
#Sta/Elev= 30
       0 1868.39   40.911868.457    47.7  1868.3   76.151866.329    95.4 1865.55
   114.5 1865.19   152.6 1865.27   181.3 1864.44   190.8 1864.79   200.3 1864.12
   209.9 1861.89   219.4 1858.99  223.31 1858.46     229  1857.8   238.5 1858.23
  240.05 1858.49   257.6 1860.88   286.2 1862.91  305.161865.169   315.1 1866.23
   334.4 1867.55  347.981868.997     373 1872.31   382.6 1873.17   430.9 1876.32
   450.2 1877.33   459.8 1877.66   498.4 1878.57  536.081880.316   546.6 1880.79
#Mann= 8 ,-1 , 0
       0     .12       0   40.91    .016       0   76.15     .12       0
  223.31    .045       0  240.05     .12       0  305.16    .016       0
  347.98     .12       0  536.08    .016       0
Bank Sta=223.31,240.05
XS Rating Curve= 0 ,0
Exp/Cntr=0.3,0.1

Type RM Length L Ch R = 1 ,75651.7 ,278.4,280.7,283.2
XS GIS Cut Line= 4
      1862972.31      219786.109     1863080.817      220029.165
     1863149.176      220126.821     1863620.096      220134.416
#Sta/Elev= 30
       0 1875.54      38 1869.69    66.5 1866.28      76 1865.75   96.211865.586
   123.6 1866.18  135.391866.004   275.4 1858.56   293.7 1856.74     312 1853.71
  317.16  1853.3   321.2 1852.99  333.87  1853.4   348.7 1854.88   376.2 1858.87
   395.2 1861.14   414.8 1862.72   444.2  1863.8  484.511863.768   522.8 1864.31
  578.481866.399   620.9 1869.57  652.591871.093   669.9 1871.87   679.7  1873.1
   723.71881.972  773.421891.761   817.1 1896.88  830.741898.972   856.4  1903.4
#Mann= 11 ,-1 , 0
       0     .12       0   96.21    .016       0  135.39     .12       0
  317.16    .045       0  333.87     .12       0  484.51    .016       0
  578.48     .06       0  652.59     .12       0   723.7    .016       0
  773.42     .12       0  830.74    .016       0
Bank Sta=317.16,333.87
XS Rating Curve= 0 ,0
Exp/Cntr=0.3,0.1

Type RM Length L Ch R = 1 ,75371.1 ,230.7,236.2,241.7
XS GIS Cut Line= 3
     1862654.384      219842.533     1862908.291      220262.455
     1863090.582       220740.97
#Sta/Elev= 30
       0 1892.23   137.4 1874.62   166.8 1872.16  205.261870.785   225.7 1870.88
  243.341872.958   284.6 1880.85   294.4 1882.08   314.1 1882.79   323.9 1881.53
   333.7 1878.64   353.3 1870.52   363.1  1865.6   382.8  1852.9   392.6 1849.65
   402.4 1849.06   412.2 1849.76   451.5 1852.75   480.9  1853.9   500.4 1853.31
   548.7 1850.01   693.6  1847.7   712.9  1849.2   722.6 1851.66   770.9  1872.3
   780.6 1875.46   790.2 1877.49   857.9  1884.6   944.8 1890.43  1002.8    1891
#Mann= 5 ,-1 , 0
       0     .12       0  205.26    .016       0  243.34     .12       0
   392.6    .045       0   412.2     .12       0
#XS Ineff= 2 , 0
                          478.02         1855.51
Permanent Ineff=
       F       F
Bank Sta=392.6,412.2
XS Rating Curve= 0 ,0
Exp/Cntr=0.3,0.1

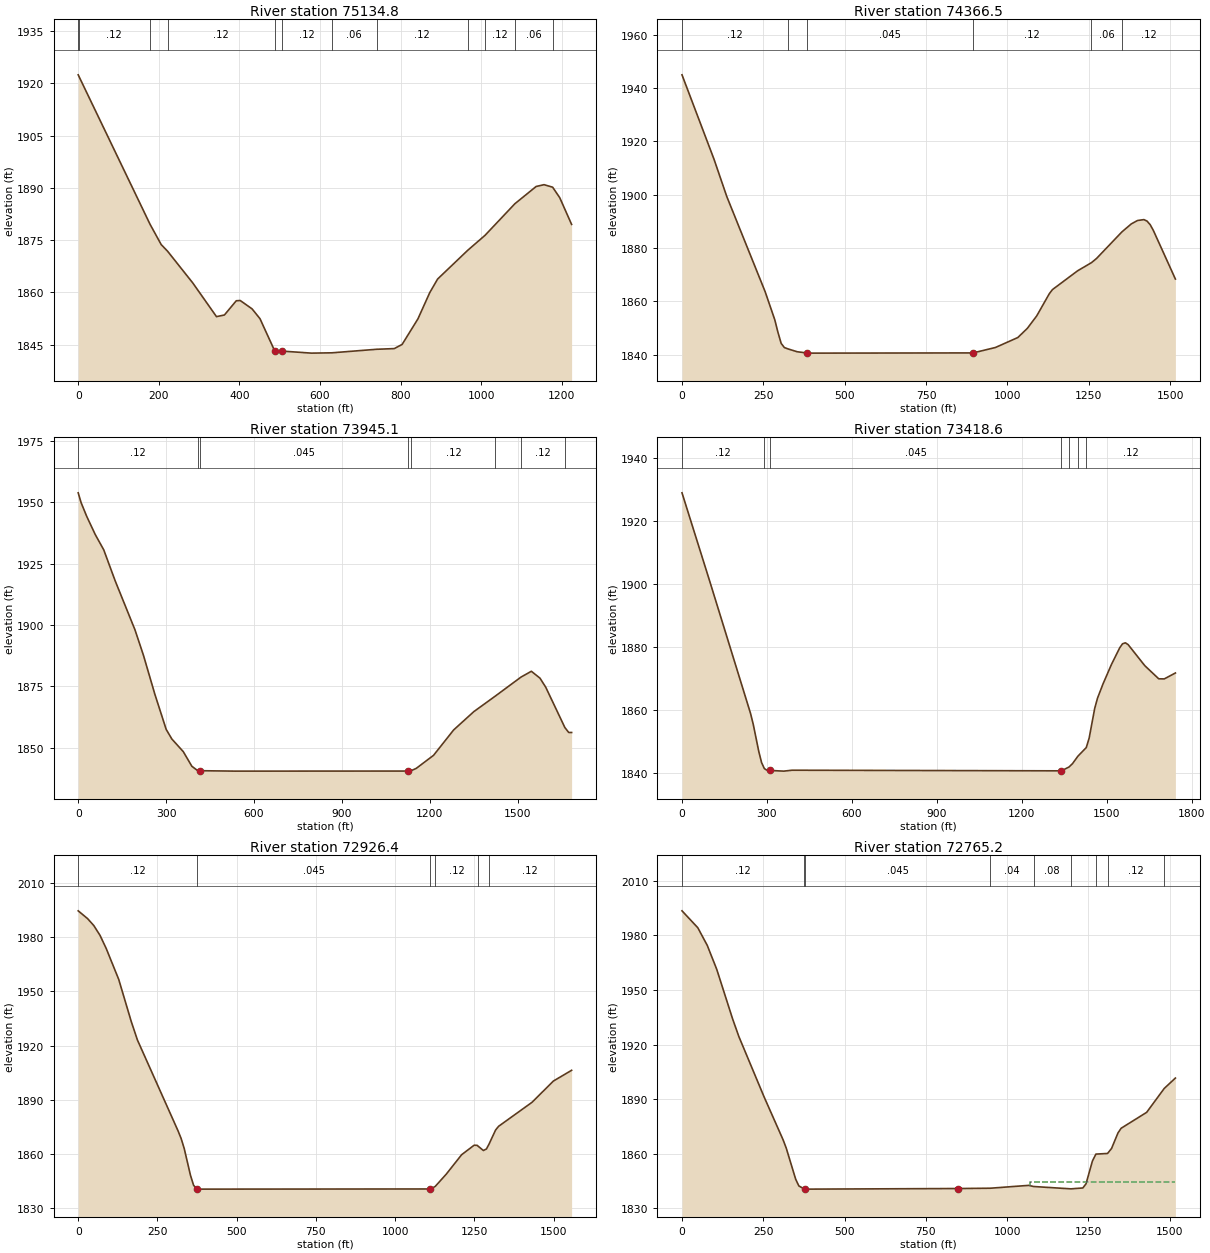
Type RM Length L Ch R = 1 ,75134.8 ,819.4,768.3,716.4
XS GIS Cut Line= 3
     1862454.732      219826.257      1862736.85      220494.659
     1863135.287      220794.573
#Sta/Elev= 30
       0 1922.44    1.291922.117  178.041879.593   205.9 1873.72  221.721871.814
   284.3  1862.7   343.1 1853.03   362.8 1853.51   392.2 1857.59     402 1857.66
   431.4 1855.26     451 1852.45  487.87 1843.12  505.41 1843.15   578.4 1842.56
  629.351842.648  740.571843.666   784.2 1843.86   803.7 1845.06   842.8 1852.37
   872.2 1859.91   891.7 1863.82  966.531872.081 1009.19 1876.35 1083.441885.435
  1136.2 1890.39  1155.8 1890.91 1177.151890.188  1194.9 1887.15  1224.2  1879.5
#Mann= 12 ,-1 , 0
       0    .016       0    1.29     .12       0  178.04    .016       0
  221.72     .12       0  487.87    .045       0  505.41     .12       0
  629.35     .06       0  740.57     .12       0  966.53     .06       0
 1009.19     .12       0 1083.44     .06       0 1177.15     .12       0
Bank Sta=487.87,505.41
XS Rating Curve= 0 ,0
Exp/Cntr=0.3,0.1

Type RM Length L Ch R = 1 ,74366.5 ,425.2,421.4,417.5
XS GIS Cut Line= 3
     1861701.693      220737.715     1862717.318      220622.698
     1863163.933      220833.635
#Sta/Elev= 30
       0 1945.01    98.3 1913.35   137.6 1899.34   255.5 1863.61     285 1853.11
   294.8 1848.37   304.7 1844.22   314.5 1842.66  325.291842.163   353.8 1841.08
   383.3 1840.62     403 1840.56   894.4 1840.64   963.2 1842.68  1031.8 1846.41
  1060.9 1849.83  1089.9 1854.53  1128.6 1862.86  1138.3 1864.41  1215.8 1871.48
 1258.09 1874.51  1273.9 1876.11 1351.521886.044  1380.4 1889.05  1399.8 1890.34
  1419.2 1890.67  1428.9 1890.11  1438.6 1888.75  1448.2 1886.63    1516 1868.36
#Mann= 6 ,-1 , 0
       0     .12       0  325.29     .04       0   383.3    .045       0
   894.4     .12       0 1258.09     .06       0 1351.52     .12       0
Bank Sta=383.3,894.4
XS Rating Curve= 0 ,0
Exp/Cntr=0.3,0.1

Type RM Length L Ch R = 1 ,73945.1 ,529.5,526.5,523.5
XS GIS Cut Line= 3
      1861624.87      220953.427     1861885.287      221185.198
     1863189.975      220901.343
#Sta/Elev= 30
       0 1953.76     9.7 1949.82      29 1944.19    58.1  1936.8    87.2 1930.56
   125.9 1918.04   193.7 1898.04   222.7 1887.66   261.5 1871.86   300.2 1857.54
   319.6 1853.61   358.4  1848.5   387.9 1842.52  407.481840.761   417.3 1840.72
   535.2 1840.55  1124.2 1840.58 1137.381840.784  1153.7 1841.68  1212.6 1846.97
  1281.3 1857.31    1350 1864.74 1423.411871.074 1510.851878.781  1546.4 1881.17
  1575.8 1878.38  1595.5 1874.69 1660.861858.283    1674 1856.27  1683.8 1856.26
#Mann= 8 ,-1 , 0
       0     .12       0  407.48     .04       0   417.3    .045       0
  1124.2     .04       0 1137.38     .12       0 1423.41     .06       0
 1510.85     .12       0 1660.86    .016       0
Bank Sta=417.3,1124.2
XS Rating Curve= 0 ,0
Exp/Cntr=0.3,0.1

Type RM Length L Ch R = 1 ,73418.6 ,490,492.3,494.5
XS GIS Cut Line= 4
     1861822.787      221916.968     1862010.287      221734.677
     1863145.704      221390.927     1863439.975      221409.156
#Sta/Elev= 30
       0 1928.84    96.8 1901.12   242.1 1858.85   251.8 1855.33   271.3 1846.73
   281.1 1843.25  288.451841.825   290.9 1841.35   300.7  1840.8   310.5 1840.76
   359.6 1840.55     389 1840.84    1340 1840.64 1366.771841.857  1379.2 1842.92
 1398.321845.295 1427.841848.028    1438 1851.02  1457.6 1860.45  1467.5 1863.69
  1487.1 1868.25  1516.6 1874.36  1546.1  1879.7  1555.9 1880.94  1565.8 1881.26
  1575.6 1880.69  1634.6    1874  1683.7 1869.84  1703.3 1869.81  1742.6 1871.68
#Mann= 7 ,-1 , 0
       0     .12       0  288.45     .04       0   310.5    .045       0
    1340     .04       0 1366.77     .12       0 1398.32    .016       0
 1427.84     .12       0
Bank Sta=310.5,1340
XS Rating Curve= 0 ,0
Exp/Cntr=0.3,0.1

Type RM Length L Ch R = 1 ,72926.4 ,149.4,161.1,172.8
XS GIS Cut Line= 3
     1861966.016      222219.052     1863200.391      221924.781
     1863463.412      221807.593
#Sta/Elev= 30
       0  1994.6    29.5  1990.3    49.2 1986.45    68.9 1981.01    88.5  1973.7
   127.9 1956.62   167.2 1933.43   186.9  1923.1   314.8 1872.91   324.6 1868.68
   334.5 1863.05   354.1 1848.32     364 1842.73   373.8 1840.72   383.6 1840.56
  1111.6 1840.65 1126.441842.041  1160.8 1848.73    1210 1859.63  1249.3 1864.86
  1259.1 1864.78 1262.391864.252  1278.6 1861.94  1288.2  1862.8 1296.391865.487
    1317 1873.26  1326.6 1875.34  1432.1 1888.63  1499.3 1900.37  1556.9 1906.33
#Mann= 6 ,-1 , 0
       0     .12       0   373.8    .045       0  1111.6     .04       0
 1126.44     .12       0 1262.39    .016       0 1296.39     .12       0
Bank Sta=373.8,1111.6
XS Rating Curve= 0 ,0
Exp/Cntr=0.3,0.1

Type RM Length L Ch R = 1 ,72765.2 ,183,181.5,179.7
XS GIS Cut Line= 3
     1861981.641      222232.073     1862348.829       222193.01
     1863494.662      222271.135
#Sta/Elev= 30
       0 1993.44    48.6 1984.16    77.7 1974.46   106.9 1961.28   155.5 1934.17
   174.9 1924.38   252.6  1891.2     311 1867.65   320.7 1863.08   349.8 1845.95
   359.5 1842.31  376.611840.639   379.1 1840.57   388.9 1840.56   850.2 1840.89
   948.4 1841.06  1066.2 1842.62 1081.691841.996 1196.431840.711  1233.1  1841.2
  1242.9 1843.51  1262.5 1855.97 1273.251859.801 1309.061860.142  1321.4 1862.89
  1341.1  1871.4  1350.9    1874  1429.4 1882.74 1483.361895.846  1517.8 1901.57
#Mann= 9 ,-1 , 0
       0     .12       0  376.61     .04       0   379.1    .045       0
   948.4     .04       0 1081.69     .08       0 1196.43     .12       0
 1273.25    .016       0 1309.06     .12       0 1483.36     .06       0
#XS Ineff= 2 , 0
                         1071.62         1844.59
Permanent Ineff=
       F       F
Bank Sta=379.1,850.2
XS Rating Curve= 0 ,0
Exp/Cntr=0.3,0.1

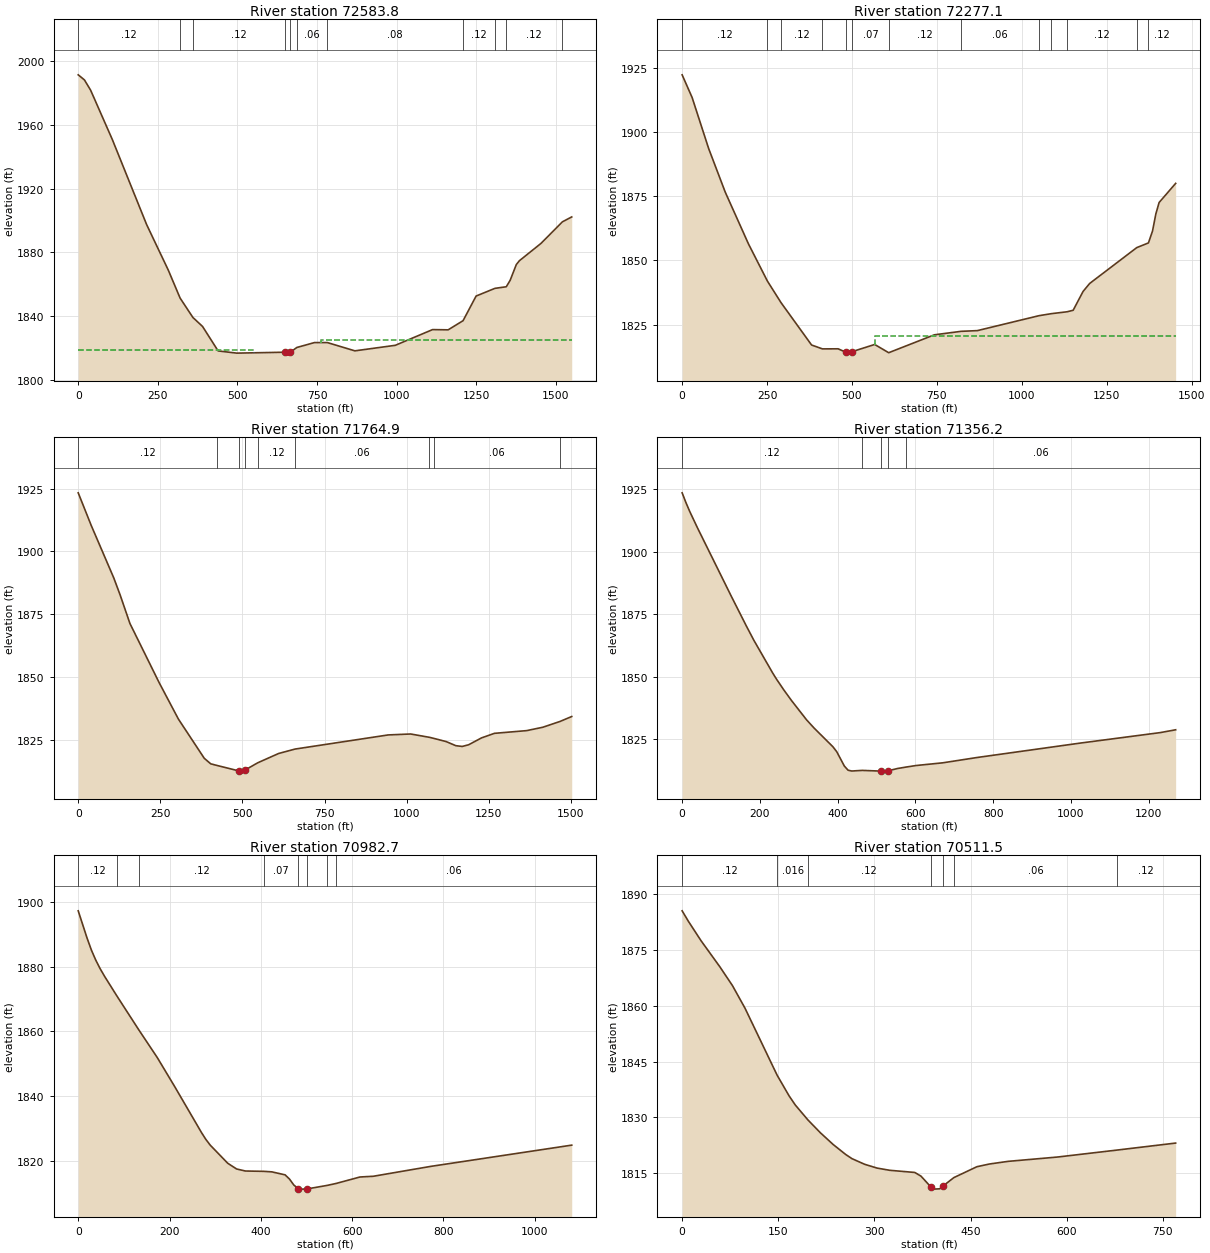
Type RM Length L Ch R = 1 ,72583.8 ,292.2,306.7,316.9
XS GIS Cut Line= 4
     1861994.662      222252.906      1862361.85      222385.718
     1863288.933      222409.156      1863499.87      222312.802
#Sta/Elev= 30
       0 1991.42    19.5 1988.24      39 1981.77   107.4  1950.7   214.8 1897.49
   283.1 1868.81  319.861851.397  360.221839.181   390.5 1833.56   439.3 1818.22
   497.8 1816.83  650.16  1817.4  666.45 1817.43   686.41820.362   741.9 1823.45
  782.451823.451   868.8 1818.26   995.7 1821.73  1112.8 1831.59  1161.7 1831.44
 1208.581837.183  1249.5 1852.64 1308.751857.476 1344.261858.462  1356.5 1862.54
  1375.8 1872.39  1385.5 1874.81  1453.1 1885.63 1520.451899.191  1549.8 1902.28
#Mann= 11 ,-1 , 0
       0     .12       0  319.86     .06       0  360.22     .12       0
  650.16    .045       0  666.45     .12       0   686.4     .06       0
  782.45     .08       0 1208.58     .12       0 1308.75    .016       0
 1344.26     .12       0 1520.45     .06       0
#XS Ineff= 2 , 0
          552.89 1818.97  763.38          1824.9
Permanent Ineff=
       F       F
Bank Sta=650.16,666.45
XS Rating Curve= 0 ,0
Exp/Cntr=0.3,0.1

Type RM Length L Ch R = 1 ,72277.1 ,433.9,512.2,438.5
XS GIS Cut Line= 3
     1862044.141      222414.364     1862702.995      222687.802
     1863403.516      222450.823
#Sta/Elev= 30
       0 1922.23    29.3 1913.43    78.2 1893.48     127 1876.52   195.4 1856.36
  250.921841.946  291.111833.525   381.1 1817.02  413.091815.511   459.3 1815.54
     482 1814.21   488.6 1813.86   500.2 1814.42   566.8 1817.23  608.151814.024
   742.5 1820.99  821.551822.353     869 1822.62 1050.491828.436  1086.41829.215
  1133.41829.965  1151.2 1830.55  1180.4 1837.89  1199.9    1841 1338.461854.952
 1372.781856.773  1384.8  1861.4  1394.5    1868  1404.2 1872.51  1452.9 1879.96
#Mann= 13 ,-1 , 0
       0     .12       0  250.92     .06       0  291.11     .12       0
  413.09     .07       0     482    .045       0   500.2     .07       0
  608.15     .12       0  821.55     .06       0 1050.49     .12       0
  1086.4     .06       0  1133.4     .12       0 1338.46    .016       0
 1372.78     .12       0
#XS Ineff= 2 , 0
                          568.01         1820.57
Permanent Ineff=
       F       F
Bank Sta=482,500.2
XS Rating Curve= 0 ,0
Exp/Cntr=0.3,0.1

Type RM Length L Ch R = 1 ,71764.9 ,404.1,408.7,319.2
XS GIS Cut Line= 3
     1861998.361      222428.828     1862335.854      222925.309
       1863238.2      222927.271
#Sta/Elev= 30
       0 1923.37    39.4 1910.43   108.3 1889.43   127.9 1882.56   157.5 1871.26
     246 1847.79   305.1 1833.14   383.8 1817.51   403.5  1815.3  423.511814.622
   488.1 1812.51   492.1 1812.39   506.7 1812.73  546.75 1815.72   610.1 1819.42
  660.241821.186   943.6 1826.82  1012.3  1827.2 1069.311825.875 1084.671825.385
  1120.2 1824.18  1149.6 1822.54  1169.2 1822.23  1188.8  1822.9    1228 1825.64
  1267.3 1827.46  1365.4 1828.54  1414.4 1829.88 1466.731832.183  1502.7 1834.17
#Mann= 9 ,-1 , 0
       0     .12       0  423.51     .07       0   488.1    .045       0
   506.7     .07       0  546.75     .12       0  660.24     .06       0
 1069.31     .12       0 1084.67     .06       0 1466.73     .12       0
Bank Sta=488.1,506.7
XS Rating Curve= 0 ,0
Exp/Cntr=0.3,0.1

Type RM Length L Ch R = 1 ,71356.2 ,379.5,373.6,214.2
XS GIS Cut Line= 4
     1861722.753      222656.693     1861939.607      222978.273
     1862237.773      223143.049     1862770.129      223237.091
#Sta/Elev= 30
       0 1923.59     9.7  1919.7    19.4 1916.18    38.8 1909.78   126.1 1882.31
   164.8 1870.41   184.2 1864.66   232.7 1851.54   242.4 1849.11   261.8 1844.66
   281.2  1840.5     320 1832.76   339.4 1829.46   387.9 1821.96   397.6    1820
   417.1 1814.28   426.8  1812.6   436.5 1812.28  462.631812.534   510.9 1812.25
   514.4 1812.24   529.7 1812.37   553.3 1813.27  576.121813.873     602 1814.49
   670.1 1815.56     758 1817.68  1023.4 1823.45  1229.8 1827.66  1269.1 1828.78
#Mann= 5 ,-1 , 0
       0     .12       0  462.63     .07       0   510.9    .045       0
   529.7     .07       0  576.12     .06       0
Bank Sta=510.9,529.7
XS Rating Curve= 0 ,0
Exp/Cntr=0.3,0.1

Type RM Length L Ch R = 1 ,70982.7 ,416.9,471.2,398.3
XS GIS Cut Line= 4
     1861590.375        223390.2     1861904.298      223166.588
     1862251.505      223188.166     1862594.348      223245.771
#Sta/Elev= 30
       0 1897.15    19.3 1888.79    28.9 1885.05    38.5 1881.95    48.2 1879.28
    57.8 1876.96   85.191870.822  133.431860.332   173.4  1851.9     212 1842.85
   269.8  1828.9   279.4 1826.78   289.1 1824.98   327.6 1819.38   346.9 1817.63
   366.2    1817  406.671816.896   424.1 1816.74   453.1 1815.82   462.7 1814.54
   472.4 1812.66     482  1811.6   491.7 1811.42   501.4 1811.49  544.871812.556
  564.911813.168   617.3 1815.16   646.3 1815.38   771.9 1818.42    1081 1824.97
#Mann= 8 ,-1 , 0
       0     .12       0   85.19    .016       0  133.43     .12       0
  406.67     .07       0     482    .045       0   501.4     .07       0
  544.87     .12       0  564.91     .06       0
Bank Sta=482,501.4
XS Rating Curve= 0 ,0
Exp/Cntr=0.3,0.1

Type RM Length L Ch R = 1 ,70511.5 ,200.2,178.5,163
XS GIS Cut Line= 3
     1861779.177      223516.068     1862093.371      223354.495
     1862510.038      223355.798
#Sta/Elev= 30
       0 1885.42     9.8  1882.6    29.4 1877.43    58.9  1870.4    78.5 1865.37
    98.1 1859.31  148.231841.335   166.8 1835.82   176.6 1833.34  196.321829.336
   215.9 1825.87   235.5 1822.78   255.2 1820.08     265 1818.96   284.6 1817.46
   304.2 1816.43   323.9 1815.84     363 1815.26   372.7 1814.27  387.64 1811.46
   392.1 1810.79   401.8 1810.87  406.87  1811.6  424.011813.886   459.9  1816.8
   479.3 1817.52   508.3 1818.23   585.9  1819.4  678.341821.258     770 1823.14
#Mann= 7 ,-1 , 0
       0     .12       0  148.23    .016       0  196.32     .12       0
  387.64    .045       0  406.87     .12       0  424.01     .06       0
  678.34     .12       0
Bank Sta=387.64,406.87
XS Rating Curve= 0 ,0
Exp/Cntr=0.3,0.1

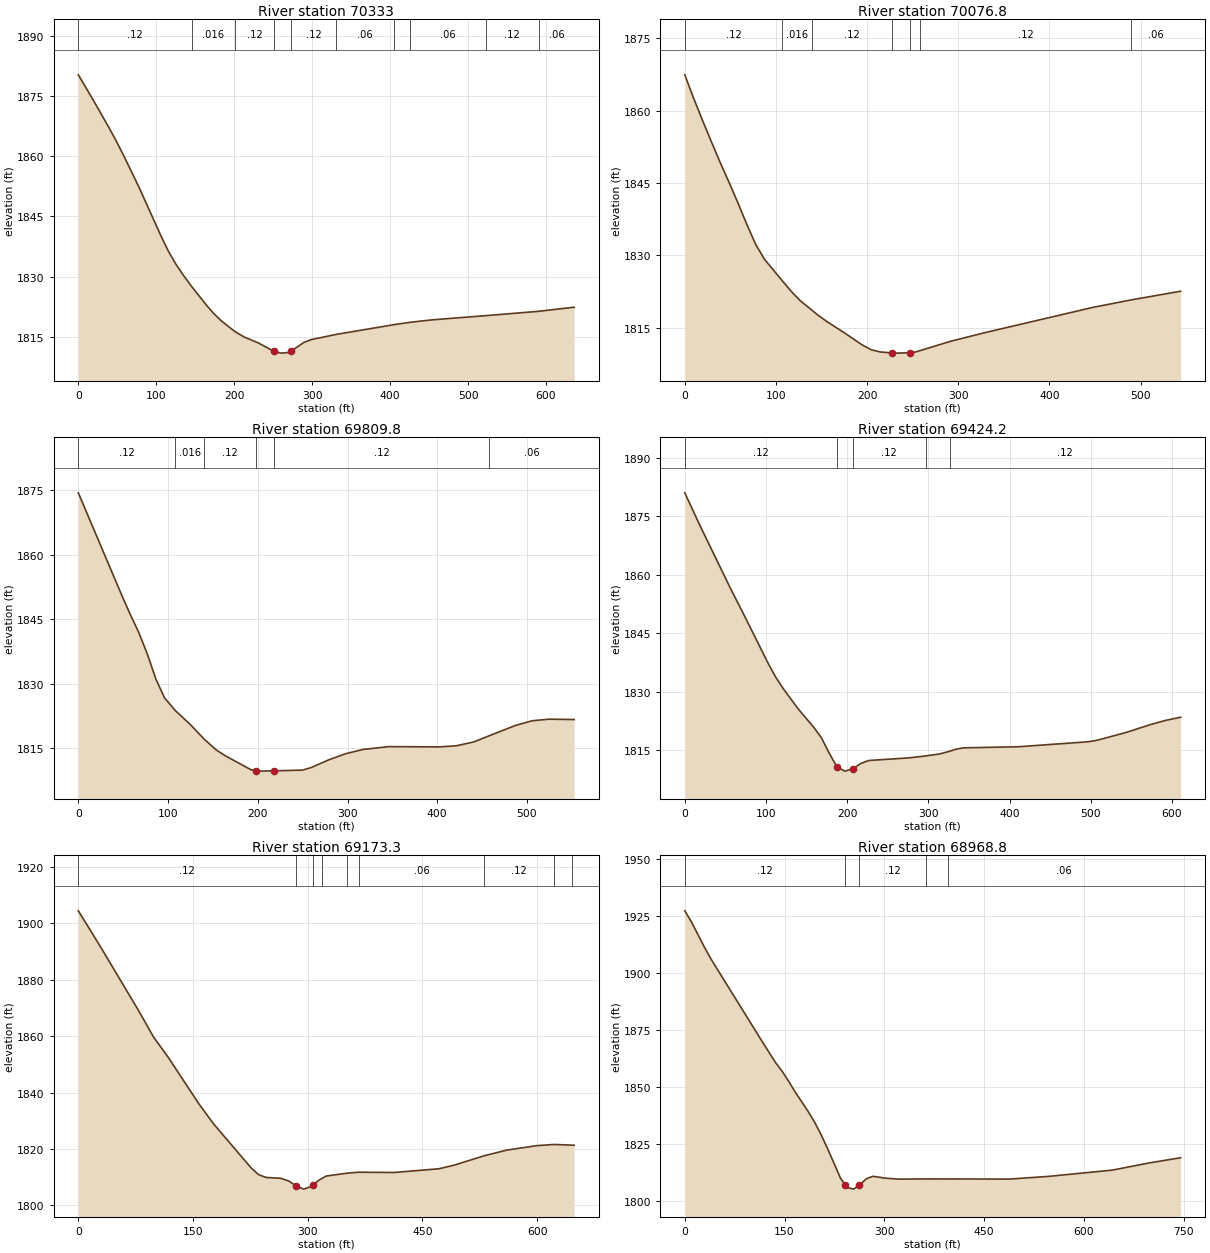
Type RM Length L Ch R = 1 ,70333   ,235,256.2,268.3
XS GIS Cut Line= 3
     1861883.344      223626.745     1862300.403      223448.245
     1862482.694      223439.131
#Sta/Elev= 30
       0 1880.23    19.3  1873.9    38.6 1867.34    48.3  1863.9    57.9 1860.26
    77.2 1852.55   106.2 1840.11   115.8 1836.28   125.5 1833.05   135.1  1830.3
  145.421827.585   164.1 1823.02   173.7 1820.88   183.4 1819.05  200.771816.411
   212.4 1815.07   231.6  1813.5     251 1811.44   260.6 1811.02   270.3 1811.19
  272.44 1811.43   289.6  1813.7   299.2  1814.4  331.241815.688  404.73 1818.09
  425.011818.667   453.6 1819.29  522.881820.341  590.461821.416   636.2 1822.44
#Mann= 10 ,-1 , 0
       0     .12       0  145.42    .016       0  200.77     .12       0
     251    .045       0  272.44     .12       0  331.24     .06       0
  404.73     .12       0  425.01     .06       0  522.88     .12       0
  590.46     .06       0
Bank Sta=251,272.44
XS Rating Curve= 0 ,0
Exp/Cntr=0.3,0.1

Type RM Length L Ch R = 1 ,70076.8 ,268.8,267,236.4
XS GIS Cut Line= 3
     1861957.955        223732.1     1862327.746      223730.798
     1862494.413      223680.016
#Sta/Elev= 30
       0  1867.4     9.7 1862.54    19.5 1857.94    29.2 1853.52    38.9 1849.19
    48.7 1845.05    58.4  1840.8    68.1 1836.38    77.8 1832.25    87.6 1829.12
  106.681824.781   116.8 1822.51   126.5  1820.6  139.341818.633     146  1817.6
   155.7 1816.28   175.2 1813.91   194.6 1811.42   204.4 1810.42   214.1 1809.96
     227 1809.76   233.6 1809.71   246.8  1809.8     253 1809.94  258.481810.248
   291.9 1812.18   330.9 1814.03   447.2 1819.17  489.911820.749     544 1822.54
#Mann= 7 ,-1 , 0
       0     .12       0  106.68    .016       0  139.34     .12       0
     227    .045       0   246.8     .06       0  258.48     .12       0
  489.91     .06       0
Bank Sta=227,246.8
XS Rating Curve= 0 ,0
Exp/Cntr=0.3,0.1

Type RM Length L Ch R = 1 ,69809.8 ,374.1,385.6,375.7
XS GIS Cut Line= 3
     1861989.205      224004.235     1862356.392      223928.714
     1862502.225      223827.152
#Sta/Elev= 30
       0  1874.4    48.1 1850.71    57.7  1846.2    67.3 1841.93    76.9 1836.88
    86.5 1831.02    96.1 1826.68  107.981823.756     125 1820.45  140.531817.024
   153.8 1814.56   163.4 1813.27   192.2 1809.98     198 1809.77   201.8 1809.64
   218.1 1809.71   249.9 1809.88   259.5 1810.47   278.8 1812.24     298  1813.7
   317.2 1814.68     346 1815.34   402.9 1815.28   421.6 1815.55   440.4 1816.41
  457.961817.873   487.1 1820.26   505.8 1821.36   524.5 1821.73   552.6 1821.64
#Mann= 6 ,-1 , 0
       0     .12       0  107.98    .016       0  140.53     .12       0
     198    .045       0   218.1     .12       0  457.96     .06       0
Bank Sta=198,218.1
XS Rating Curve= 0 ,0
Exp/Cntr=0.3,0.1

Type RM Length L Ch R = 1 ,69424.2 ,238.7,250.9,265.6
XS GIS Cut Line= 4
     1862038.467      224287.035     1862206.155      224274.644
     1862364.982      224227.876     1862637.105      224279.794
#Sta/Elev= 30
       0 1881.07    18.7 1872.66      56 1856.65    74.7 1848.99   102.8 1837.24
   112.1 1833.72   121.4 1830.76   140.1 1825.49   158.8 1820.89   168.2 1818.22
   177.9 1814.23   187.6 1810.63   197.4 1809.62   207.1 1810.23   216.8 1811.57
   226.6 1812.35   275.3 1813.01   296.61813.516   314.2 1814.04   326.71814.744
   333.7 1815.22   343.3  1815.6   410.1 1815.87   496.1 1817.14   505.7 1817.46
   515.2 1817.94   543.9 1819.57   572.5 1821.49   591.6 1822.61   610.8 1823.47
#Mann= 5 ,-1 , 0
       0     .12       0   187.6    .045       0   207.1     .12       0
   296.6    .016       0   326.7     .12       0
Bank Sta=187.6,207.1
XS Rating Curve= 0 ,0
Exp/Cntr=0.3,0.1

Type RM Length L Ch R = 1 ,69173.3 ,204.5,204.5,203.6
XS GIS Cut Line= 2
     1862001.507      224466.267     1862646.038      224537.882
#Sta/Elev= 30
       0 1904.48    29.5  1891.5    78.6 1869.16    98.3 1859.74   117.9 1852.38
   157.2 1836.17   176.9 1828.87     226 1813.25   235.8 1810.85   245.6 1809.87
   265.3 1809.54   275.1 1808.61     285 1806.86   294.8 1805.72   304.6 1806.63
  306.43 1807.01   314.4 1808.85  318.421809.469   324.2 1810.36  351.941811.402
  366.521811.722   412.7 1811.62   471.6 1812.94   491.3 1814.21  530.761817.553
   560.1 1819.55   599.4 1821.14  622.23 1821.57  645.851821.331   648.5 1821.28
#Mann= 9 ,-1 , 0
       0     .12       0     285    .045       0  306.43     .12       0
  318.42    .016       0  351.94     .12       0  366.52     .06       0
  530.76     .12       0  622.23     .06       0  645.85     .12       0
Bank Sta=285,306.43
XS Rating Curve= 0 ,0
Exp/Cntr=0.3,0.1

Type RM Length L Ch R = 1 ,68968.8 ,224,226,228.3
XS GIS Cut Line= 3
     1861949.473      224638.322     1862560.376        224706.2
     1862629.398      224595.162
#Sta/Elev= 30
       0 1927.34     9.8 1922.59    29.3 1911.51      39 1906.44    48.8 1901.78
   117.1 1869.68   136.6 1860.75   146.4 1856.99   156.1 1852.64   165.9 1847.96
   185.4 1839.42   195.1 1834.71   204.9 1829.23   214.6 1823.14   234.2 1810.09
   241.4 1807.13   243.9  1806.1   253.7 1805.35   262.2 1807.06   273.2 1809.94
   282.9 1810.98   302.4 1810.13     322 1809.73  363.05 1809.83  395.211809.799
   487.8 1809.75   546.4 1810.92   642.7 1813.68   698.7 1816.86   745.4 1819.11
#Mann= 5 ,-1 , 0
       0     .12       0   241.4    .045       0   262.2     .12       0
  363.05    .016       0  395.21     .06       0
Bank Sta=241.4,262.2
XS Rating Curve= 0 ,0
Exp/Cntr=0.3,0.1

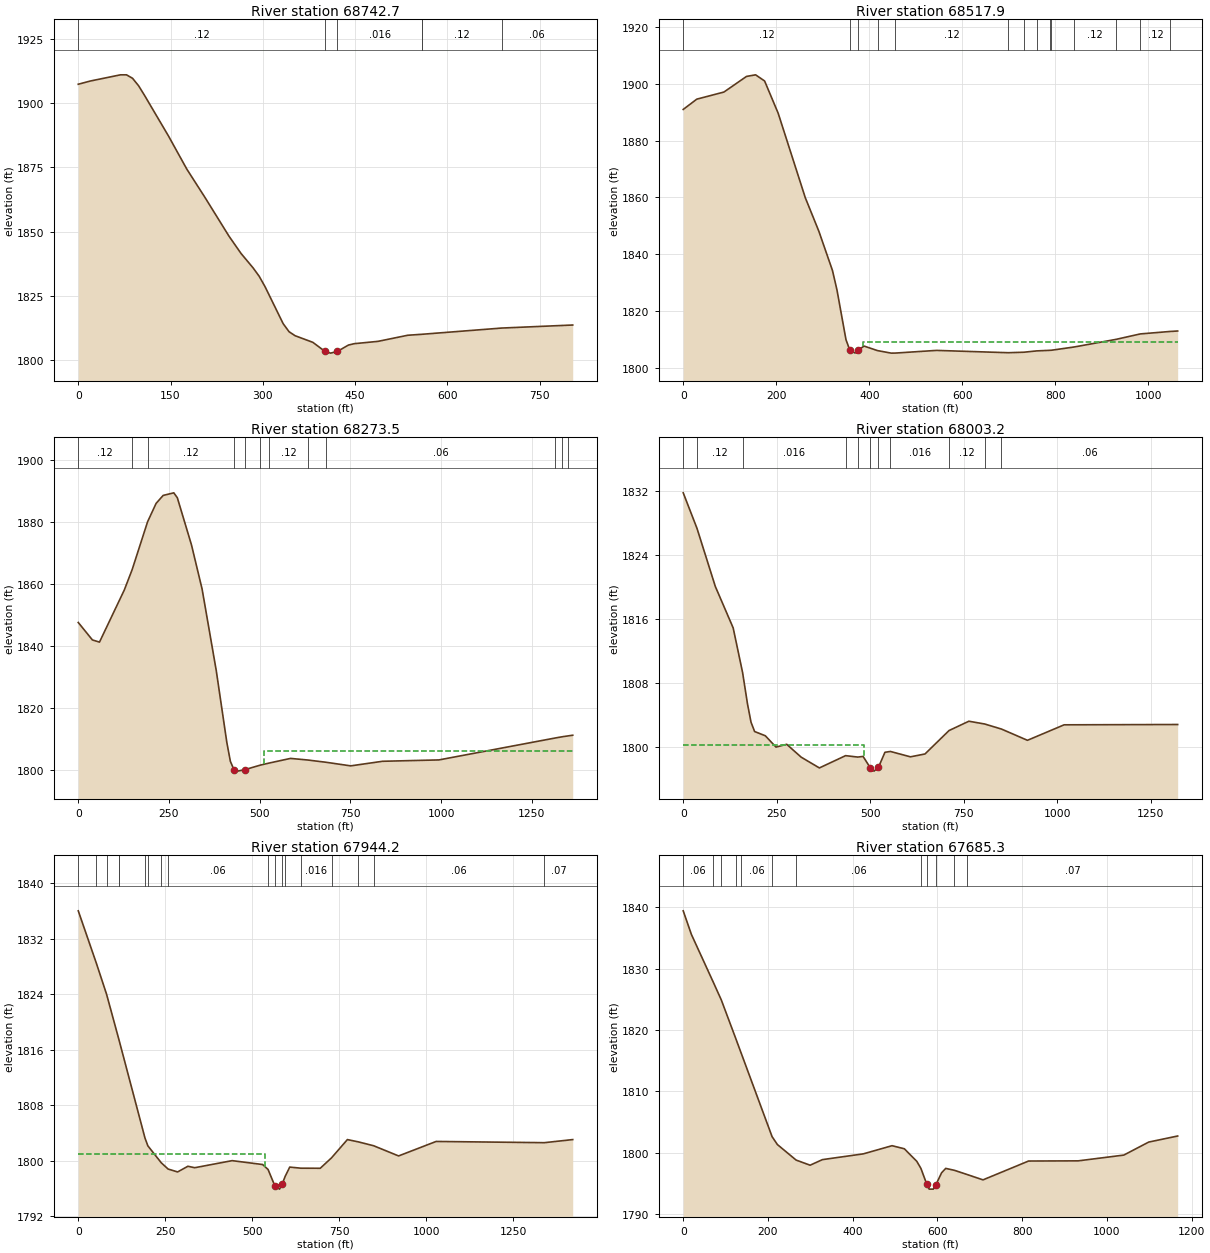
Type RM Length L Ch R = 1 ,68742.7 ,219.3,224.9,230.5
XS GIS Cut Line= 4
     1861862.184       224859.93     1862185.534       224857.76
     1862413.399      224896.823     1862646.738      224810.016
#Sta/Elev= 30
       0  1907.4    19.6 1908.65    68.6 1911.06    78.4 1911.06    88.2 1909.71
      98 1906.82   107.8 1903.02     147 1887.09   176.4 1874.36   205.8 1863.38
     245 1848.24   264.6 1841.51   284.2 1835.89     294 1832.66   303.8 1828.47
     333 1814.19   342.6 1811.06   352.3 1809.52   381.2 1806.94   400.2 1803.54
     410 1802.74   421.1  1803.4     439 1805.88   448.6 1806.42   487.1 1807.32
   535.3 1809.69  558.161810.069  558.27 1810.07  688.16  1812.5   803.5 1813.68
#Mann= 6 ,-1 , 0
       0     .12       0   400.2    .045       0   421.1    .016       0
  558.16     .06       0  558.27     .12       0  688.16     .06       0
Bank Sta=400.2,421.1
XS Rating Curve= 0 ,0
Exp/Cntr=0.3,0.1

Type RM Length L Ch R = 1 ,68517.9 ,239.2,244.4,248.7
XS GIS Cut Line= 3
     1861814.924      224933.461     1862525.211      225170.259
     1862633.718       224875.12
#Sta/Elev= 30
       0 1890.98    29.2  1894.6    87.5  1897.1   136.1 1902.61   155.6 1903.17
     175    1901   204.2 1889.63   262.5 1859.88   291.7 1848.05   320.9 1834.26
   330.6 1827.39     350 1809.86  357.94 1806.32   369.5 1805.18  375.83 1806.16
   388.9 1807.62  417.821806.024   447.3 1805.14  456.291805.159   544.5  1806.1
  698.631805.286  732.611805.461  760.091805.924  788.481806.125  791.761806.158
  840.871807.309  930.771809.989   982.81811.902 1047.691812.782  1063.2 1812.93
#Mann= 14 ,-1 , 0
       0     .12       0  357.94    .045       0  375.83     .12       0
  417.82    .016       0  456.29     .12       0  698.63    .016       0
  732.61     .06       0  760.09    .016       0  788.48     .12       0
  791.76    .016       0  840.87     .12       0  930.77     .06       0
   982.8     .12       0 1047.69     .06       0
#XS Ineff= 2 , 0
                          387.62         1809.12
Permanent Ineff=
       F       F
Bank Sta=357.94,375.83
XS Rating Curve= 0 ,0
Exp/Cntr=0.3,0.1

Type RM Length L Ch R = 1 ,68273.5 ,331,270.3,209.9
XS GIS Cut Line= 3
     1861682.062      225074.774     1862439.441      225435.017
     1862730.239      224998.819
#Sta/Elev= 30
       0 1847.62      39 1841.98    58.5 1841.28   126.8 1858.09  148.441864.663
  191.061880.161   214.6 1886.11     234 1888.68   263.3 1889.52   273.1 1887.92
   312.1 1872.69   341.3 1858.44   380.3 1832.13   409.6 1808.79   419.3 1802.73
   429.1 1800.08   438.8 1799.59   458.4 1800.04  502.291801.542  526.711802.211
   585.1  1803.7  632.071803.187  683.351802.446   750.9 1801.29   838.7 1802.77
     994 1803.21  1315.21810.307 1334.271810.698  1351.11810.991  1362.9 1811.19
#Mann= 12 ,-1 , 0
       0     .12       0  148.44     .06       0  191.06     .12       0
   429.1    .045       0   458.4     .12       0  502.29    .016       0
  526.71     .12       0  632.07    .016       0  683.35     .06       0
  1315.2     .12       0 1334.27     .06       0  1351.1     .12       0
#XS Ineff= 2 , 0
                           512.9         1805.95
Permanent Ineff=
       F       F
Bank Sta=429.1,458.4
XS Rating Curve= 0 ,0
Exp/Cntr=0.3,0.1

Type RM Length L Ch R = 1 ,68003.2 ,59,59,59.3
XS GIS Cut Line= 4
     1861714.397       225806.87     1861993.043      225707.912
      1862159.71      225323.797     1862711.793      225576.402
#Sta/Elev= 30
       0 1831.79    36.81827.341    85.8 1820.06   133.5 1814.87  158.681809.281
   171.7 1805.37   181.2 1803.06   190.8 1801.89   219.4 1801.36     248 1799.94
   276.6 1800.29   315.2 1798.68   363.9 1797.33  433.931798.868  466.361798.691
   480.7 1798.77   500.3 1797.33   509.9 1796.93   521.8 1797.41   539.1 1799.29
  553.831799.393   607.3 1798.72   646.2 1799.08  710.471802.015   763.4 1803.18
  805.531802.835  850.56  1802.2     920 1800.79    1018 1802.73  1321.5 1802.77
#Mann= 11 ,-1 , 0
       0     .06       0    36.8     .12       0  158.68    .016       0
  433.93     .06       0  466.36     .12       0   500.3    .045       0
   521.8     .12       0  553.83    .016       0  710.47     .12       0
  805.53    .016       0  850.56     .06       0
#XS Ineff= 2 , 0
          482.56  1800.2
Permanent Ineff=
       F       F
Bank Sta=500.3,521.8
XS Rating Curve= 0 ,0
Exp/Cntr=0.3,0.1

Type RM Length L Ch R = 1 ,67944.2 ,216.1,258.9,301.5
XS GIS Cut Line= 4
     1861711.903      225855.478     1862045.126      225735.256
     1862211.793      225351.141     1862799.033      225623.277
#Sta/Elev= 30
       0 1836.05   51.831828.509   81.351824.007  116.54 1817.51  117.781817.279
  191.571803.273  199.871802.139  238.61 1799.68  258.01 1798.79   285.4 1798.37
   314.9 1799.19   334.6 1798.98   441.9    1800   529.5 1799.44  545.151798.729
   564.3  1796.4   578.2 1795.89   585.8 1796.63  594.371797.736   607.4 1799.07
  639.34 1798.91   695.1  1798.9   727.81800.424     773 1803.04  804.811802.705
  848.511802.148   920.1 1800.68  1027.9 1802.77 1338.751802.592  1420.2 1803.04
#Mann= 18 ,-1 , 0
       0     .06       0   51.83     .12       0   81.35     .06       0
  116.54     .12       0  117.78     .06       0  191.57     .08       0
  199.87     .06       0  238.61    .016       0  258.01     .06       0
  545.15    .016       0   564.3    .045       0   585.8    .016       0
  594.37     .12       0  639.34    .016       0   727.8     .12       0
  804.81    .016       0  848.51     .06       0 1338.75     .07       0
#XS Ineff= 2 , 0
          536.64 1800.98
Permanent Ineff=
       F       F
Bank Sta=564.3,585.8
XS Rating Curve= 0 ,0
Exp/Cntr=0.3,0.1

Type RM Length L Ch R = 1 ,67685.3 ,426.8,387.5,348.3
XS GIS Cut Line= 3
     1861701.052      225868.499     1862193.564      225696.193
     1862838.095      225668.849
#Sta/Elev= 30
       0 1839.45    19.3  1835.6   70.621827.865   89.781824.938  124.441818.552
  137.271816.159  209.69 1802.64   222.2 1801.35  266.411798.816   299.5 1797.98
   328.5 1798.89   425.2 1799.83   492.8 1801.16   521.8 1800.66   551.1 1798.62
  560.881797.472   574.4 1794.95   580.4 1794.08   590.2 1794.08   596.2 1794.79
   609.8 1796.75   619.5 1797.46  640.191797.144  669.731796.466   707.5 1795.59
     815 1798.66   932.3 1798.69  1039.8 1799.63  1098.5 1801.75  1166.9 1802.74
#Mann= 12 ,-1 , 0
       0     .06       0   70.62     .12       0   89.78     .06       0
  124.44     .12       0  137.27     .06       0  209.69    .016       0
  266.41     .06       0  560.88     .12       0   574.4    .045       0
   596.2     .06       0  640.19     .12       0  669.73     .07       0
Bank Sta=574.4,596.2
XS Rating Curve= 0 ,0
Exp/Cntr=0.3,0.1