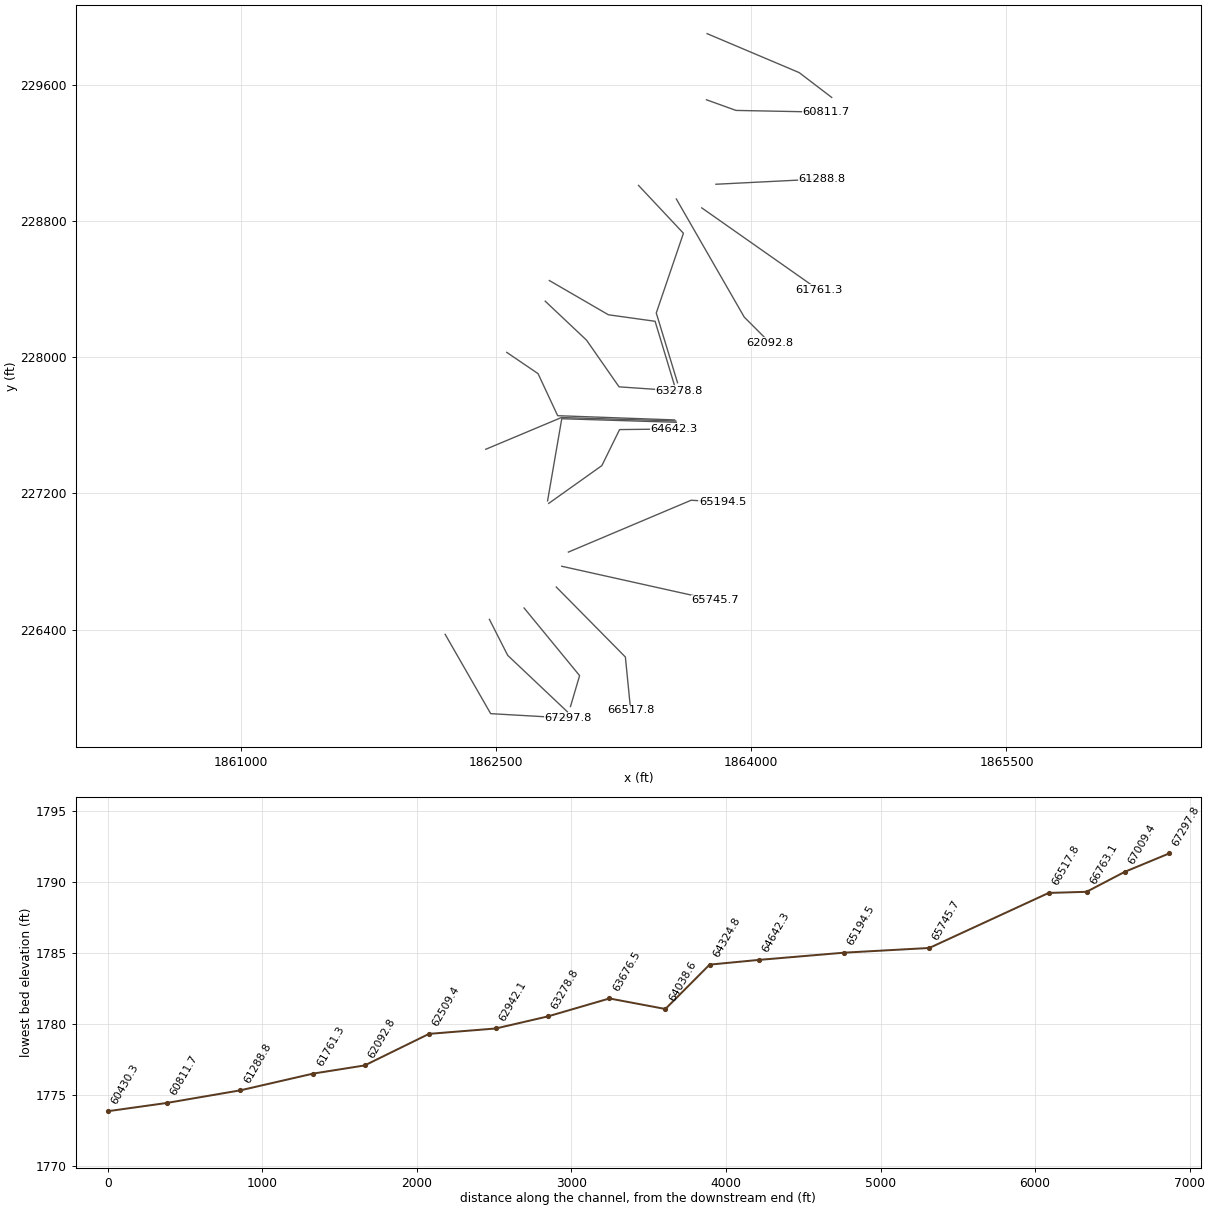
HEC-RAS study TETERCK.prj: TETERCK

--- TETERCK.g01 (geometry) --- (continued)

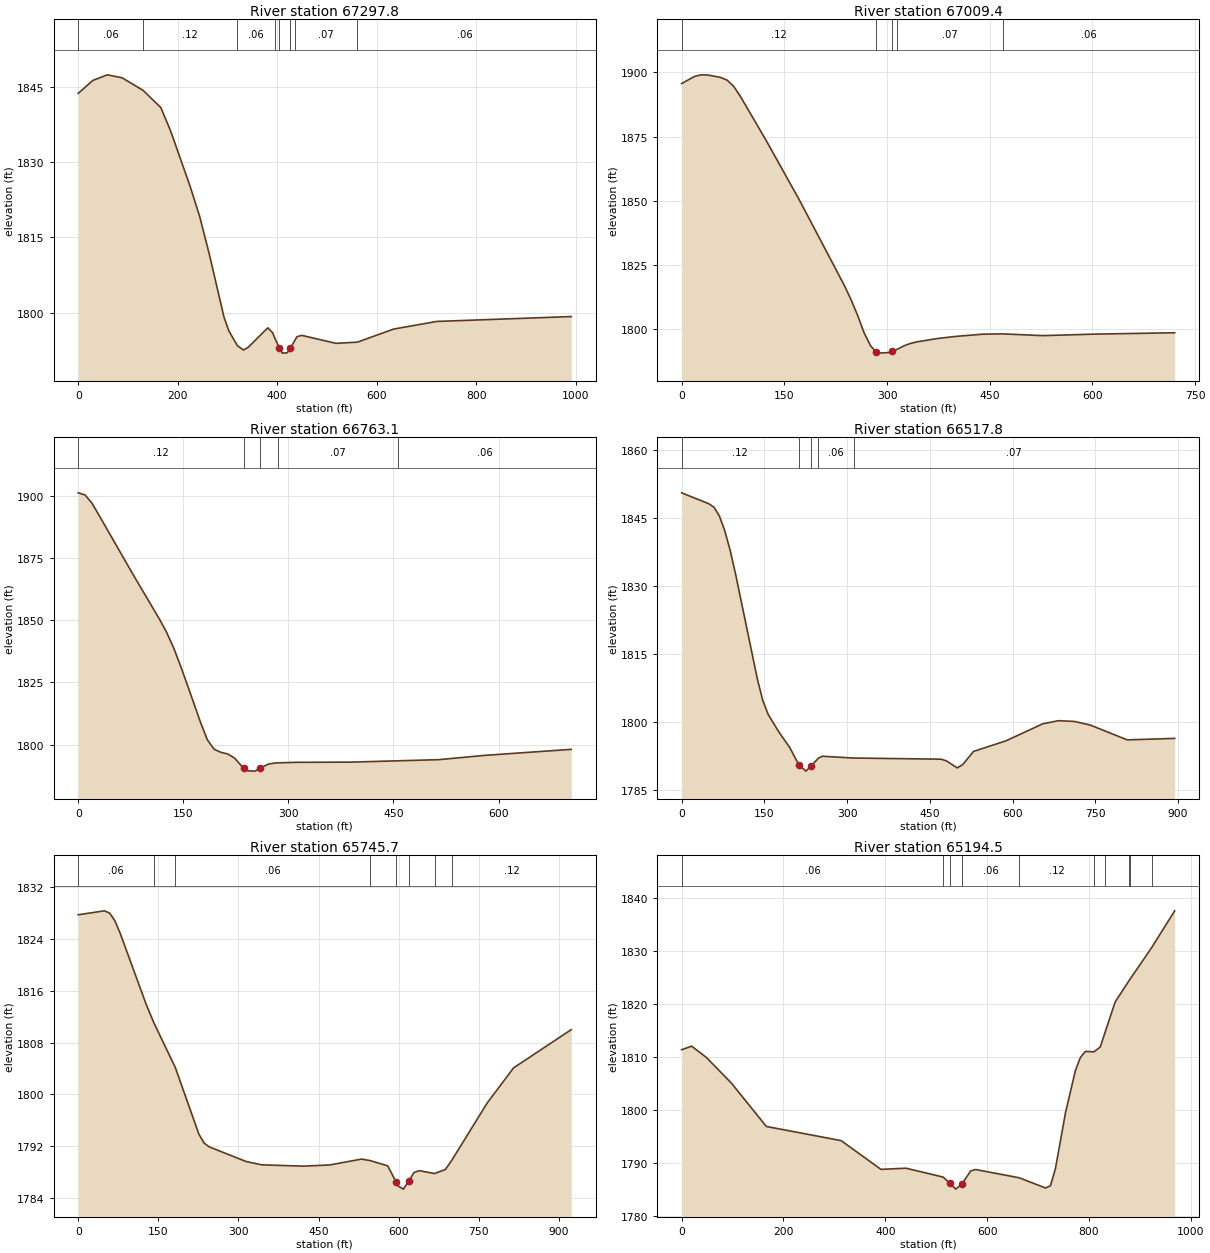
Type RM Length L Ch R = 1 ,67297.8 ,276.9,288.4,299.2
XS GIS Cut Line= 3
     1862200.184      226371.971     1862467.737      225905.779
     1862920.862      225879.737
#Sta/Elev= 30
       0 1843.65    29.3 1846.22    58.6 1847.34      88 1846.76   130.31844.268
   166.1 1840.84   185.7 1836.22   224.8 1825.24   244.3 1819.17   263.9 1811.57
   293.2 1799.15     303 1796.42  320.221793.473   332.3 1792.63     342 1793.18
   381.2 1797.04   390.9 1796.07  395.811794.883   404.5 1793.04   410.5 1792.01
   420.2 1792.06   426.5    1793  435.421794.488   439.8 1795.27   449.6 1795.54
     518 1793.96  561.421794.191   634.1 1796.79     721 1798.31   991.4 1799.28
#Mann= 8 ,-1 , 0
       0     .06       0   130.3     .12       0  320.22     .06       0
  395.81     .12       0   404.5    .045       0   426.5     .12       0
  435.42     .07       0  561.42     .06       0
Bank Sta=404.5,426.5
XS Rating Curve= 0 ,0
Exp/Cntr=0.3,0.1

Type RM Length L Ch R = 1 ,67009.4 ,251,246.3,241.6
XS GIS Cut Line= 3
     1862460.216      226460.175     1862567.855      226248.369
     1862918.549      225916.772
#Sta/Elev= 30
       0 1895.62      19 1898.42    28.5 1899.02      38 1898.96      57 1898.01
    66.5 1896.94      76 1894.57    85.5 1890.77   123.6 1873.42   171.1 1850.74
   237.6 1817.09   247.2 1811.67   256.9 1805.53   266.6 1798.58   276.2 1793.47
  283.95 1791.22   285.8 1790.71   305.2 1790.95  307.93 1791.36  314.161792.113
   324.5 1793.52   334.1 1794.46   343.8  1795.1   372.7 1796.36   401.7 1797.25
   440.3 1798.09  469.011798.201   527.2 1797.52   604.4 1798.11   720.2 1798.64
#Mann= 5 ,-1 , 0
       0     .12       0  283.95    .045       0  307.93     .12       0
  314.16     .07       0  469.01     .06       0
Bank Sta=283.95,307.93
XS Rating Curve= 0 ,0
Exp/Cntr=0.3,0.1

Type RM Length L Ch R = 1 ,66763.1 ,241.7,245.3,248.9
XS GIS Cut Line= 3
      1862664.05      226526.922     1862990.439      226129.353
     1862936.864      225947.663
#Sta/Elev= 30
       0 1901.16     9.7 1900.33    19.4  1897.1    29.1 1892.46    77.6 1868.69
   116.5 1850.15   126.2  1845.1   135.9 1839.08   145.6 1831.97   155.3 1824.39
   174.7 1808.85   184.4 1801.87   194.1 1798.09   203.8 1796.86   213.5  1796.2
   223.2 1794.55   232.9 1791.48  237.33 1790.44   242.6 1789.41   252.3 1789.31
  259.58 1790.51   271.8 1792.15   281.5 1792.58  285.341792.635   310.6 1792.85
   388.2 1792.92  455.991793.458   514.4 1793.91   580.7 1795.65   703.8 1798.06
#Mann= 5 ,-1 , 0
       0     .12       0  237.33    .045       0  259.58     .06       0
  285.34     .07       0  455.99     .06       0
Bank Sta=237.33,259.58
XS Rating Curve= 0 ,0
Exp/Cntr=0.3,0.1

Type RM Length L Ch R = 1 ,66517.8 ,687.2,772.2,783.6
XS GIS Cut Line= 3
     1862853.286      226650.186     1863259.536      226238.728
     1863290.786      225924.492
#Sta/Elev= 30
       0 1850.53      49 1848.15    58.8 1847.35    68.6 1845.39    78.4 1842.11
    88.2 1837.77      98 1832.53   137.2 1809.58     147 1804.85   156.8 1801.74
   176.4 1797.84     196 1794.44  212.76 1790.55   225.4 1789.23   235.2 1790.41
  247.65 1792.05   254.8 1792.51  311.631792.116   470.4 1791.86   480.2 1791.48
   499.8 1789.94   509.6 1790.66   529.2 1793.57   587.8 1795.89   654.8 1799.65
   683.5 1800.34   712.2 1800.17   740.9 1799.38   807.9 1796.11     894 1796.44
#Mann= 5 ,-1 , 0
       0     .12       0  212.76    .045       0   235.2     .12       0
  247.65     .06       0  311.63     .07       0
Bank Sta=212.76,235.2
XS Rating Curve= 0 ,0
Exp/Cntr=0.3,0.1

Type RM Length L Ch R = 1 ,65745.7 ,526.4,551.1,573.6
XS GIS Cut Line= 2
     1862885.578      226772.235      1863786.62      226571.714
#Sta/Elev= 30
       0 1827.74    49.1 1828.35    58.9    1828    68.7 1826.81    78.6 1824.88
   127.7 1813.81  141.881811.021  181.821804.146   225.9 1793.86   235.7 1792.48
   245.5 1791.88   314.2 1789.63   343.7 1789.11   422.3 1788.91   471.4  1789.1
   530.3    1790  546.391789.772   579.4 1788.96  595.24 1786.46     599 1785.83
   608.8 1785.36   618.7 1786.57   628.5 1787.91   638.3 1788.21   667.11787.771
   687.4 1788.39  699.78 1789.86     766  1798.7   815.1 1804.09   923.1    1810
#Mann= 8 ,-1 , 0
       0     .06       0  141.88     .12       0  181.82     .06       0
  546.39     .12       0  595.24    .045       0   618.7     .12       0
   667.1    .016       0  699.78     .12       0
Bank Sta=595.24,618.7
XS Rating Curve= 0 ,0
Exp/Cntr=0.3,0.1

Type RM Length L Ch R = 1 ,65194.5 ,523.7,552.3,580.1
XS GIS Cut Line= 3
      1862924.64      226855.568     1863645.995      227160.256
      1863830.89      227149.839
#Sta/Elev= 30
       0 1811.35    19.6 1812.03    48.9 1809.87    97.9 1805.03   166.4 1796.86
   313.2 1794.19   391.5 1788.76   440.5 1788.98  513.721787.301  526.64 1786.11
   538.4 1785.03   550.4    1786   567.7 1788.48   577.5 1788.73  662.891787.173
   714.5 1785.25   724.3 1785.67   734.1 1788.95   753.7 1799.42   773.3 1807.45
   783.1  1809.9   792.8 1811.04  809.541810.948     822 1811.87  832.111814.808
   851.3 1820.37  878.021824.302  879.651824.544  923.531830.718   968.2 1837.58
#Mann= 10 ,-1 , 0
       0     .06       0  513.72     .12       0  526.64    .045       0
   550.4     .06       0  662.89     .12       0  809.54    .016       0
  832.11     .12       0  878.02     .06       0  879.65     .12       0
  923.53     .06       0
Bank Sta=526.64,550.4
XS Rating Curve= 0 ,0
Exp/Cntr=0.3,0.1

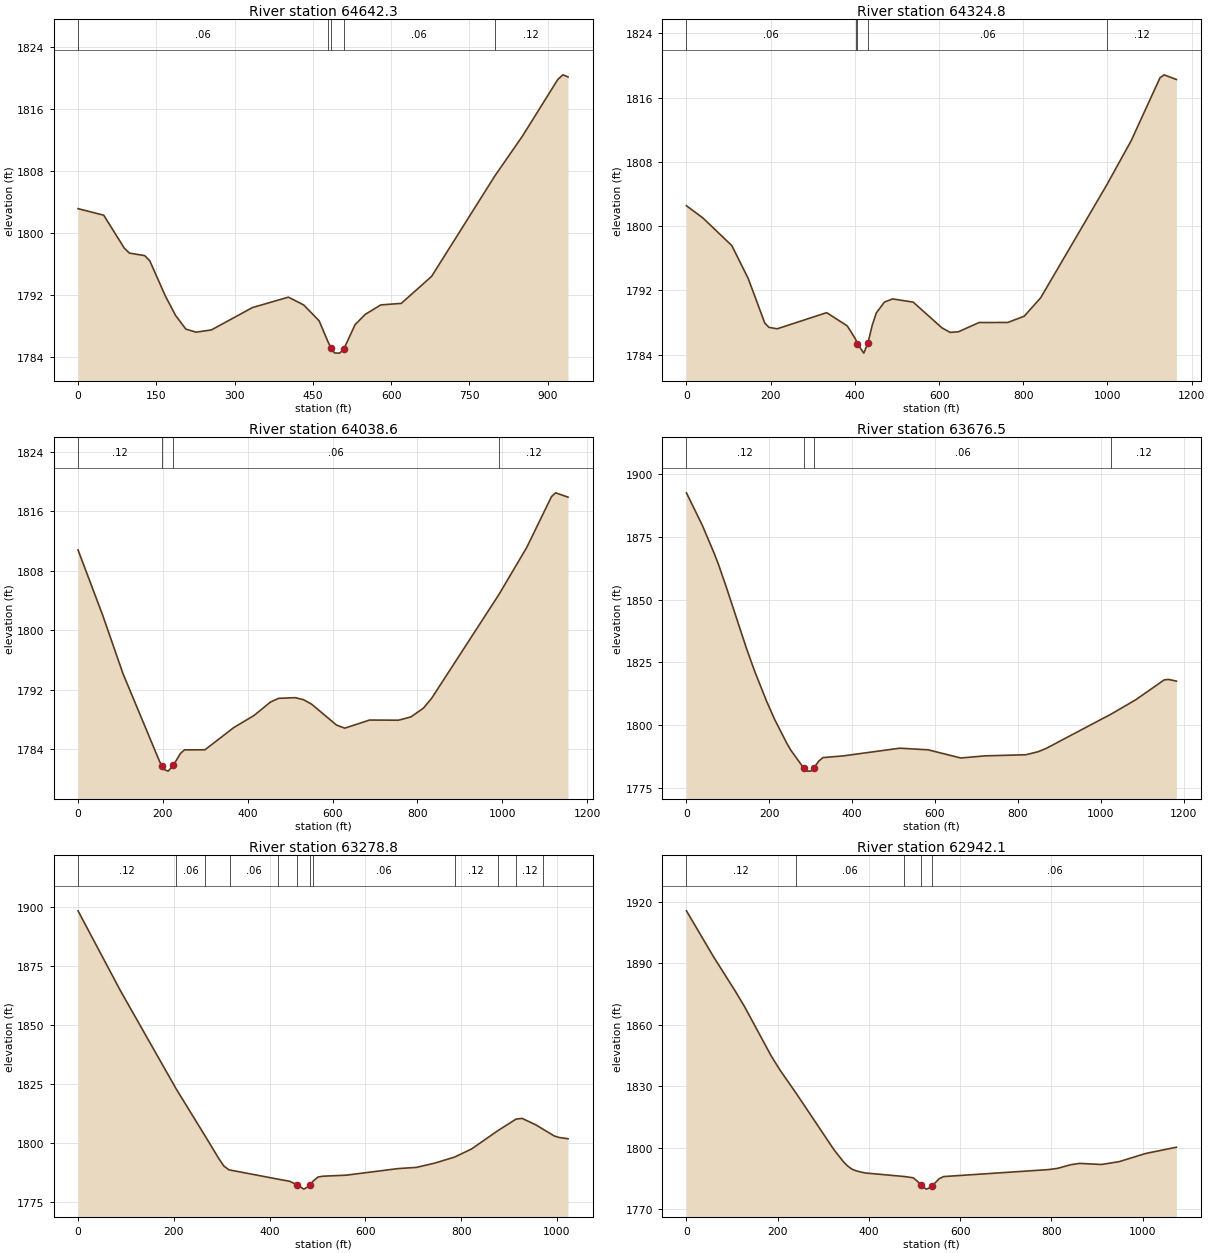
Type RM Length L Ch R = 1 ,64642.3 ,306.8,317.5,328.1
XS GIS Cut Line= 4
     1862808.799      227141.664     1863121.299      227363.886
     1863225.466      227575.692      1863544.91      227579.164
#Sta/Elev= 30
       0 1803.13    49.2 1802.29    88.5 1798.06    98.3 1797.41   127.8 1797.08
   137.6  1796.4   167.2  1791.9   186.8 1789.39   206.5 1787.62   226.1 1787.22
   255.6 1787.51   334.3 1790.39   403.1 1791.73   432.6 1790.72   462.1 1788.68
  478.791786.014   484.9 1785.18   491.6 1784.54   501.5 1784.52   509.1 1785.02
     531 1788.19   550.6 1789.52   580.2 1790.73   619.5 1790.93   677.6 1794.41
  798.271807.292   851.8 1812.49   919.6 1819.79   929.3 1820.37     939  1820.1
#Mann= 5 ,-1 , 0
       0     .06       0  478.79     .12       0   484.9    .045       0
   509.1     .06       0  798.27     .12       0
Bank Sta=484.9,509.1
XS Rating Curve= 0 ,0
Exp/Cntr=0.3,0.1

Type RM Length L Ch R = 1 ,64324.8 ,324.2,286.2,250.2
XS GIS Cut Line= 3
     1862802.245      227156.784     1862885.578      227639.422
     1863559.189      227618.589
#Sta/Elev= 30
       0 1802.55    39.2 1801.02   107.8 1797.58   146.9 1793.46   186.1 1787.93
   195.9  1787.4   215.5 1787.22     333 1789.23     382 1787.58  401.571785.943
  405.91 1785.36   421.2 1784.19     431 1785.43   440.8 1787.57   450.6 1789.17
   470.2 1790.55   489.8 1790.94   538.6 1790.54     607 1787.33   626.5 1786.77
     646 1786.85   694.9    1788   763.3 1788.01   802.3 1788.79   841.4 1791.09
  999.231805.232  1056.3 1810.65  1124.6 1818.47  1134.4 1818.85  1163.7 1818.27
#Mann= 5 ,-1 , 0
       0     .06       0  401.57     .12       0  405.91    .045       0
     431     .06       0  999.23     .12       0
Bank Sta=405.91,431
XS Rating Curve= 0 ,0
Exp/Cntr=0.3,0.1

Type RM Length L Ch R = 1 ,64038.6 ,420.3,362.1,300.8
XS GIS Cut Line= 3
     1862438.682      227459.861     1862883.561      227646.493
     1863555.653      227626.311
#Sta/Elev= 30
       0 1810.82    57.9 1802.07   106.1 1794.16     193 1782.26  198.51 1781.74
   202.6 1781.29   212.3 1781.07  224.47 1781.83   241.2 1783.44   250.9 1783.93
   299.1 1783.94   366.6 1786.91   414.9 1788.56   453.5 1790.36   472.8 1790.86
   511.7 1790.95   531.2 1790.68   550.6 1790.07   609.1 1787.27   628.6 1786.85
   687.1 1787.94   755.3 1787.92   784.5 1788.36   813.8 1789.53   833.2 1790.85
  992.351804.859  1057.4 1811.14  1115.9 1817.99  1125.6  1818.5  1154.8 1817.92
#Mann= 4 ,-1 , 0
       0     .12       0  198.51    .045       0  224.47     .06       0
  992.35     .12       0
Bank Sta=198.51,224.47
XS Rating Curve= 0 ,0
Exp/Cntr=0.3,0.1

Type RM Length L Ch R = 1 ,63676.5 ,392.1,397.7,399
XS GIS Cut Line= 4
     1862562.208      228029.558     1862746.236      227904.558
     1862861.529      227657.378     1863548.772      227632.478
#Sta/Elev= 30
       0  1892.4    38.7 1879.35    67.7 1868.08    77.4 1863.91    96.7 1854.72
   145.1  1830.5   164.4 1821.62   193.4 1809.63   212.8  1802.4     242 1792.97
   251.7  1790.2   282.6 1783.14   290.6 1781.84   300.4 1781.81   307.5 1783.03
   319.9 1785.88   329.6 1787.19   378.3 1787.86   514.9 1790.92   583.6 1790.28
   662.2 1787.03   721.2 1787.88   819.4 1788.32   848.9 1789.52   868.5 1790.84
 1025.841804.523  1084.7 1810.17  1153.4 1818.06  1163.3 1818.26  1182.9 1817.58
#Mann= 4 ,-1 , 0
       0     .12       0   282.6    .045       0   307.5     .06       0
 1025.84     .12       0
Bank Sta=282.6,307.5
XS Rating Curve= 0 ,0
Exp/Cntr=0.3,0.1

Type RM Length L Ch R = 1 ,63278.8 ,305.1,336.7,363.6
XS GIS Cut Line= 4
     1862788.356      228330.395     1863031.411      228101.228
     1863222.383      227826.922      1863576.55      227802.617
#Sta/Elev= 30
       0 1898.33    88.4 1864.58  204.391823.172  266.021802.843   294.8 1793.22
   304.6 1790.32   314.4 1788.81  317.741788.619  418.081784.757   442.2 1783.86
  456.97 1782.39   471.7 1780.55  484.39 1782.09   490.9 1783.93   501.2 1785.67
     511 1786.01   560.2 1786.46   668.3 1789.24   706.7 1789.75     745 1791.56
  786.421794.116   821.8 1797.54  876.221805.213  914.781810.185   927.4 1810.49
   956.1 1807.75  971.591805.861   994.5 1803.07  1004.1 1802.43  1023.3 1801.88
#Mann= 12 ,-1 , 0
       0     .12       0  204.39     .06       0  266.02     .12       0
  317.74     .06       0  418.08     .12       0  456.97    .045       0
  484.39     .12       0   490.9     .06       0  786.42     .12       0
  876.22     .06       0  914.78     .12       0  971.59     .06       0
Bank Sta=456.97,484.39
XS Rating Curve= 0 ,0
Exp/Cntr=0.3,0.1

Type RM Length L Ch R = 1 ,62942.1 ,498.9,432.6,365.7
XS GIS Cut Line= 4
     1862812.661      228451.922     1863159.883      228250.534
     1863434.189      228212.339     1863548.772      227833.867
#Sta/Elev= 30
       0  1915.5    58.7 1893.34   107.7 1876.07   127.3 1868.77     186  1844.6
   205.6 1837.62  240.69  1826.4   323.1    1799   342.7 1793.43   352.4 1791.16
   362.2 1789.51     372  1788.6   391.6 1787.58  476.911785.869   496.9 1785.24
   506.4 1783.51   513.2 1781.77   525.6  1779.7   535.1 1780.49   538.7 1781.35
   554.2 1784.84   563.8 1785.83   794.1 1789.24   813.4 1789.84   842.3 1791.61
   861.6 1792.26   909.8 1791.72   948.4 1793.12  1006.3 1797.09  1073.8 1800.15
#Mann= 5 ,-1 , 0
       0     .12       0  240.69     .06       0  476.91     .12       0
   513.2    .045       0   538.7     .06       0
Bank Sta=513.2,538.7
XS Rating Curve= 0 ,0
Exp/Cntr=0.3,0.1

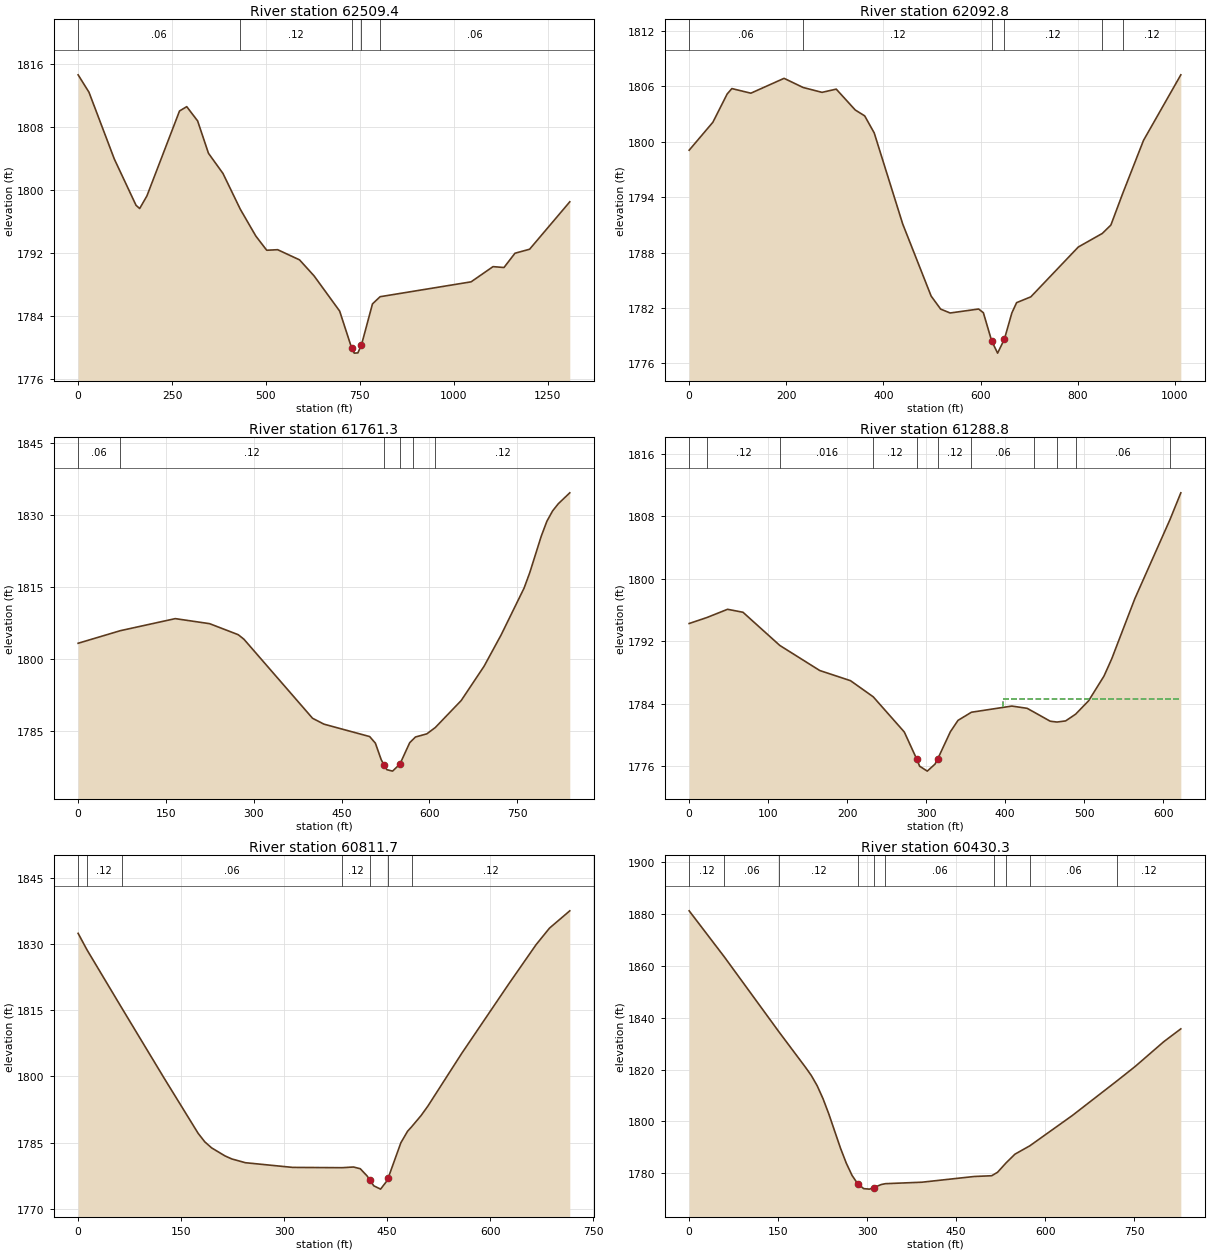
Type RM Length L Ch R = 1 ,62509.4 ,384.6,416.6,448.9
XS GIS Cut Line= 4
     1863336.967       229010.95     1863600.856        228729.7
     1863441.133       228260.95     1863566.133      227851.228
#Sta/Elev= 30
       0 1814.65    28.9 1812.44    96.4 1803.96   154.3 1798.08   163.9 1797.68
   183.2 1799.28     270 1810.06   289.2 1810.61   318.2  1808.8   347.1 1804.69
   385.7 1802.13  431.811797.592   473.1 1794.19   502.2 1792.38   531.3 1792.45
   589.6 1791.16   628.4 1789.12   696.4 1784.66   728.7 1779.92   735.2 1779.32
   744.9 1779.35   754.5 1780.37   783.8 1785.57  804.141786.483  1046.4 1788.37
  1104.8  1790.3    1134 1790.19  1163.2    1792  1202.2 1792.51  1309.2 1798.53
#Mann= 5 ,-1 , 0
       0     .06       0  431.81     .12       0   728.7    .045       0
   754.5     .12       0  804.14     .06       0
Bank Sta=728.7,754.5
XS Rating Curve= 0 ,0
Exp/Cntr=0.3,0.1

Type RM Length L Ch R = 1 ,62092.8 ,314.7,331.5,348.1
XS GIS Cut Line= 3
     1863559.189      228931.089     1863958.495      228236.645
       1864107.8      228087.339
#Sta/Elev= 30
       0 1799.09    48.8 1802.12    78.2 1805.18    87.9 1805.77     127 1805.27
   195.4 1806.88  234.53 1805.89   273.5 1805.36   302.8 1805.71   341.9 1803.45
   361.4 1802.81     381 1800.96   439.6  1791.1   498.2 1783.28   517.8 1781.87
   537.3 1781.45   595.9 1781.88   605.7 1781.48   622.8 1778.42     635  1777.1
     649 1778.62   664.3 1781.45   674.1 1782.57   703.4  1783.2   801.1  1788.6
  850.52 1790.07   868.2 1790.98  892.23 1794.36   935.4 1800.16  1012.2 1807.26
#Mann= 6 ,-1 , 0
       0     .06       0  234.53     .12       0   622.8    .045       0
     649     .12       0  850.52    .016       0  892.23     .12       0
Bank Sta=622.8,649
XS Rating Curve= 0 ,0
Exp/Cntr=0.3,0.1

Type RM Length L Ch R = 1 ,61761.3 ,447.2,472.5,497.8
XS GIS Cut Line= 2
     1863708.495      228879.006     1864395.995      228396.367
#Sta/Elev= 30
       0 1803.21   72.171805.836     166 1808.35   224.6  1807.3   273.5    1805
   283.3 1804.05   400.5 1787.56     420 1786.33   498.1 1783.74   507.9 1782.36
   517.7 1778.95  522.26 1777.88   527.4 1776.84   537.2 1776.53  549.73 1777.99
   566.5 1782.46  572.091783.139   576.3 1783.65   595.8 1784.31  610.151785.621
   654.4 1791.25   693.5  1798.4   722.8 1804.98   761.9 1814.72   771.6 1817.94
   791.2 1825.54   800.9 1828.68   810.7 1830.84   820.5 1832.34     840  1834.6
#Mann= 6 ,-1 , 0
       0     .06       0   72.17     .12       0  522.26    .045       0
  549.73     .12       0  572.09    .016       0  610.15     .12       0
Bank Sta=522.26,549.73
XS Rating Curve= 0 ,0
Exp/Cntr=0.3,0.1

Type RM Length L Ch R = 1 ,61288.8 ,481.6,477.1,464.7
XS GIS Cut Line= 2
     1863791.828      229017.895     1864413.356      229049.145
#Sta/Elev= 30
       0 1794.25   22.621795.021    48.6 1796.07    68.1 1795.69  114.751791.439
   165.3 1788.23   204.2 1786.93  232.991784.864   272.3 1780.36  288.27 1776.84
   291.7 1775.98   301.4 1775.35   311.2 1776.25  314.64 1776.92   330.6 1780.39
   340.3 1781.85  357.27 1782.89   408.4 1783.68   427.8 1783.39  437.041782.871
     457 1781.74  465.591781.634   476.5 1781.78  489.221782.648   505.6 1784.36
   525.1 1787.53   534.8 1789.72     564 1797.41  608.471807.532   622.3 1810.98
#Mann= 11 ,-1 , 0
       0     .06       0   22.62     .12       0  114.75    .016       0
  232.99     .12       0  288.27    .045       0  314.64     .12       0
  357.27     .06       0  437.04     .12       0  465.59    .016       0
  489.22     .06       0  608.47     .12       0
#XS Ineff= 2 , 0
                          396.59         1784.59
Permanent Ineff=
       F       F
Bank Sta=288.27,314.64
XS Rating Curve= 0 ,0
Exp/Cntr=0.3,0.1

Type RM Length L Ch R = 1 ,60811.7 ,396.1,381.4,366.1
XS GIS Cut Line= 3
     1863736.272      229514.422     1863909.883      229451.922
     1864441.133      229441.506
#Sta/Elev= 30
       0 1832.39   12.941828.651   63.181815.587   126.2 1799.35   174.8 1787.09
   184.5 1785.16   194.4  1783.8     214 1781.97   223.9 1781.29   243.6 1780.44
   312.4 1779.38  384.431779.315     401 1779.47   410.8 1779.08   420.7 1777.46
   424.4 1776.61   430.5 1775.21   440.4 1774.46   450.2 1776.44   451.5    1777
   469.9 1784.95   479.7 1787.57  485.841788.624   499.4 1791.13   509.2 1793.25
   558.4 1805.17   627.3 1820.99   666.7  1829.8   686.4 1833.58   715.9 1837.49
#Mann= 7 ,-1 , 0
       0     .06       0   12.94     .12       0   63.18     .06       0
  384.43     .12       0   424.4    .045       0   451.5    .016       0
  485.84     .12       0
Bank Sta=424.4,451.5
XS Rating Curve= 0 ,0
Exp/Cntr=0.3,0.1

Type RM Length L Ch R = 1 ,60430.3 ,335.7,435.4,463.9
XS GIS Cut Line= 3
     1863739.745      229903.311     1864281.411      229674.145
     1864472.383      229528.311
#Sta/Elev= 30
       0 1881.32   59.431863.485  152.131834.333     196 1820.92   205.8 1817.75
   215.6 1813.84   225.5 1808.82   235.3  1802.9   254.9 1789.74   264.7 1783.92
   274.5 1779.16   283.9 1775.97   294.1 1774.07   303.9 1773.88   311.3 1774.47
   323.5 1775.65  330.781775.984   392.1 1776.55   480.3 1778.76   509.7 1779.05
  513.41 1779.55   519.5 1780.37  534.141784.054   548.9 1787.37  574.081790.621
   645.8 1802.34  721.441815.777   751.5 1821.24   799.6 1830.79   828.4 1835.76
#Mann= 10 ,-1 , 0
       0     .12       0   59.43     .06       0  152.13     .12       0
   283.9    .045       0   311.3     .12       0  330.78     .06       0
  513.41     .12       0  534.14    .016       0  574.08     .06       0
  721.44     .12       0
Bank Sta=283.9,311.3
XS Rating Curve= 0 ,0
Exp/Cntr=0.3,0.1