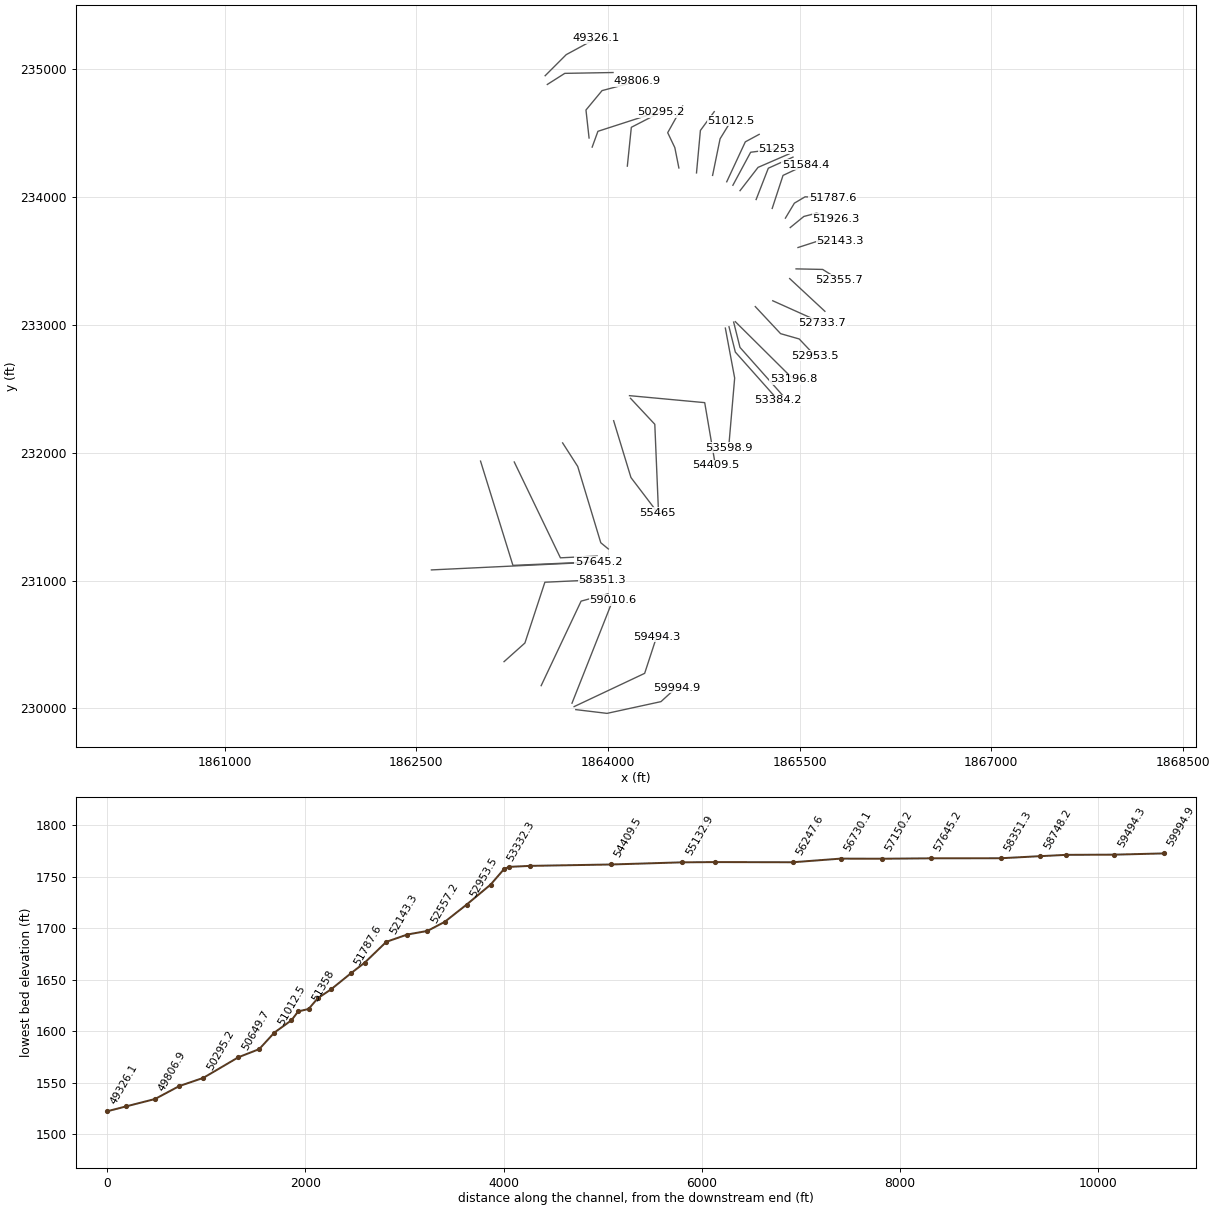
HEC-RAS study TETERCK.prj: TETERCK

--- TETERCK.g01 (geometry) --- (continued)

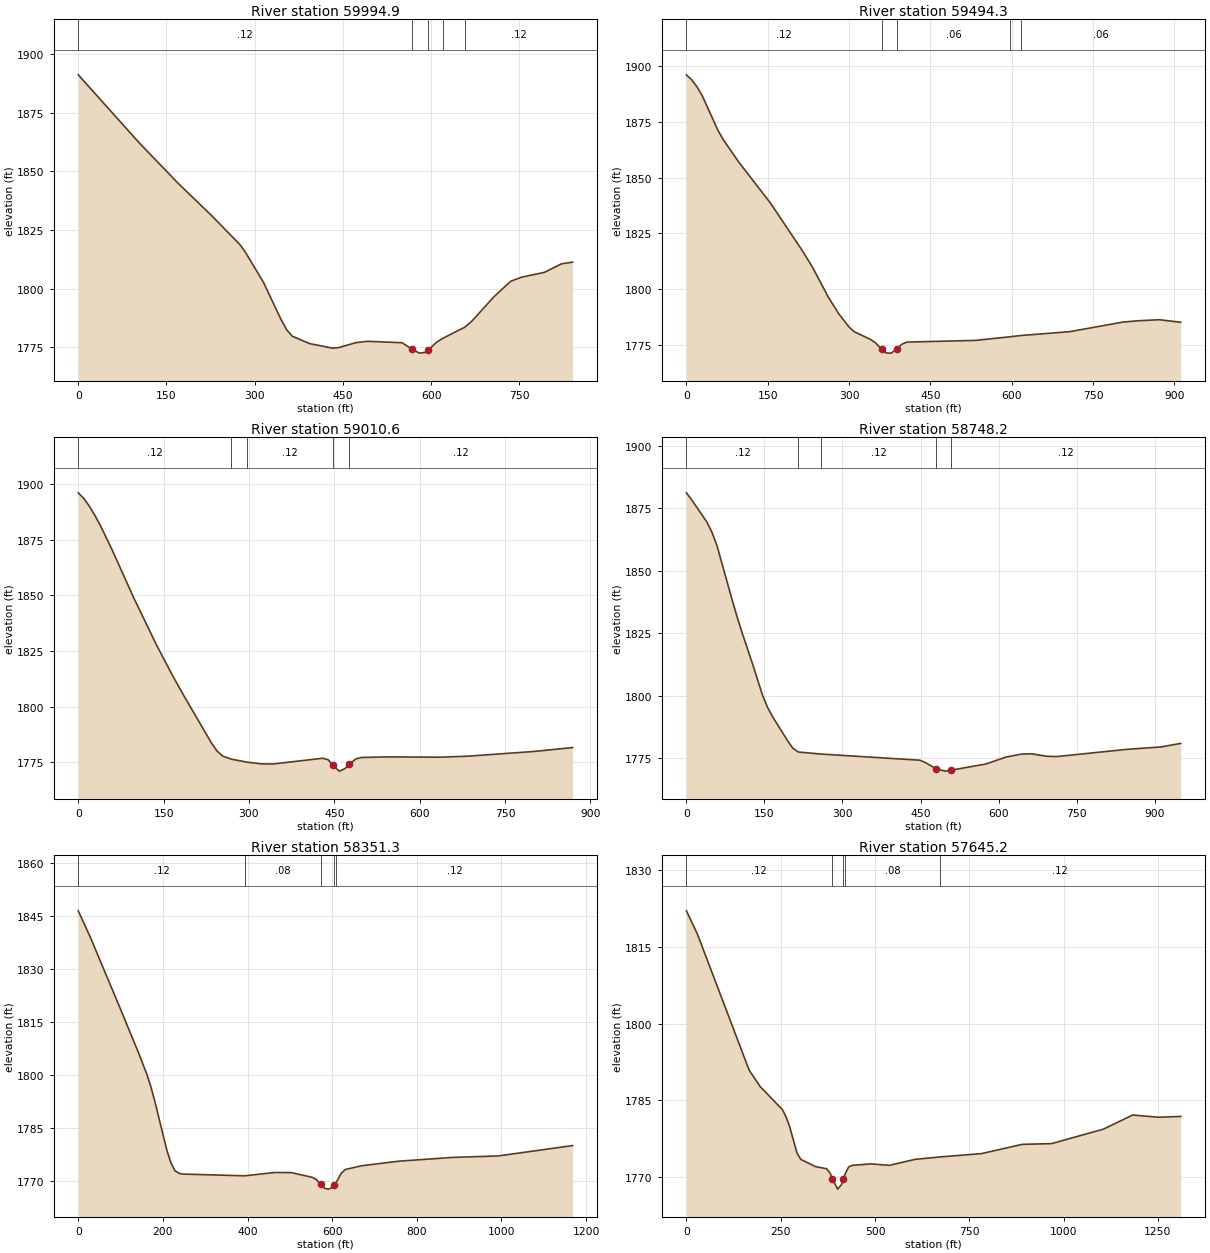
Type RM Length L Ch R = 1 ,59994.9 ,195.5,500.5,506.3
XS GIS Cut Line= 4
     1863748.252      229989.754     1863992.651      229960.309
     1864414.919      230052.254      1864534.71      230161.629
#Sta/Elev= 30
       0 1891.07   104.2 1861.95   170.4  1844.7   227.2 1830.98   275.6 1818.54
   285.4    1815   314.9 1802.66   344.4 1787.04   354.2 1782.51     364 1779.67
   393.5 1776.53   432.8 1774.57   442.6 1774.81   472.1 1776.93   491.7 1777.51
   550.6 1776.91   567.4 1774.15   580.1 1772.47   589.9 1772.78   595.2 1773.85
   609.6 1777.16  620.251778.823  657.151783.495   668.5 1785.89     707 1796.53
   735.6 1803.14   754.7 1804.89   792.8 1806.89   821.5 1810.52   840.5 1811.25
#Mann= 5 ,-1 , 0
       0     .12       0   567.4    .045       0   595.2     .12       0
  620.25    .016       0  657.15     .12       0
Bank Sta=567.4,595.2
XS Rating Curve= 0 ,0
Exp/Cntr=0.3,0.1

Type RM Length L Ch R = 1 ,59494.3 ,454.2,483.7,512.6
XS GIS Cut Line= 3
     1863735.231      230013.192     1864287.314      230273.609
     1864381.064      230560.067
#Sta/Elev= 30
       0 1896.24     9.7 1893.98    19.4  1890.9    29.1 1886.89    58.1 1871.33
    67.8  1867.2    96.9 1856.94     155 1838.66   213.2  1817.5   232.5  1809.9
   261.6 1796.47     281 1788.95   300.4 1782.85     310  1780.8   339.1 1777.49
   348.8 1775.88   360.2 1773.01   368.2 1771.36   377.9 1771.26   388.5 1773.23
   397.3 1775.25     407 1776.22   532.9 1776.97  596.961778.608  616.781779.158
   707.6 1780.91   804.9 1785.19     834 1785.81   872.9 1786.26   911.8 1785.11
#Mann= 5 ,-1 , 0
       0     .12       0   360.2    .045       0   388.5     .06       0
  596.96     .12       0  616.78     .06       0
Bank Sta=360.2,388.5
XS Rating Curve= 0 ,0
Exp/Cntr=0.3,0.1

Type RM Length L Ch R = 1 ,59010.6 ,258.4,262.4,276.6
XS GIS Cut Line= 2
     1863718.738      230040.102     1864038.356      230847.756
#Sta/Elev= 30
       0  1896.1     9.8 1893.56    19.5 1890.08    29.3 1885.95      39 1881.36
    58.6 1870.99    97.6 1848.87   136.6 1828.23   165.9 1813.91   185.4 1805.04
   234.2 1783.68     244 1780.07   253.8 1777.83  269.221776.428  297.351775.075
   322.1 1774.33   341.6 1774.26   429.4 1776.85   439.2  1776.2   447.6 1773.64
   458.7 1771.07   468.5 1772.16   476.2 1774.14     488 1776.55   497.7 1777.21
   546.5 1777.47   634.4 1777.33   683.2 1777.76   800.3 1779.89   868.6 1781.66
#Mann= 5 ,-1 , 0
       0     .12       0  269.22     .06       0  297.35     .12       0
   447.6    .045       0   476.2     .12       0
Bank Sta=447.6,476.2
XS Rating Curve= 0 ,0
Exp/Cntr=0.3,0.1

Type RM Length L Ch R = 1 ,58748.2 ,397.5,396.9,384.7
XS GIS Cut Line= 3
     1863477.419      230177.254     1863789.919      230838.713
     1864000.856      230896.004
#Sta/Elev= 30
       0 1881.24     9.8 1878.52      39 1869.65    48.8 1865.59    58.5 1860.27
    87.8 1838.43    97.5 1831.51   107.3 1825.04   126.8 1812.95   146.3 1800.19
   156.1 1795.27   165.8 1791.54   195.1 1781.79   204.8 1778.92  215.371777.453
  258.661776.652   448.7 1774.18   458.4 1773.35   479.7 1770.75   497.5 1769.81
   508.5 1770.18   575.5 1772.65   614.5 1775.45   643.8 1776.62   663.3 1776.76
   692.6 1775.75     712 1775.64   845.6 1778.51   912.1 1779.49   950.1 1780.91
#Mann= 5 ,-1 , 0
       0     .12       0  215.37     .06       0  258.66     .12       0
   479.7    .045       0   508.5     .12       0
Bank Sta=479.7,508.5
XS Rating Curve= 0 ,0
Exp/Cntr=0.3,0.1

Type RM Length L Ch R = 1 ,58351.3 ,752,706.1,658.2
XS GIS Cut Line= 4
     1863186.967      230365.117     1863350.161       230510.95
     1863506.411      230986.645     1863954.328      231007.478
#Sta/Elev= 30
       0 1846.46    28.6 1838.97    95.2 1820.01   142.7 1806.25   161.8 1800.34
   171.3 1796.88   180.8 1792.67   209.3 1778.83   218.9 1775.22   228.7 1772.96
   238.5 1772.24   248.3 1772.04  393.041771.553   464.3  1772.5   503.6 1772.45
   552.7 1771.13   562.5  1770.5   572.9  1769.1   582.1 1768.03   591.9 1767.79
   601.8 1768.37  604.66 1768.92  609.951769.774   621.4 1772.28   631.2 1773.35
   670.5 1774.41   758.6  1775.7   885.3 1776.76   992.5 1777.17    1168  1780.1
#Mann= 5 ,-1 , 0
       0     .12       0  393.04     .08       0   572.9    .045       0
  604.66     .08       0  609.95     .12       0
Bank Sta=572.9,604.66
XS Rating Curve= 0 ,0
Exp/Cntr=0.3,0.1

Type RM Length L Ch R = 1 ,57645.2 ,545.1,495,444.8
XS GIS Cut Line= 2
      1862618.39      231082.999     1863927.418      231145.499
#Sta/Elev= 30
       0 1821.99    29.3 1817.42   166.3 1790.91   195.6  1787.7   254.3 1783.23
   264.1 1781.82   273.8 1779.87   293.4 1774.68   303.2  1773.5   342.3 1772.09
   371.6 1771.68   381.4 1770.77   386.6 1769.76     401  1767.7   410.8 1768.54
   416.3 1769.73  421.321770.748   430.3 1772.04   440.1 1772.34     489 1772.62
   537.9 1772.34   606.4 1773.51  671.271773.971   782.4 1774.63     890 1776.43
   968.2 1776.58  1105.1 1779.39  1183.4 1782.16  1251.8 1781.72  1310.5 1781.88
#Mann= 5 ,-1 , 0
       0     .12       0   386.6    .045       0   416.3     .12       0
  421.32     .08       0  671.27     .12       0
Bank Sta=386.6,416.3
XS Rating Curve= 0 ,0
Exp/Cntr=0.3,0.1

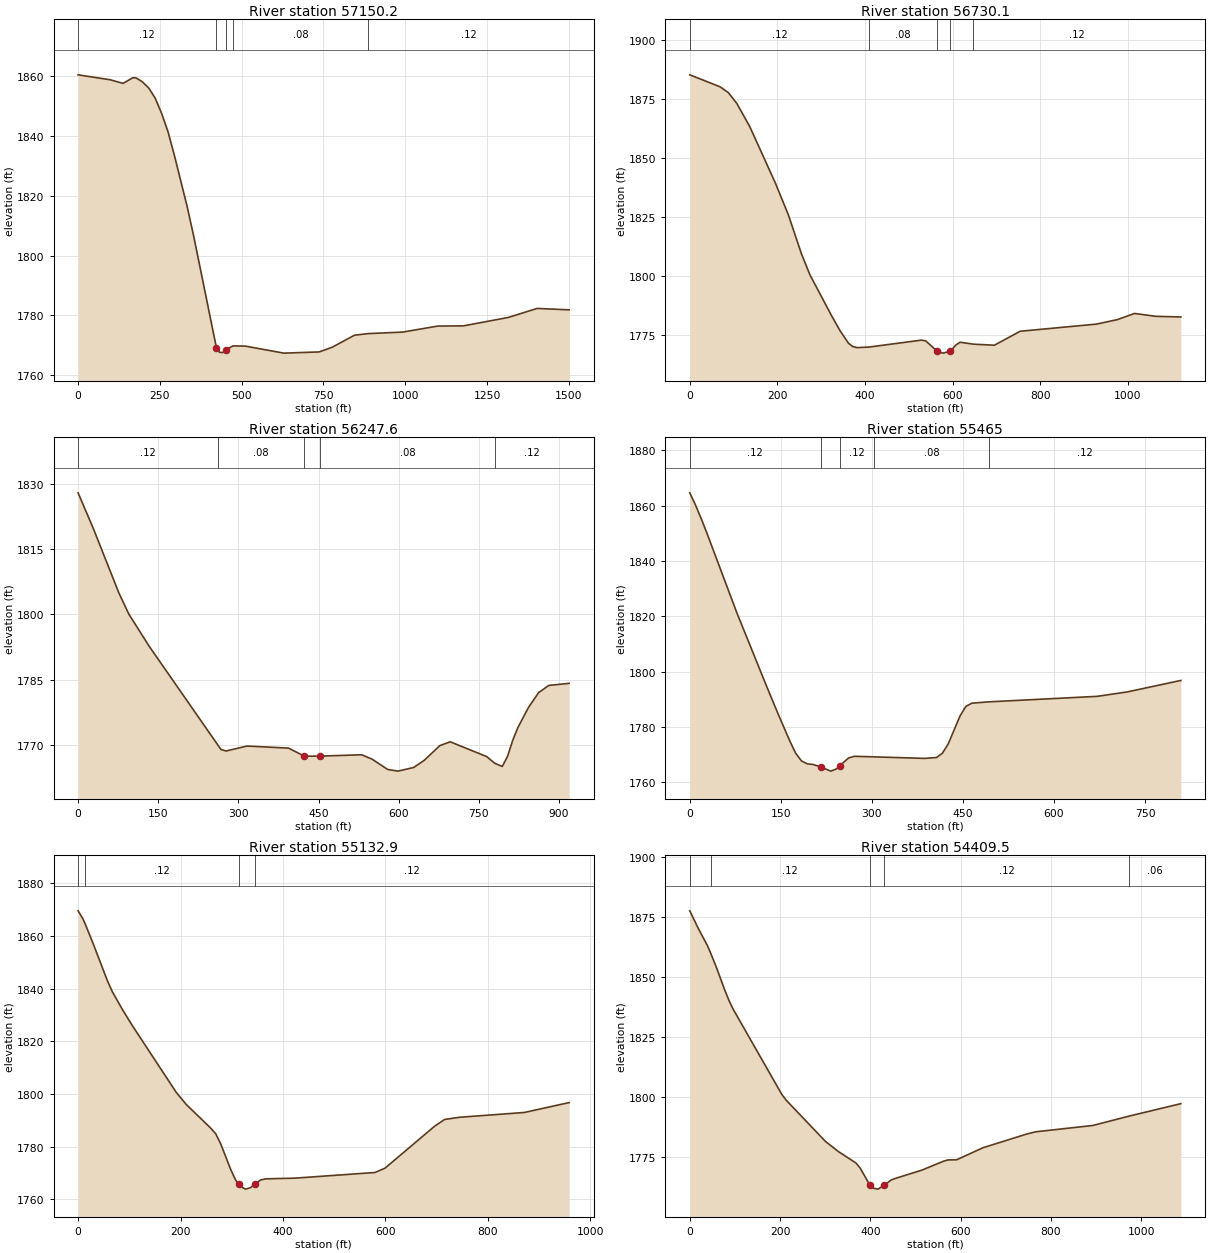
Type RM Length L Ch R = 1 ,57150.2 ,405.2,420.1,426.3
XS GIS Cut Line= 3
     1863002.939      231934.561     1863256.411      231118.589
     1863902.245      231146.367
#Sta/Elev= 30
       0 1860.53    98.2 1858.87   137.5 1857.66     167 1859.54   176.8 1859.53
   196.4  1858.2   216.1  1856.1   235.7  1852.7   255.4 1847.59     275  1841.4
   294.6 1833.44   333.9 1816.16   353.6 1806.36   422.9 1769.05   432.1  1767.6
     442  1767.5   452.9 1768.51  473.541769.733   510.7 1769.67   628.6 1767.31
   736.6 1767.71   775.9 1769.24   844.6  1773.3  886.21 1773.85   991.6 1774.35
  1099.3 1776.37  1177.6 1776.44  1314.8 1779.26  1402.9 1782.28  1500.9 1781.81
#Mann= 5 ,-1 , 0
       0     .12       0   422.9    .045       0   452.9     .12       0
  473.54     .08       0  886.21     .12       0
Bank Sta=422.9,452.9
XS Rating Curve= 0 ,0
Exp/Cntr=0.3,0.1

Type RM Length L Ch R = 1 ,56730.1 ,494.7,482.5,477.4
XS GIS Cut Line= 3
     1863266.828      231927.617     1863627.939      231177.617
     1863916.133      231191.506
#Sta/Elev= 30
       0 1885.14    68.6 1880.12    88.1  1877.6   107.7 1872.94   137.1 1863.16
   195.9 1839.13   225.2 1825.82   254.6 1809.56   274.2 1800.55   323.2 1783.38
   342.8 1776.96   362.3 1771.58   372.1  1770.2   381.9 1769.74  409.571769.983
   528.8 1772.91   538.6  1772.6  564.16 1768.29   577.8 1767.41  594.91  1768.2
   607.2 1770.84     617 1772.02  647.561771.194   695.3 1770.76   754.1 1776.66
   928.6 1779.69   976.7 1781.62  1015.1  1784.2  1063.2 1782.99  1120.9  1782.7
#Mann= 5 ,-1 , 0
       0     .12       0  409.57     .08       0  564.16    .045       0
  594.91     .08       0  647.56     .12       0
Bank Sta=564.16,594.91
XS Rating Curve= 0 ,0
Exp/Cntr=0.3,0.1

Type RM Length L Ch R = 1 ,56247.6 ,773.7,782.6,778.1
XS GIS Cut Line= 4
       1863645.3      232076.922     1863763.356      231892.895
     1863943.911      231295.672     1864002.939      231247.061
#Sta/Elev= 30
       0 1828.02    28.5  1819.8      76 1805.05    95.1 1800.04   133.1 1792.65
  260.941770.017   267.4 1768.87   277.1 1768.53   316.1 1769.67   394.1 1769.19
   423.4 1767.33   452.6 1767.35   530.6 1767.66   550.1 1766.66   579.3 1764.28
   598.8 1763.89   628.1 1764.74   647.6 1766.36   676.8 1769.75   696.3 1770.65
   764.6 1767.25  780.011765.675   793.8 1764.97   803.6 1767.27   813.3 1770.96
   823.1 1773.95   842.6  1778.5   861.7 1781.96   880.8 1783.64     919 1784.12
#Mann= 5 ,-1 , 0
       0     .12       0  260.94     .08       0   423.4    .045       0
   452.6     .08       0  780.01     .12       0
Bank Sta=423.4,452.6
XS Rating Curve= 0 ,0
Exp/Cntr=0.3,0.1

Type RM Length L Ch R = 1 ,55465   ,340.2,332.1,323.6
XS GIS Cut Line= 3
     1864044.606      232250.534     1864180.022      231806.089
     1864388.356      231531.784
#Sta/Elev= 30
       0 1864.61     9.7 1860.06    19.4 1854.98      29 1849.59    77.4 1821.35
   125.8 1795.13   145.2 1784.88   164.6 1775.05   174.2 1770.61   183.9 1767.75
   193.6 1766.68   203.3 1766.45   215.6 1765.57   232.3 1764.05     242 1764.89
     247    1766   261.4 1768.76     271 1769.41  304.161769.201   387.2 1768.65
   406.5 1768.97   416.2 1770.53   425.9 1773.94   445.3    1784   454.9 1787.45
   464.6 1788.59  492.711789.083   671.3 1791.07   720.5 1792.66   809.1 1796.82
#Mann= 5 ,-1 , 0
       0     .12       0   215.6    .045       0     247     .12       0
  304.16     .08       0  492.71     .12       0
Bank Sta=215.6,247
XS Rating Curve= 0 ,0
Exp/Cntr=0.3,0.1

Type RM Length L Ch R = 1 ,55132.9 ,638.8,723.4,780.3
XS GIS Cut Line= 3
      1864176.55      232425.881     1864366.654      232222.756
       1864395.3      231543.068
#Sta/Elev= 30
       0 1869.58     9.6  1866.5   13.951864.543    28.8 1857.41    57.6 1842.82
    67.2 1838.71    86.3 1832.15   105.5 1826.08   191.9  1800.5     211 1796.01
     259 1786.98   268.6 1784.87   278.2 1781.12   297.6 1771.42   307.4 1767.32
   313.2 1765.81   317.1  1764.8   326.8 1763.82   336.5 1764.38   344.8 1765.71
     356 1767.28   365.7 1767.72     424    1768   579.5 1770.14   598.9 1771.76
   696.1 1787.76   715.5  1790.3   744.7 1791.13     871 1792.95   958.5 1796.71
#Mann= 4 ,-1 , 0
       0    .016       0   13.95     .12       0   313.2    .045       0
   344.8     .12       0
Bank Sta=313.2,344.8
XS Rating Curve= 0 ,0
Exp/Cntr=0.3,0.1

Type RM Length L Ch R = 1 ,54409.5 ,864.3,810.6,753.1
XS GIS Cut Line= 3
     1864168.738      232446.714     1864757.279      232392.027
     1864840.613      231902.443
#Sta/Elev= 30
       0 1877.71    19.4 1870.16    38.8 1863.32   46.31 1860.05    58.1 1854.55
    77.5 1844.67    87.2 1840.16    96.9 1836.43   203.5  1801.3   213.2 1798.85
   300.4 1781.61   329.4 1777.34   368.2 1772.59   377.9 1770.33   398.4 1763.54
     407 1762.08   416.7 1761.71   430.6 1763.26   445.7 1765.49   455.4 1766.18
   513.6  1769.6     562 1773.35   571.7 1773.88   591.1 1773.94   649.5 1778.97
   746.9 1784.71   766.4 1785.61     893 1788.25  972.34 1792.11  1087.7 1797.34
#Mann= 5 ,-1 , 0
       0    .016       0   46.31     .12       0   398.4    .045       0
   430.6     .12       0  972.34     .06       0
Bank Sta=398.4,430.6
XS Rating Curve= 0 ,0
Exp/Cntr=0.3,0.1

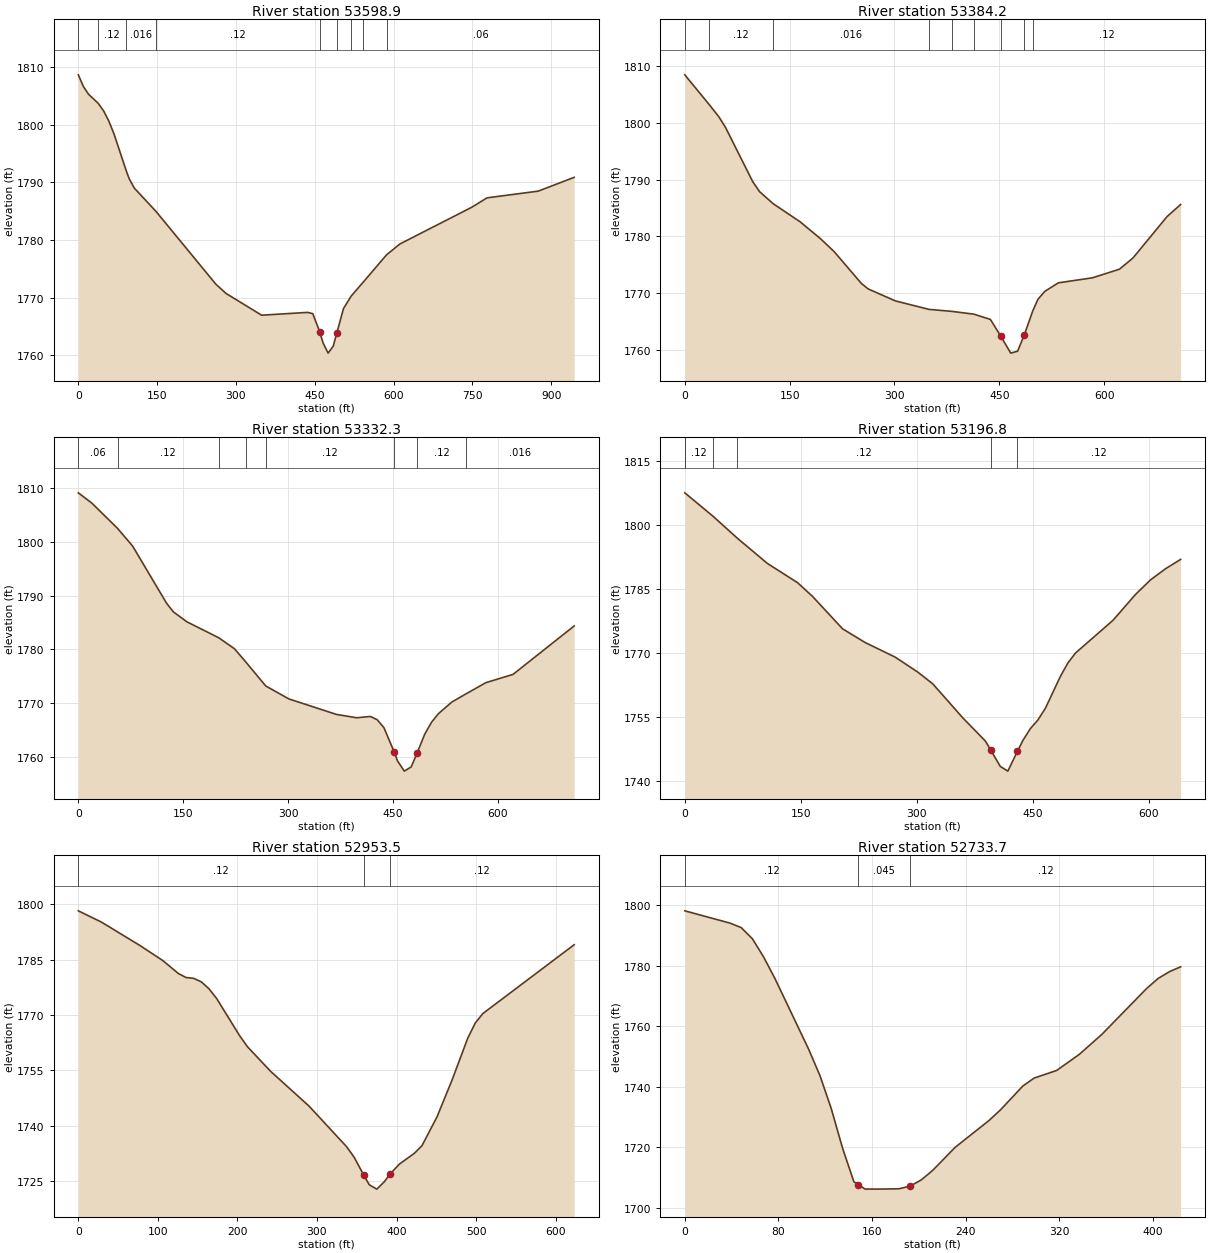
Type RM Length L Ch R = 1 ,53598.9 ,183.4,214.6,245.6
XS GIS Cut Line= 3
     1864918.738       232975.36     1864991.654      232584.735
     1864944.779      232040.464
#Sta/Elev= 30
       0 1808.67     9.7 1806.64    19.4  1805.3   37.821803.732    48.5 1802.36
    58.2 1800.61    67.8 1798.44   91.521791.939    96.9 1790.63   106.6 1789.01
  147.591784.997   261.7 1772.35   281.1 1770.74   348.9 1766.96   436.4 1767.45
   446.2 1767.23  459.34 1764.11   465.7 1762.17   475.4 1760.38   485.2  1761.6
  491.93 1763.86   504.7 1768.12  519.331770.283  542.591772.733  586.671777.437
     612 1779.32   748.6 1785.68   777.8 1787.32   875.4 1788.49   943.7 1790.88
#Mann= 9 ,-1 , 0
       0     .06       0   37.82     .12       0   91.52    .016       0
  147.59     .12       0  459.34    .045       0  491.93     .12       0
  519.33     .06       0  542.59     .12       0  586.67     .06       0
Bank Sta=459.34,491.93
XS Rating Curve= 0 ,0
Exp/Cntr=0.3,0.1

Type RM Length L Ch R = 1 ,53384.2 ,52,51.9,51.9
XS GIS Cut Line= 3
     1864947.383      232985.777     1864996.863       232787.86
       1865332.8      232410.256
#Sta/Elev= 30
       0 1808.48   34.921803.238    48.6 1801.11    58.3 1799.21    97.2 1789.65
   106.9  1787.9  126.361785.775   165.2 1782.56   194.3 1779.58   213.7 1777.32
   252.6 1771.72   262.3 1770.75   301.2 1768.64  349.511767.137  382.19 1766.79
  413.751766.292   437.3 1765.37  452.08 1762.41   466.4 1759.43   476.2 1759.77
   485.9  1762.7  497.97 1766.91   505.3 1768.92     515 1770.31   534.5 1771.82
   583.1  1772.7   621.9 1774.22   641.4 1776.22     690  1783.5   709.4 1785.62
#Mann= 9 ,-1 , 0
       0     .06       0   34.92     .12       0  126.36    .016       0
  349.51     .06       0  382.19    .016       0  413.75     .12       0
  452.08    .045       0   485.9    .016       0  497.97     .12       0
Bank Sta=452.08,485.9
XS Rating Curve= 0 ,0
Exp/Cntr=0.3,0.1

Type RM Length L Ch R = 1 ,53332.3 ,133.1,135.6,138
XS GIS Cut Line= 3
     1864983.842      233022.235     1865033.321      232824.318
     1865369.258      232446.714
#Sta/Elev= 30
       0 1809.16    19.4 1807.24   56.121802.545    77.7 1799.25   126.3  1788.6
     136    1787   155.4 1785.15  200.931782.181   223.4 1780.14  239.351777.712
  268.15 1773.21   301.2  1770.8   369.2 1767.92   398.4 1767.29   417.8 1767.54
   427.6 1766.93   437.3 1765.44   451.8 1760.96   456.7 1759.26   466.4 1757.36
   476.2 1758.14   484.9 1760.78   495.6 1764.24   505.3 1766.45     515 1768.03
   534.5 1770.23  554.361771.716   583.1 1773.83   621.9 1775.36   709.4 1784.38
#Mann= 8 ,-1 , 0
       0     .06       0   56.12     .12       0  200.93     .06       0
  239.35    .016       0  268.15     .12       0   451.8    .045       0
   484.9     .12       0  554.36    .016       0
Bank Sta=451.8,484.9
XS Rating Curve= 0 ,0
Exp/Cntr=0.3,0.1

Type RM Length L Ch R = 1 ,53196.8 ,224.2,243.3,262.3
XS GIS Cut Line= 2
     1864996.863      233025.707     1865451.724      232574.318
#Sta/Elev= 30
       0 1807.53     .651807.436   36.351802.054   67.181797.005   106.8 1790.96
   145.6 1786.48   165.1 1783.24   203.9 1775.64     233 1772.43   271.9    1769
     301  1765.5   320.4 1762.75   359.2 1754.77   388.4 1749.33  395.76  1747.1
   407.8 1743.35   417.5 1742.26   429.8 1746.88   436.9 1749.44   446.6 1752.23
   456.3 1754.24     466 1756.99   485.5 1764.51   495.2 1767.65   504.9 1769.95
   553.4 1777.63   582.6 1783.72     602 1787.13   621.4 1789.74   640.8 1791.92
#Mann= 6 ,-1 , 0
       0     .06       0     .65     .12       0   36.35     .06       0
   67.18     .12       0  395.76    .045       0   429.8     .12       0
Bank Sta=395.76,429.8
XS Rating Curve= 0 ,0
Exp/Cntr=0.3,0.1

Type RM Length L Ch R = 1 ,52953.5 ,225.1,219.7,214.3
XS GIS Cut Line= 4
     1865153.113      233143.763     1865351.029      232931.957
     1865496.863       232890.29     1865621.863      232758.346
#Sta/Elev= 30
       0 1798.24      29 1795.19    77.3 1788.86   106.3 1784.74   125.6 1781.27
   135.3 1780.16   144.9 1779.94   154.6 1778.98   164.3 1777.09   173.9 1774.46
   202.9 1764.34   212.6  1761.4   241.6 1754.75   289.9 1745.32   337.3 1734.28
   346.8 1731.41  358.97 1726.51   365.7 1723.97   375.2 1722.78   384.7 1724.78
  391.38 1726.75   403.6 1729.57   422.6 1732.52   432.1  1734.6   451.1 1742.47
   470.2 1752.57   489.4 1763.64     499 1767.82   508.5 1770.38   623.3 1789.05
#Mann= 3 ,-1 , 0
       0     .12       0  358.97    .045       0  391.38     .12       0
Bank Sta=358.97,391.38
XS Rating Curve= 0 ,0
Exp/Cntr=0.3,0.1

Type RM Length L Ch R = 1 ,52733.7 ,188.7,176.5,164.3
XS GIS Cut Line= 2
     1865289.831      233189.336     1865676.116      233015.724
#Sta/Elev= 30
       0 1798.19    38.5 1794.14    48.1 1792.66    57.8 1788.92    67.4 1782.87
      77 1775.79   105.9 1752.32   115.5 1743.62   125.1 1732.76   134.8 1719.62
   144.4 1708.57  148.23 1707.61     154 1706.14   163.6 1706.12   182.9 1706.23
   192.5 1707.11   202.1  1709.2   211.8 1712.35     231 1719.97   259.9 1728.84
   269.5 1732.29   288.8 1740.25   298.4 1742.86   317.6 1745.38   336.9 1750.68
   356.1 1757.27   394.6 1772.55   404.3 1775.82   413.9 1778.05   423.5 1779.67
#Mann= 3 ,-1 , 0
       0     .12       0  148.23    .045       0   192.5     .12       0
Bank Sta=148.23,192.5
XS Rating Curve= 0 ,0
Exp/Cntr=0.3,0.1

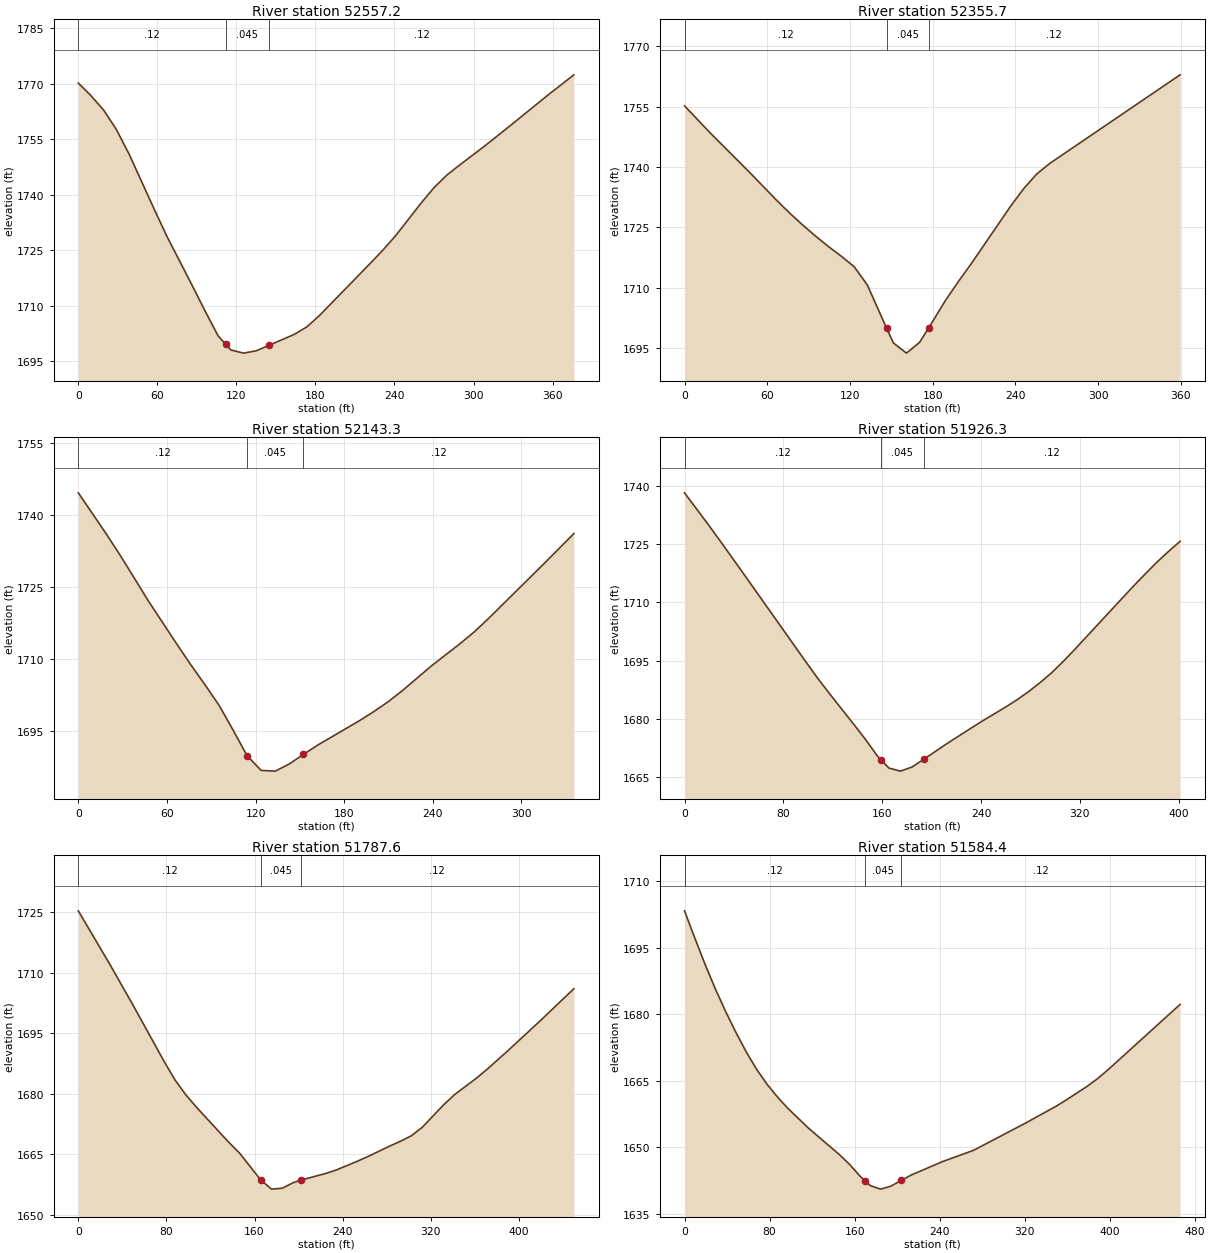
Type RM Length L Ch R = 1 ,52557.2 ,173.9,201.5,229
XS GIS Cut Line= 2
      1865422.21      233362.947     1865697.817       233106.87
#Sta/Elev= 29
       0 1770.14     9.6 1766.76    19.3 1762.83    28.9 1757.61    38.6 1750.94
    57.9 1735.87    67.5  1728.6    86.8 1715.27    96.5 1708.42   106.1 1701.92
  111.92 1699.62   115.8  1698.1   125.4 1697.24     135 1697.86   144.7 1699.34
     164 1702.31   173.6 1704.35   183.3 1707.48   221.9 1721.58   231.5 1725.16
   241.2 1729.08   260.4 1737.84   270.1 1741.95   279.8 1745.32   289.4 1748.01
   308.7 1753.22     328 1758.69   356.9 1767.03   376.2 1772.38
#Mann= 3 ,-1 , 0
       0     .12       0  111.92    .045       0   144.7     .12       0
Bank Sta=111.92,144.7
XS Rating Curve= 0 ,0
Exp/Cntr=0.3,0.1

Type RM Length L Ch R = 1 ,52355.7 ,199.9,212.4,223.7
XS GIS Cut Line= 3
     1865472.123      233438.902     1865680.456      233434.561
     1865808.495      233354.266
#Sta/Elev= 24
       0  1755.2    18.9 1748.39    47.4 1738.62    66.3 1731.93    75.8 1728.72
    85.2 1725.76    94.7 1722.96   104.2 1720.32   113.7 1717.86   123.1 1715.24
   132.6 1710.73   146.6 1699.98   151.6  1696.3     161 1693.79   170.5 1696.45
  177.09 1700.02   189.4 1706.93   198.9 1711.67   208.4 1716.19   236.7 1730.34
   246.2  1734.7   255.6  1738.3     265 1740.91   359.5  1762.9
#Mann= 3 ,-1 , 0
       0     .12       0   146.6    .045       0  177.09     .12       0
Bank Sta=146.6,177.09
XS Rating Curve= 0 ,0
Exp/Cntr=0.3,0.1

Type RM Length L Ch R = 1 ,52143.3 ,217.9,216.9,216
XS GIS Cut Line= 3
     1865487.314      233606.002     1865641.394      233655.915
     1865815.005      233655.915
#Sta/Elev= 25
       0 1744.68      19 1736.09    28.6 1731.55    47.6 1722.08    66.7 1713.17
    76.2 1708.85    85.7 1704.73    95.3 1700.42   104.8 1695.26   114.3 1689.91
   123.8 1686.85   133.4  1686.7   142.9  1688.2   152.4 1690.17     162  1692.1
   190.9 1697.31   200.5 1699.18   210.2 1701.24   219.8 1703.56   239.1 1708.62
   258.4 1713.23   268.1  1715.7   277.7 1718.48   316.3 1730.21   335.6  1736.2
#Mann= 3 ,-1 , 0
       0     .12       0   114.3    .045       0   152.4     .12       0
Bank Sta=114.3,152.4
XS Rating Curve= 0 ,0
Exp/Cntr=0.3,0.1

Type RM Length L Ch R = 1 ,51926.3 ,129.4,138.8,149.3
XS GIS Cut Line= 4
      1865426.55      233762.252     1865532.887      233849.058
     1865632.713      233875.099     1865786.793      233829.527
#Sta/Elev= 30
       0 1738.12    19.6 1729.81    29.4 1725.52      49  1716.8      98  1694.8
   107.8 1690.48   117.7 1686.39   137.3 1678.53   146.6 1674.71     156 1670.56
  159.05 1669.53   165.4 1667.41   174.8 1666.62   184.2 1667.68   193.5 1669.63
   212.3 1673.67   231.1  1677.5   240.4 1679.37   259.3 1682.97   268.8 1684.88
   278.2 1686.98   287.7 1689.34   297.2 1691.91   306.6 1694.82     316 1697.94
   363.3 1714.13   372.8 1717.25   382.2 1720.26   391.7 1723.05   401.1 1725.66
#Mann= 3 ,-1 , 0
       0     .12       0  159.05    .045       0   193.5     .12       0
Bank Sta=159.05,193.5
XS Rating Curve= 0 ,0
Exp/Cntr=0.3,0.1

Type RM Length L Ch R = 1 ,51787.6 ,176.1,203.2,230.2
XS GIS Cut Line= 4
      1865388.79      233836.037     1865459.102      233953.224
     1865542.435      234002.704     1865758.581      233994.891
#Sta/Elev= 30
       0 1725.37    29.3 1711.77    48.8  1702.4    78.1 1687.91    87.8 1683.41
    97.6 1679.72   107.4 1676.62   117.1 1673.72   136.7 1667.92   146.4 1665.26
   165.7 1658.57   175.4 1656.33   185.1 1656.55   194.8  1657.9  201.83 1658.55
   223.9 1660.16   233.6 1661.02   253.2 1663.23   263.1 1664.44   282.7 1667.01
   292.6 1668.22   302.4 1669.58   312.2 1671.66   331.9 1677.31   341.7  1679.8
   361.4 1683.85   371.2 1686.08   390.9  1690.9   420.4 1698.37   449.9 1706.05
#Mann= 3 ,-1 , 0
       0     .12       0   165.7    .045       0  201.83     .12       0
Bank Sta=165.7,201.83
XS Rating Curve= 0 ,0
Exp/Cntr=0.3,0.1

Type RM Length L Ch R = 1 ,51584.4 ,135.6,133.6,131.7
XS GIS Cut Line= 3
     1865285.491      233912.137     1865370.126      234170.383
     1865545.908      234252.848
#Sta/Elev= 30
       0 1703.33     9.7 1697.18    19.4 1691.22    29.1 1685.66    38.8 1680.55
    48.5 1675.83    58.2 1671.44    67.9 1667.54    77.6 1664.21    87.4 1661.34
    97.1 1658.79   116.5 1654.32   145.6 1648.34   155.3 1646.11     165 1643.48
  169.75 1642.41   174.7 1641.34   184.4 1640.55   194.1 1641.22   203.8 1642.54
   213.5 1643.77   242.6 1646.76   271.8 1649.31   320.3 1655.41   349.4 1659.26
   359.1  1660.7   378.6 1663.75   388.3 1665.47     398 1667.44   465.9 1682.22
#Mann= 3 ,-1 , 0
       0     .12       0  169.75    .045       0   203.8     .12       0
Bank Sta=169.75,203.8
XS Rating Curve= 0 ,0
Exp/Cntr=0.3,0.1

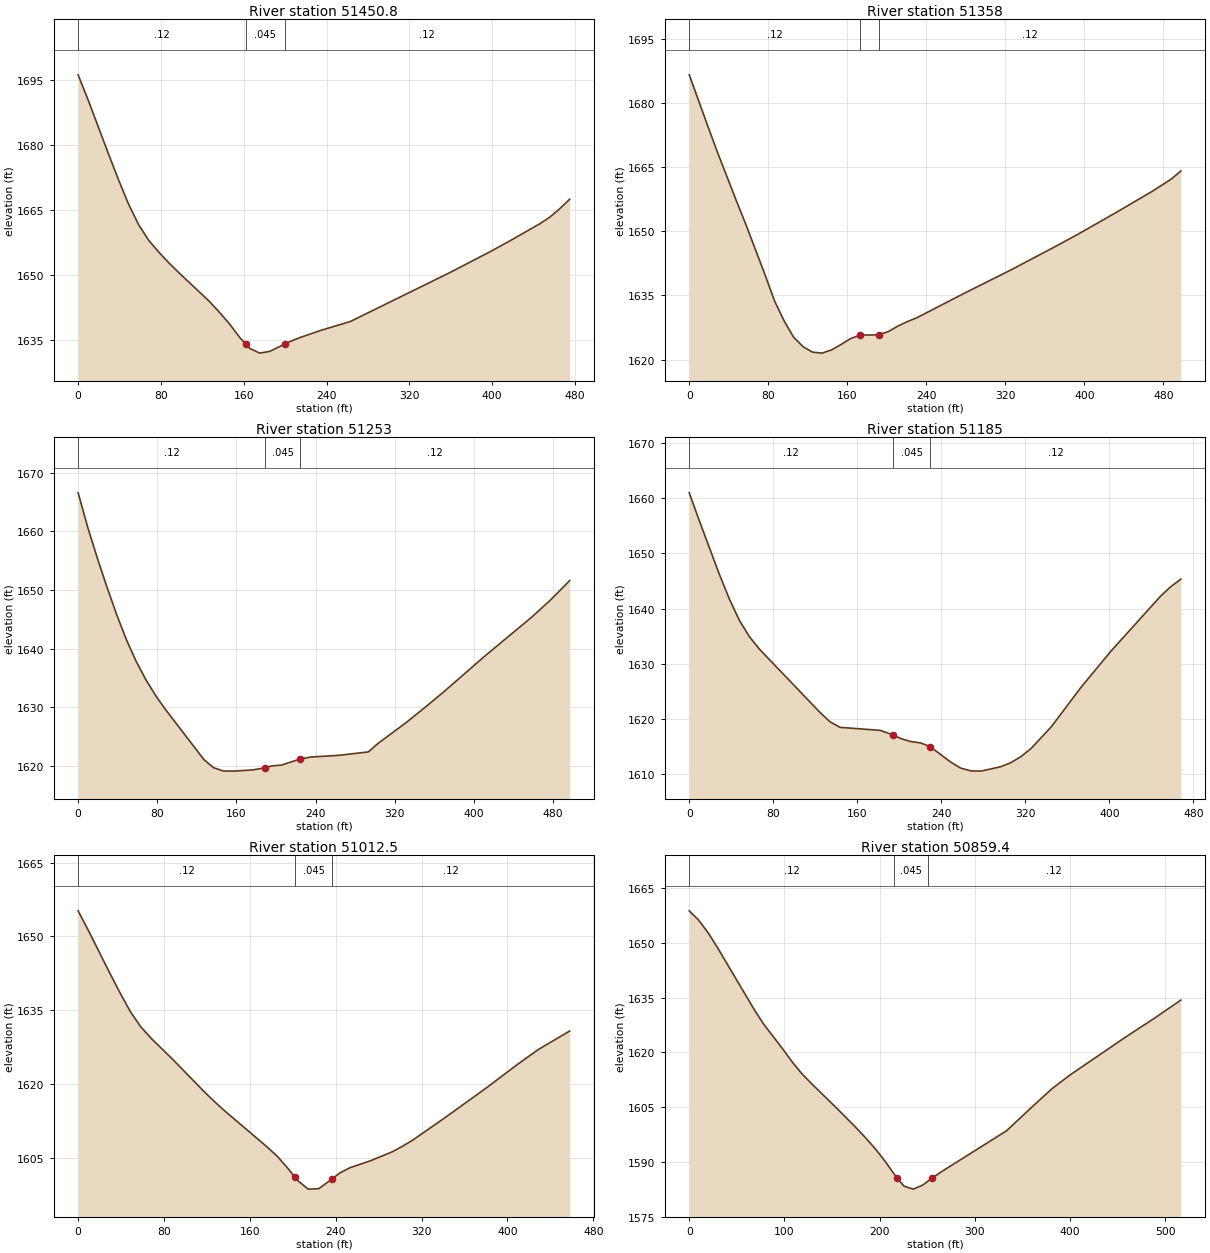
Type RM Length L Ch R = 1 ,51450.8 ,103.6,92.8,81.8
XS GIS Cut Line= 3
     1865159.623      233981.581     1865255.109      234226.807
     1865448.251      234313.612
#Sta/Elev= 30
       0 1696.22     9.8 1690.34    29.2 1678.05      39 1672.01    48.7 1666.38
    58.5  1661.6    68.2 1658.01      78 1655.27    87.7  1652.8    97.5  1650.5
   126.7 1643.94   136.4 1641.43   146.2 1638.74     156 1635.63  161.72 1634.13
   165.7 1633.08   175.4 1631.97   185.2 1632.38  199.85 1634.09   204.7 1634.64
   214.4 1635.57   233.9 1637.18   263.2 1639.29   359.4  1650.6   397.9 1655.37
   417.2  1657.9     446 1661.83   455.7 1663.36   465.3  1665.3   474.9 1667.51
#Mann= 3 ,-1 , 0
       0     .12       0  161.72    .045       0  199.85     .12       0
Bank Sta=161.72,199.85
XS Rating Curve= 0 ,0
Exp/Cntr=0.3,0.1

Type RM Length L Ch R = 1 ,51358   ,98.7,105,111.1
XS GIS Cut Line= 3
     1865033.755      234051.025     1865174.814      234233.317
      1865420.04      234339.654
#Sta/Elev= 29
       0 1686.53    19.2  1674.3    28.8  1668.3      48 1656.94    57.6 1651.42
    76.8  1639.8    86.4 1633.71      96  1629.1   105.6 1625.28   115.2 1623.06
   124.8 1621.77   134.5 1621.54   144.1 1622.29   153.7 1623.55   163.3 1624.94
   172.9 1625.74   192.1 1625.81   201.7 1626.59   211.3 1627.86   220.9  1628.9
   230.5  1629.8   278.2 1635.48     326    1641   373.7  1646.8   392.8  1649.2
     431 1654.21   469.2 1659.38   488.2  1662.2   497.8 1664.07
#Mann= 3 ,-1 , 0
       0     .12       0   172.9    .045       0   192.1     .12       0
Bank Sta=172.9,192.1
XS Rating Curve= 0 ,0
Exp/Cntr=0.3,0.1

Type RM Length L Ch R = 1 ,51253   ,65.6,67.9,70
XS GIS Cut Line= 3
     1864977.829      234093.327     1865116.718      234351.574
     1865318.541      234377.616
#Sta/Elev= 30
       0 1666.56     9.8 1660.64    19.6 1655.35    29.3 1650.43    39.1 1645.75
    48.9 1641.51    58.6 1637.88    68.4 1634.76    78.2 1632.06      88 1629.72
   127.1 1621.13   136.8 1619.75   146.6 1619.19   156.4 1619.16   175.9 1619.36
   189.1 1619.72   195.5 1620.05   205.3 1620.18   223.8  1621.2   234.6 1621.55
   263.9 1621.86   293.2 1622.43   302.9 1623.86     332  1627.5   351.4 1630.14
   370.8 1632.86   409.5 1638.55     458 1645.34   477.3  1648.3   496.7 1651.62
#Mann= 3 ,-1 , 0
       0     .12       0   189.1    .045       0   223.8     .12       0
Bank Sta=189.1,223.8
XS Rating Curve= 0 ,0
Exp/Cntr=0.3,0.1

Type RM Length L Ch R = 1 ,51185   ,163.8,172.5,181.5
XS GIS Cut Line= 3
     1864929.588       234120.47     1865074.988       234432.97
     1865183.495      234491.564
#Sta/Elev= 30
       0 1660.93     9.6 1655.86    28.7 1646.17    38.3 1641.67    47.9  1637.8
    57.4 1634.87      67 1632.61   124.5  1621.2     134 1619.51   143.6  1618.5
   181.9 1617.95   194.4 1617.11   201.1  1616.5   210.6 1615.94   220.2 1615.69
   229.2 1615.03   248.9 1612.22   258.5 1611.12   268.1 1610.63   277.6 1610.58
   296.8 1611.39   306.4 1612.13     316 1613.24   325.5 1614.69   344.7 1618.61
   373.1 1625.78   401.6 1632.32     449 1642.29   458.5 1643.96     468 1645.31
#Mann= 3 ,-1 , 0
       0     .12       0   194.4    .045       0   229.2     .12       0
Bank Sta=194.4,229.2
XS Rating Curve= 0 ,0
Exp/Cntr=0.3,0.1

Type RM Length L Ch R = 1 ,51012.5 ,149.1,153.1,157.2
XS GIS Cut Line= 3
     1864818.911      234170.383     1864877.505      234456.841
      1864964.31        234597.9
#Sta/Elev= 30
       0 1655.19     9.8  1651.1    29.2 1642.67      39 1638.54    48.7  1634.7
    58.5 1631.59    68.2 1629.25    87.7  1625.1     117 1618.55   126.7  1616.5
   136.4 1614.57   175.4 1607.34   185.2  1605.4   194.9    1603     202 1601.09
   204.7 1600.36   214.4 1598.64   224.2 1598.73   236.9 1600.75   243.7  1601.9
   253.4    1603   272.9 1604.44   292.4  1606.2   302.1 1607.33   311.9 1608.62
   341.1 1613.05   380.1 1619.17   409.3 1623.97   428.8 1627.01     458 1630.77
#Mann= 3 ,-1 , 0
       0     .12       0     202    .045       0   236.9     .12       0
Bank Sta=202,236.9
XS Rating Curve= 0 ,0
Exp/Cntr=0.3,0.1

Type RM Length L Ch R = 1 ,50859.4 ,190.9,209.7,229.8
XS GIS Cut Line= 3
     1864693.043      234189.914     1864723.425      234521.946
     1864831.932      234669.515
#Sta/Elev= 30
       0 1658.76     9.8 1656.23    19.6 1652.85    29.4 1648.82    68.6  1631.6
    78.4 1627.68    98.1 1621.01   107.9  1617.5   117.7 1614.38   127.5 1611.73
   156.9 1604.26   176.5 1599.09   186.3 1596.36   196.1 1593.45   205.9 1590.19
   215.4 1586.68  218.77 1585.54   225.6 1583.43   235.4  1582.6   245.2 1583.68
   250.4 1584.69     255 1585.58   264.8 1587.33   333.4 1598.56   362.3  1605.6
   381.6 1610.17   400.9 1613.97   458.7 1624.23   487.7 1629.17   516.6 1634.33
#Mann= 3 ,-1 , 0
       0     .12       0   215.4    .045       0   250.4     .12       0
Bank Sta=218.77,255
XS Rating Curve= 0 ,0
Exp/Cntr=0.3,0.1

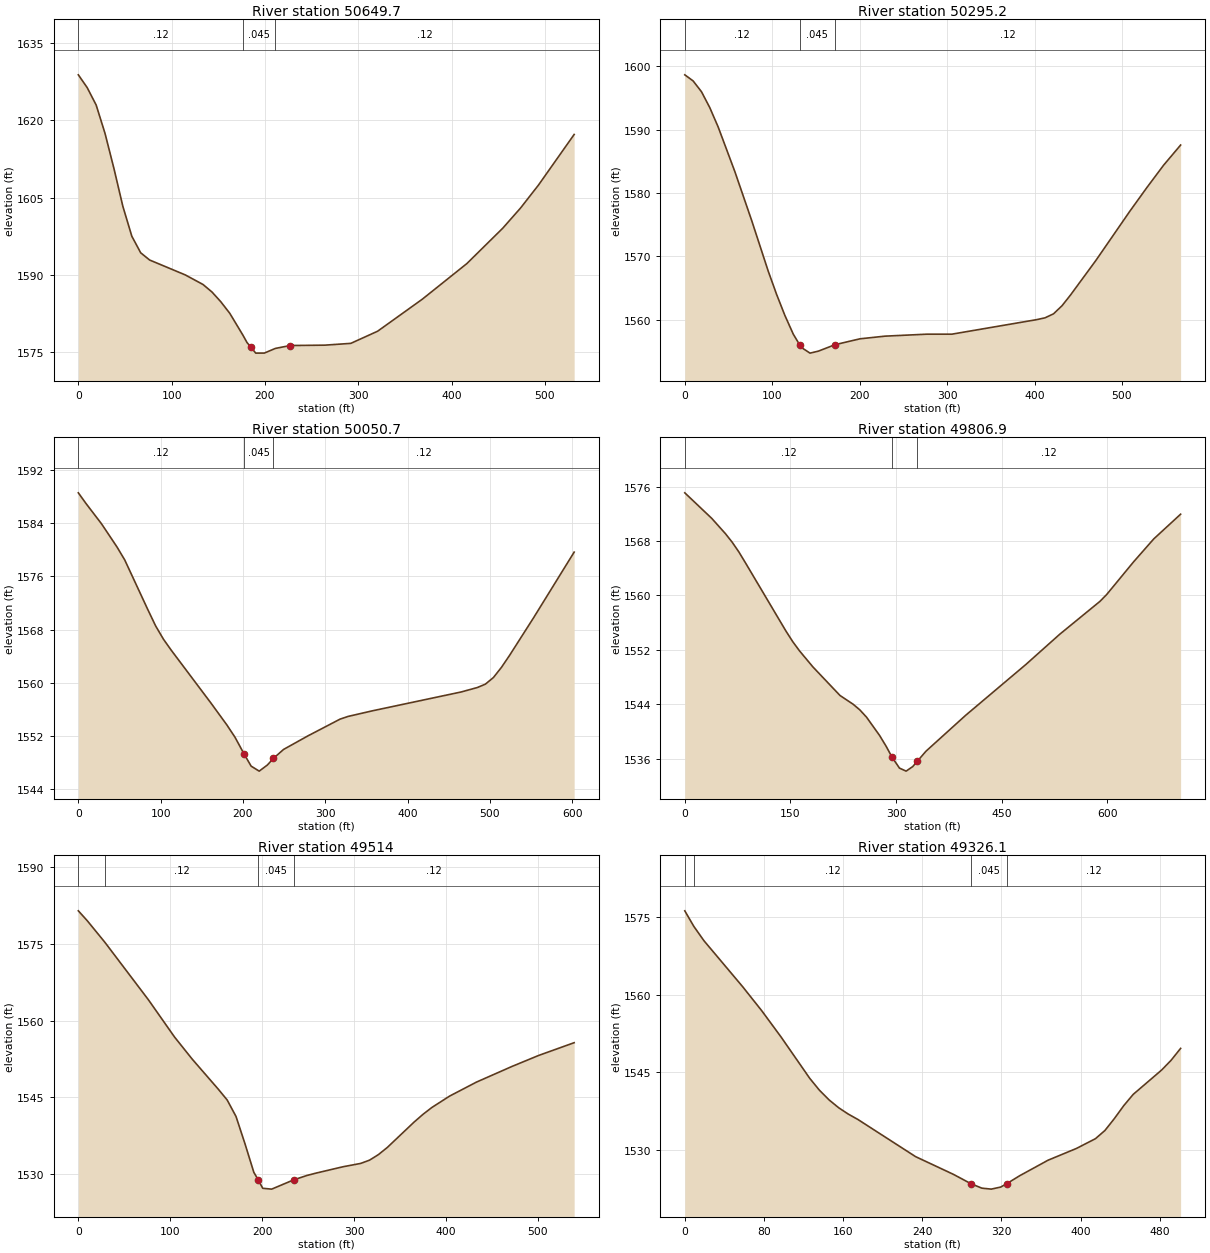
Type RM Length L Ch R = 1 ,50649.7 ,373.5,354.5,334
XS GIS Cut Line= 4
     1864555.164       234228.47     1864523.483       234387.61
     1864467.625      234504.687     1864584.461      234713.496
#Sta/Elev= 30
       0 1628.87     9.5 1626.38    19.1    1623    28.6 1617.48    38.2 1610.62
    47.7  1603.3    57.3 1597.49    66.8 1594.26    76.4 1592.85   114.5 1589.96
   133.6 1588.09   143.2 1586.63   152.7 1584.73   162.3 1582.48   176.1 1578.32
   180.8 1576.79  184.66 1575.96   190.1 1574.74   199.3 1574.75   211.2 1575.66
   227.1 1576.22   264.2 1576.29     292 1576.64   320.7    1579   368.6 1585.23
   416.4 1592.17   454.7 1599.02   473.8 1602.95     493 1607.41   531.3 1617.27
#Mann= 3 ,-1 , 0
       0     .12       0   176.1    .045       0   211.2     .12       0
Bank Sta=184.66,227.1
XS Rating Curve= 0 ,0
Exp/Cntr=0.3,0.1

Type RM Length L Ch R = 1 ,50295.2 ,288.2,244.5,200.5
XS GIS Cut Line= 3
     1864151.735       234243.01     1864182.985      234546.829
     1864415.624      234666.621
#Sta/Elev= 30
       0 1598.64     9.5 1597.68    19.1 1595.97    28.6 1593.46    38.2  1590.4
    57.3 1583.35    76.4 1575.69    95.4 1567.67     105 1563.99   114.5 1560.66
   124.1 1557.71  131.24 1556.06   133.6 1555.59   143.2 1554.72   152.7 1555.03
   171.8 1556.05   200.4 1556.98   229.1  1557.4   276.8 1557.71   305.4 1557.71
   402.3    1560     412 1560.29   421.7 1560.92   431.4 1562.19   441.1 1563.88
   470.2 1569.35   508.9 1577.09   528.3 1580.81   547.7 1584.39   567.1 1587.56
#Mann= 3 ,-1 , 0
       0     .12       0  131.24    .045       0   171.8     .12       0
Bank Sta=131.24,171.8
XS Rating Curve= 0 ,0
Exp/Cntr=0.3,0.1

Type RM Length L Ch R = 1 ,50050.7 ,222.5,243.8,265.1
XS GIS Cut Line= 3
     1863876.561      234391.881     1863921.593      234515.476
     1864369.692        234660.4
#Sta/Elev= 30
       0  1588.6     9.4 1586.98    28.2 1583.93      47 1580.44    56.4 1578.49
    84.6 1570.97      94 1568.54   103.4 1566.56   112.8 1564.91     161 1556.96
   180.6 1553.62   190.4 1551.78   201.5 1549.24     210 1547.43   219.8 1546.68
   229.7  1547.6   237.1  1548.6   249.3 1549.94   278.7 1551.97     318 1554.51
   327.8 1554.92   357.2 1555.76   465.1  1558.6   484.8 1559.27   494.6 1559.78
   504.4 1560.78   514.2 1562.32     524 1564.11   553.4 1569.82   602.5 1579.67
#Mann= 3 ,-1 , 0
       0     .12       0   201.5    .045       0   237.1     .12       0
Bank Sta=201.5,237.1
XS Rating Curve= 0 ,0
Exp/Cntr=0.3,0.1

Type RM Length L Ch R = 1 ,49806.9 ,325.4,292.9,260.3
XS GIS Cut Line= 4
     1863852.256      234463.062     1863828.026      234682.102
     1863953.894      234834.012     1864230.728      234907.506
#Sta/Elev= 30
       0 1575.09    38.3 1571.33    57.5 1569.11    67.1 1567.86    76.6 1566.43
    86.2 1564.79   143.7 1554.76   153.3 1553.21   162.9 1551.86     182 1549.49
   220.4  1545.3   239.2    1544   248.6 1543.18     258 1542.12   276.7 1539.41
   286.1  1537.8   294.4 1536.21   304.9 1534.62   314.3 1534.18   323.7 1534.85
   330.2 1535.63   342.5 1537.11   398.9 1542.39   484.5 1549.87   532.2 1554.28
   589.5 1559.13   599.1 1560.14   637.2 1564.93   665.9 1568.31   704.1 1571.95
#Mann= 3 ,-1 , 0
       0     .12       0   294.4    .045       0   330.2     .12       0
Bank Sta=294.4,330.2
XS Rating Curve= 0 ,0
Exp/Cntr=0.3,0.1

Type RM Length L Ch R = 1 ,49514   ,169.9,187.9,205.8
XS GIS Cut Line= 3
     1863525.508      234882.189     1863662.227      234968.994
     1864039.831      234975.505
#Sta/Elev= 30
       0 1581.49     9.5  1579.6   28.89 1575.33    76.2 1564.09   104.8 1556.76
   123.8 1552.48   152.4 1546.55     162 1544.45   171.6 1541.23   181.3 1535.92
     191 1530.29   195.8  1528.8   200.7 1527.16   210.4    1527  234.43 1528.82
   249.1 1529.69   258.8 1530.14   287.8 1531.37   307.2 1532.03   316.9 1532.67
   326.6 1533.76   336.2 1535.15   365.3 1540.11     375 1541.63   384.7 1542.98
     404 1545.21   433.1 1547.94   471.8 1551.01   500.9 1553.17   539.6 1555.67
#Mann= 4 ,-1 , 0
       0     .06       0   28.89     .12       0   195.8    .045       0
  234.43     .12       0
Bank Sta=195.8,234.43
XS Rating Curve= 0 ,0
Exp/Cntr=0.3,0.1

Type RM Length L Ch R = 1 ,49326.1 ,226.5,263,299.6
XS GIS Cut Line= 3
     1863508.642      234950.592     1863673.534      235115.484
     1863909.094      235243.079
#Sta/Elev= 30
       0 1576.26     9.21573.225    19.4 1570.46    58.3  1561.6    77.7 1556.92
    97.2 1551.84   126.3  1543.8     136 1541.52   145.8 1539.63   155.5 1538.11
   165.2 1536.88   174.9 1535.84   233.2 1528.64   271.5  1525.2   289.2 1523.39
   300.2 1522.53   309.7 1522.34   319.3 1522.74   325.4  1523.4   338.4 1524.93
   367.1 1527.94   395.8 1530.22     415 1532.11   424.6  1533.7   434.1    1536
   443.7 1538.53   453.2  1540.7     482 1545.43   491.5 1547.31   501.1 1549.61
#Mann= 4 ,-1 , 0
       0     .06       0     9.2     .12       0   289.2    .045       0
   325.4     .12       0
Bank Sta=289.2,325.4
XS Rating Curve= 0 ,0
Exp/Cntr=0.3,0.1