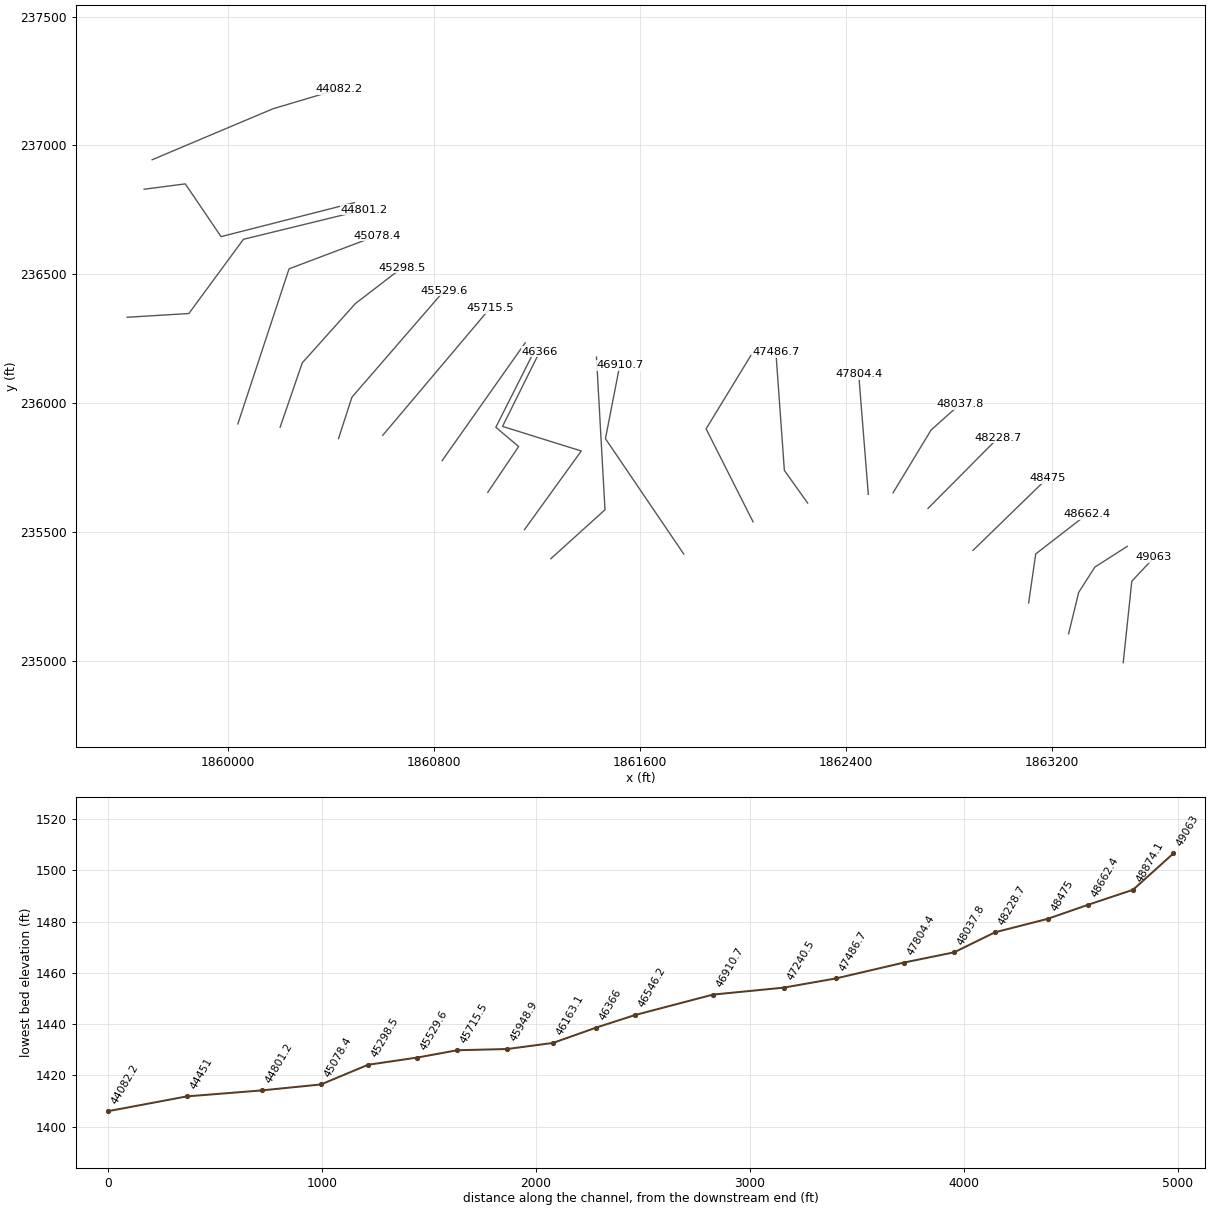
HEC-RAS study TETERCK.prj: TETERCK

--- TETERCK.g01 (geometry) --- (continued)

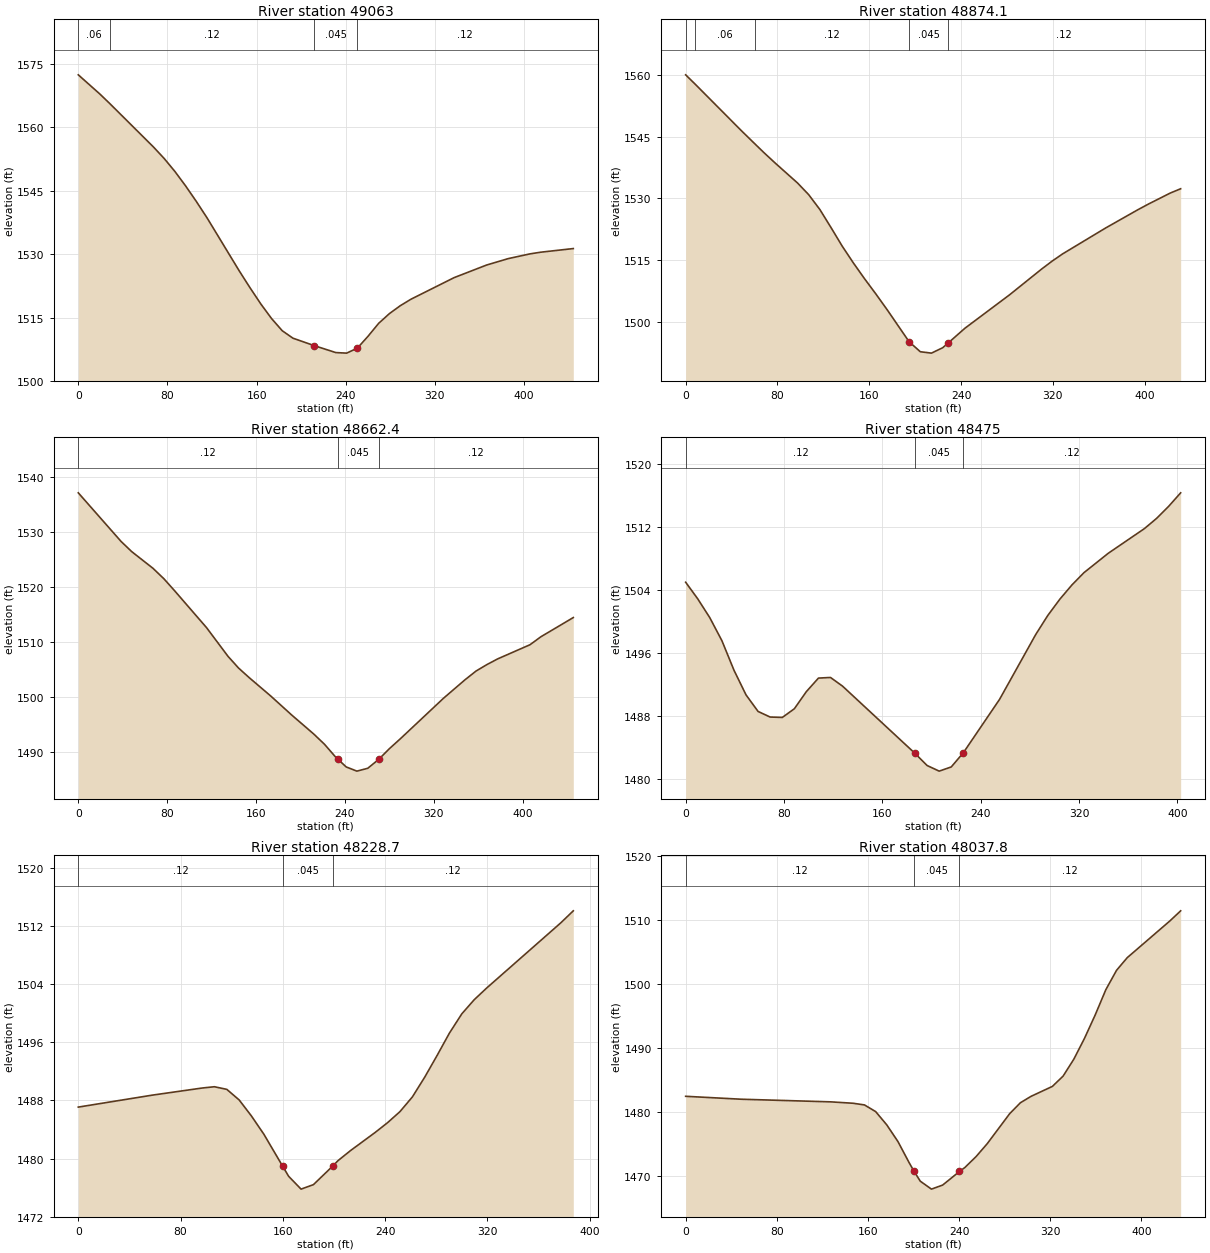
Type RM Length L Ch R = 1 ,49063   ,206.6,188.9,171.2
XS GIS Cut Line= 3
     1863475.271      234991.815     1863508.642      235307.858
     1863595.014      235400.119
#Sta/Elev= 30
       0 1572.47    19.3 1567.94   28.491565.604    67.4  1555.4      77 1552.68
    86.7 1549.59    96.3 1546.17   105.9  1542.5   115.6 1538.58   144.4 1526.06
   154.1 1522.05   163.7 1518.25   173.4 1514.77     183 1511.88   192.6 1510.11
   211.9 1508.33   231.1  1506.7   240.8 1506.57   250.4 1507.74     260 1510.56
   269.6 1513.64   279.3 1515.95   288.9 1517.79   298.5 1519.33   337.2 1524.44
   366.4 1527.43   385.8 1528.95   405.3 1530.07     415 1530.47   444.2 1531.33
#Mann= 4 ,-1 , 0
       0     .06       0   28.49     .12       0   211.9    .045       0
   250.4     .12       0
Bank Sta=211.9,250.4
XS Rating Curve= 0 ,0
Exp/Cntr=0.3,0.1

Type RM Length L Ch R = 1 ,48874.1 ,224.4,211.7,198.8
XS GIS Cut Line= 4
     1863263.267      235103.706     1863302.527      235264.672
     1863365.343      235362.822     1863490.975      235443.305
#Sta/Elev= 30
       0 1560.02    8.331557.742    48.7 1546.41   60.391543.229    68.2 1541.12
      78 1538.59    97.5 1533.74   107.2 1530.91     117 1527.28   126.7  1522.9
   136.4 1518.41   146.2  1514.3   155.9 1510.48   165.7  1506.8   175.4 1503.03
   194.8 1495.15   204.5 1492.74   214.2  1492.4     224 1493.71   228.4 1494.77
   243.4 1498.45   282.2 1506.55   310.2 1512.82   319.5 1514.78   328.8 1516.56
   366.1 1522.82   394.1 1527.24   403.4 1528.63   422.1 1531.26   431.4 1532.34
#Mann= 5 ,-1 , 0
       0     .12       0    8.33     .06       0   60.39     .12       0
   194.8    .045       0   228.4     .12       0
Bank Sta=194.8,228.4
XS Rating Curve= 0 ,0
Exp/Cntr=0.3,0.1

Type RM Length L Ch R = 1 ,48662.4 ,183.1,187.4,191.6
XS GIS Cut Line= 3
      1863108.19      235223.449     1863135.672       235413.86
     1863335.898      235568.937
#Sta/Elev= 30
       0 1537.18    38.5 1528.33    48.1 1526.47    67.3 1523.42      77 1521.54
    86.6 1519.37   115.4 1512.64   134.7 1507.42   144.3 1505.26   153.9 1503.51
   173.2 1500.18   192.4 1496.66   211.9 1493.26   221.6 1491.39   231.4 1489.11
   233.7 1488.67   241.1 1487.26   250.8 1486.49   260.6 1487.01   270.4 1488.62
     280 1490.57   289.8 1492.36   328.8 1499.77   348.2 1503.14     358 1504.71
   367.7 1505.88   377.5 1506.93   406.7 1509.52   416.4 1510.96   445.6 1514.46
#Mann= 3 ,-1 , 0
       0     .12       0   233.7    .045       0   270.4     .12       0
Bank Sta=233.7,270.4
XS Rating Curve= 0 ,0
Exp/Cntr=0.3,0.1

Type RM Length L Ch R = 1 ,48475   ,245.5,246.3,246.7
XS GIS Cut Line= 2
      1862892.26      235427.601     1863180.821       235708.31
#Sta/Elev= 30
       0 1505.01     9.8 1502.91    19.6 1500.52    29.5 1497.59    39.3 1493.85
    49.1 1490.72    58.9 1488.62    68.7 1487.91    78.6 1487.86    88.4 1488.96
    98.2 1491.14     108 1492.85   117.8 1492.93   127.6 1491.83   186.6 1483.29
   196.4 1481.76   206.2 1481.05     216 1481.58   225.8 1483.37   255.3 1490.15
   284.8  1498.4   294.6 1500.81   304.4 1502.87   314.2 1504.67     324 1506.23
   343.7 1508.68   373.1 1511.81   382.9 1513.09   392.8 1514.63   402.6 1516.35
#Mann= 3 ,-1 , 0
       0     .12       0   186.6    .045       0   225.8     .12       0
Bank Sta=186.6,225.8
XS Rating Curve= 0 ,0
Exp/Cntr=0.3,0.1

Type RM Length L Ch R = 1 ,48228.7 ,182,190.9,199.9
XS GIS Cut Line= 2
     1862717.553       235590.53      1862990.41       235865.35
#Sta/Elev= 27
       0 1487.08    58.1 1488.73    96.8  1489.7   106.5 1489.88   116.2 1489.52
   125.9 1488.06   135.5 1485.85   145.2 1483.35  159.94 1478.94   164.6 1477.56
   174.3  1475.8     184 1476.42   198.9 1478.94   203.3 1479.73     213  1481.1
   232.4 1483.61     242 1484.94   251.7 1486.46   261.4 1488.48   271.1 1491.21
   280.8  1494.2   290.4 1497.26   300.1 1499.91   309.8 1501.85   319.5 1503.45
   377.6 1512.43   387.3 1514.07
#Mann= 3 ,-1 , 0
       0     .12       0  159.94    .045       0   198.9     .12       0
Bank Sta=159.94,198.9
XS Rating Curve= 0 ,0
Exp/Cntr=0.3,0.1

Type RM Length L Ch R = 1 ,48037.8 ,209.8,233.4,256.8
XS GIS Cut Line= 3
     1862582.106      235651.383     1862729.331      235894.795
     1862841.222      235994.908
#Sta/Elev= 30
       0 1482.51      49 1482.05   127.5 1481.64   147.1 1481.42     157 1481.16
   166.8 1480.12   176.6 1478.04   186.4 1475.43   196.2 1472.14  200.44 1470.81
     206 1469.24   215.8    1468   225.6 1468.63  240.42 1470.76   245.2 1471.39
     255 1473.09   264.8 1475.11   284.5  1479.8   293.9  1481.5   303.2  1482.5
     322 1484.06   331.4 1485.67   340.8 1488.31   350.2 1491.58   359.5  1495.2
   368.9 1499.17   378.3  1502.2   387.7 1504.18   425.2 1509.93   434.6  1511.5
#Mann= 3 ,-1 , 0
       0     .12       0  200.44    .045       0  240.42     .12       0
Bank Sta=200.44,240.42
XS Rating Curve= 0 ,0
Exp/Cntr=0.3,0.1

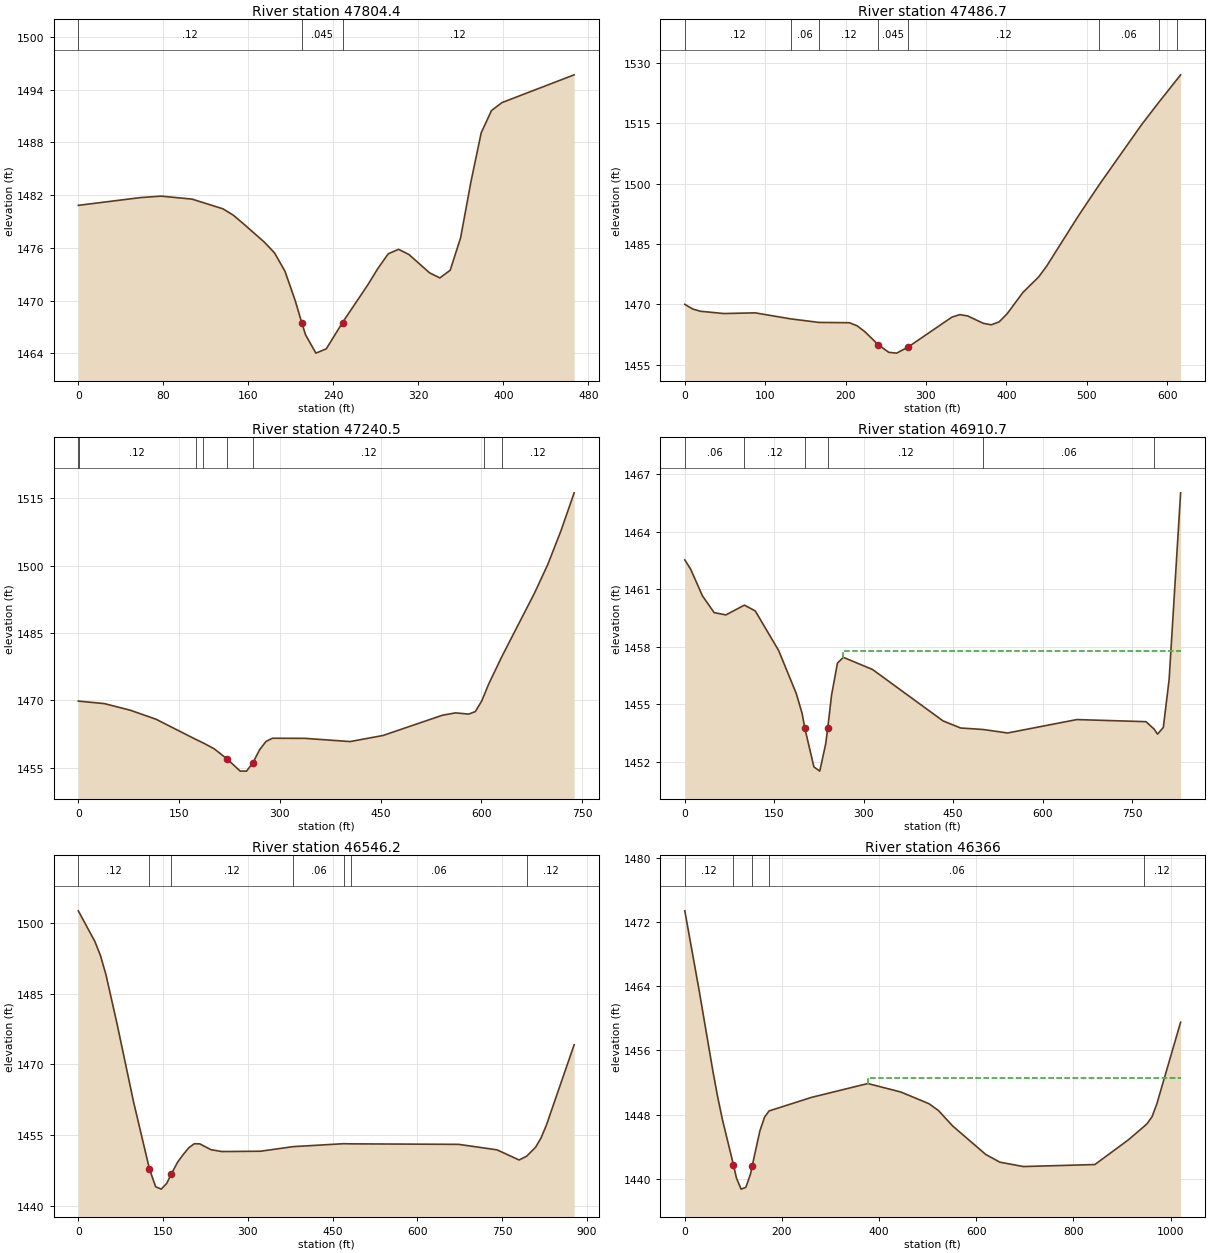
Type RM Length L Ch R = 1 ,47804.4 ,318.1,317.7,317.3
XS GIS Cut Line= 2
      1862485.92      235645.494     1862448.623      236110.724
#Sta/Elev= 30
       0 1480.83    58.3 1481.71    77.8 1481.88     107 1481.54   136.1 1480.44
   145.8 1479.72   155.6 1478.72     175 1476.66   184.7 1475.42   194.5 1473.34
   204.2 1469.98  210.25 1467.51   213.9 1466.11   223.6 1464.03   233.4 1464.52
  248.66 1467.51   272.3 1471.76     282 1473.66   291.7 1475.32   301.4 1475.83
   311.2 1475.24   330.6 1473.16   340.3 1472.58     350 1473.45   359.8 1477.13
   369.5 1483.48   379.2 1489.07   388.9 1491.61   398.7 1492.51   466.7 1495.67
#Mann= 3 ,-1 , 0
       0     .12       0  210.25    .045       0  248.66     .12       0
Bank Sta=210.25,248.66
XS Rating Curve= 0 ,0
Exp/Cntr=0.3,0.1

Type RM Length L Ch R = 1 ,47486.7 ,231.2,246.2,261.2
XS GIS Cut Line= 3
     1862250.436      235611.444     1862160.158       235738.18
     1862127.172      236198.249
#Sta/Elev= 30
       0 1469.97     9.7 1468.82    19.4 1468.25    48.6 1467.68    87.5 1467.85
  131.691466.357  166.951465.472   204.7  1465.4   214.5 1464.62   224.3 1463.11
   240.4 1459.98   253.7 1458.04   263.6 1457.84   278.1 1459.39   332.2 1466.78
   342.1 1467.41   351.9 1467.08   371.5 1465.24   381.3 1464.88   391.1 1465.62
     401 1467.63   420.6 1472.92   440.2 1476.78     450 1479.42   489.3 1491.86
  515.761499.762   567.8 1514.51  589.59 1520.17  611.96  1525.8   616.8 1527.02
#Mann= 8 ,-1 , 0
       0     .12       0  131.69     .06       0  166.95     .12       0
   240.4    .045       0   278.1     .12       0  515.76     .06       0
  589.59     .12       0  611.96     .06       0
Bank Sta=240.4,278.1
XS Rating Curve= 0 ,0
Exp/Cntr=0.3,0.1

Type RM Length L Ch R = 1 ,47240.5 ,324.8,329.7,334.5
XS GIS Cut Line= 3
     1862038.631      235538.527     1861856.339      235899.638
      1862029.95       236184.36
#Sta/Elev= 30
       0 1469.81     .351469.808    38.5 1469.26      77  1467.8   115.6 1465.78
  174.611461.304  186.211460.479   202.3 1459.18   221.5 1456.92   240.8 1454.24
   250.4 1454.22     260 1456.12   269.7 1458.95   279.3 1460.83   288.9 1461.54
   337.1 1461.52   404.5  1460.8   453.6 1462.16   541.8 1466.66   561.4 1467.19
   581.1 1466.92   590.9 1467.48   600.7 1469.92  603.94 1471.11   610.5 1473.52
  630.191479.667   679.1  1493.9   698.8 1500.25   718.4 1507.76     738 1516.19
#Mann= 8 ,-1 , 0
       0     .06       0     .35     .12       0  174.61     .06       0
  186.21     .12       0   221.5    .045       0     260     .12       0
  603.94     .06       0  630.19     .12       0
Bank Sta=221.5,260
XS Rating Curve= 0 ,0
Exp/Cntr=0.3,0.1

Type RM Length L Ch R = 1 ,46910.7 ,419.4,364.5,308.5
XS GIS Cut Line= 3
     1861769.533      235413.527     1861465.714      235861.444
     1861521.269      236146.166
#Sta/Elev= 30
       0 1462.54     9.8 1462.06    29.5 1460.67    49.2 1459.79    68.9 1459.67
   99.911460.181   118.1 1459.88   157.4 1457.81     187 1455.56   196.8 1454.52
  201.08 1453.78   216.5 1451.74   226.3 1451.52   236.2 1452.94  239.62 1453.75
     246 1455.47   255.9 1457.15   265.7 1457.46   314.9 1456.82     433 1454.14
   462.5 1453.77   500.51453.691   541.2 1453.51   657.3 1454.21   773.3  1454.1
  786.951453.709   792.6 1453.45   802.3  1453.8     812 1456.29   831.3 1466.04
#Mann= 6 ,-1 , 0
       0     .06       0   99.91     .12       0  201.08    .045       0
  239.62     .12       0   500.5     .06       0  786.95     .12       0
#XS Ineff= 2 , 0
                          265.22         1457.81
Permanent Ineff=
       F       F
Bank Sta=201.08,239.62
XS Rating Curve= 0 ,0
Exp/Cntr=0.3,0.1

Type RM Length L Ch R = 1 ,46546.2 ,172,180.2,187.8
XS GIS Cut Line= 3
      1861253.83      235395.202     1861463.978      235585.402
     1861430.913      236178.188
#Sta/Elev= 30
       0 1502.58    29.3 1496.07    39.1 1493.11    48.9 1489.02    68.4 1478.66
    97.7 1462.05   125.9 1447.78   136.8 1444.05   146.6 1443.54   156.4 1444.76
   164.3 1446.72   175.9 1449.31   185.7  1450.9   195.5 1452.32   205.2 1453.17
     215 1453.14   234.6 1451.91   254.1 1451.51   322.4 1451.58  379.841452.552
  469.391453.177  481.651453.146   672.8 1453.04   740.9 1451.87   779.8 1449.72
  793.131450.521     809 1452.43   818.8 1454.44   828.5 1457.25   877.2 1474.18
#Mann= 7 ,-1 , 0
       0     .12       0   125.9    .045       0   164.3     .12       0
  379.84     .06       0  469.39     .12       0  481.65     .06       0
  793.13     .12       0
Bank Sta=125.9,164.3
XS Rating Curve= 0 ,0
Exp/Cntr=0.3,0.1

Type RM Length L Ch R = 1 ,46366   ,201.7,202.9,204.1
XS GIS Cut Line= 4
     1861151.399      235508.049     1861371.885      235813.605
      1861066.33      235909.091     1861210.427      236199.022
#Sta/Elev= 30
       0 1473.44      29 1463.68      58 1453.36    67.6 1450.22    77.3 1447.41
   100.1 1441.73   106.3 1440.07   115.9 1438.68   125.6  1438.9   135.3 1440.57
   138.6 1441.54   154.6 1445.96   164.2 1447.67   173.51448.447   260.9 1450.14
   376.8 1451.87   444.7 1450.81   502.9 1449.34   522.3 1448.49   551.4 1446.57
   619.3 1443.02   648.4 1442.05   696.9  1441.5   844.1 1441.75   912.8 1444.82
  944.761446.474     952 1446.88   961.8 1447.72   971.6  1449.3  1020.7 1459.53
#Mann= 5 ,-1 , 0
       0     .12       0   100.1    .045       0   138.6     .12       0
   173.5     .06       0  944.76     .12       0
#XS Ineff= 2 , 0
                          377.71          1452.5
Permanent Ineff=
       F       F
Bank Sta=100.1,138.6
XS Rating Curve= 0 ,0
Exp/Cntr=0.3,0.1

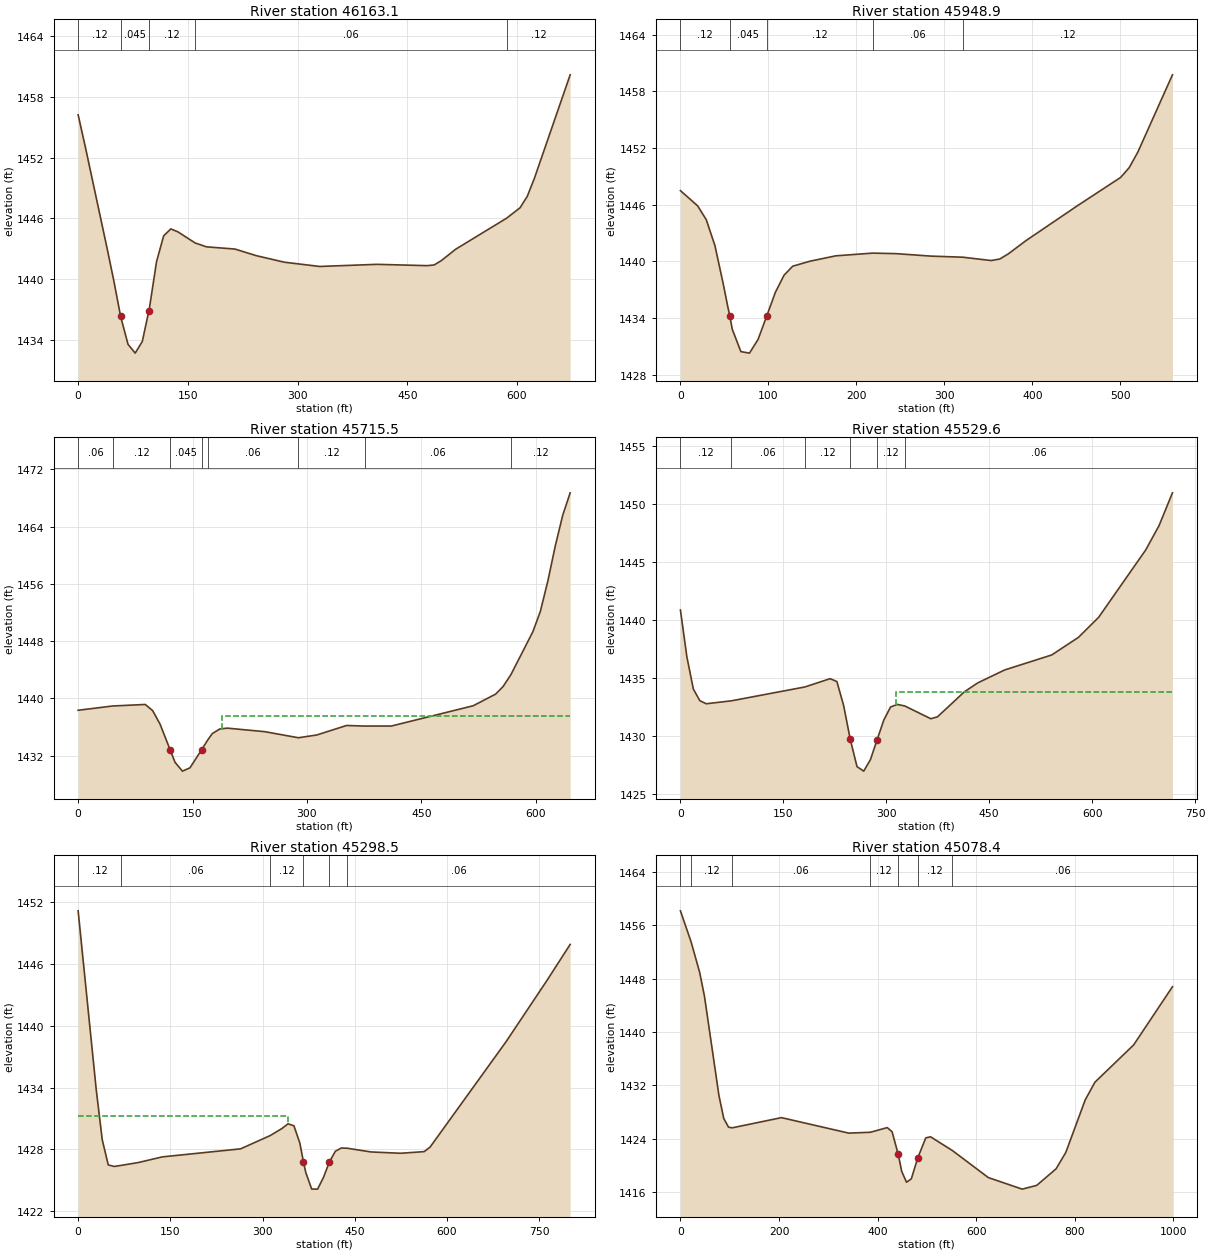
Type RM Length L Ch R = 1 ,46163.1 ,215,214.2,213.4
XS GIS Cut Line= 4
     1861009.117       235653.11      1861128.83      235830.966
     1861040.288      235905.619     1861194.542      236211.435
#Sta/Elev= 30
       0 1456.22     9.8 1453.06      39 1443.23    48.7 1439.86    58.1  1436.3
    68.2 1433.55      78 1432.68    87.7 1433.83    96.8 1436.89    97.4 1437.09
   107.2 1441.72   116.9 1444.26   126.7 1444.95   136.4 1444.66  159.851443.567
   175.4 1443.18   214.4 1442.96   243.4 1442.31     282 1441.66   330.2 1441.24
   408.5 1441.45     477 1441.32   486.8 1441.39   496.6 1441.82   516.1 1442.94
  586.011446.018   604.2 1447.04     614 1448.16   623.8 1449.95   672.7 1460.17
#Mann= 5 ,-1 , 0
       0     .12       0    58.1    .045       0    96.8     .12       0
  159.85     .06       0  586.01     .12       0
Bank Sta=58.1,96.8
XS Rating Curve= 0 ,0
Exp/Cntr=0.3,0.1

Type RM Length L Ch R = 1 ,45948.9 ,236.8,233.5,230.2
XS GIS Cut Line= 2
     1860832.033      235776.374     1861154.177       236233.57
#Sta/Elev= 30
       0  1447.5    19.6 1445.89    29.4 1444.42    39.2 1441.69    49.1 1437.44
    53.8 1435.23   56.16 1434.23    58.9 1432.84    68.7 1430.46    78.5  1430.3
    88.3 1431.76    98.1 1434.23   107.9 1436.73   117.8 1438.55   127.6  1439.5
   147.2 1440.03   176.6  1440.6  218.511440.887   245.3 1440.83   284.6 1440.57
  320.841440.455   353.2  1440.1     363 1440.26   372.9 1440.82   392.5 1442.19
   451.4 1445.91   500.4  1448.9   510.2 1449.94     520 1451.59   559.3 1459.76
#Mann= 5 ,-1 , 0
       0     .12       0   56.16    .045       0    98.1     .12       0
  218.51     .06       0  320.84     .12       0
Bank Sta=56.16,98.1
XS Rating Curve= 0 ,0
Exp/Cntr=0.3,0.1

Type RM Length L Ch R = 1 ,45715.5 ,186.3,185.9,185.4
XS GIS Cut Line= 2
     1860601.527      235874.577     1861017.458      236367.685
#Sta/Elev= 30
       0 1438.33   45.441438.928      88 1439.14    97.7 1438.28   107.5 1436.37
  120.62  1432.8   127.1 1431.04   136.8 1429.82   146.6 1430.28  161.96 1432.82
     1701434.188   175.9 1435.07   185.7 1435.71   195.5 1435.83   244.4 1435.34
  288.821434.487   312.8 1434.87   351.9  1436.2  375.521436.121   410.5 1436.12
     518 1438.96   547.4 1440.59   557.1 1441.64  567.361443.301   596.2 1449.31
     606 1452.15   615.8 1456.38   625.6 1461.31   635.3 1465.58   645.1 1468.73
#Mann= 8 ,-1 , 0
       0     .06       0   45.44     .12       0  120.62    .045       0
  161.96     .12       0     170     .06       0  288.82     .12       0
  375.52     .06       0  567.36     .12       0
#XS Ineff= 2 , 0
                          188.54         1437.57
Permanent Ineff=
       F       F
Bank Sta=120.62,161.96
XS Rating Curve= 0 ,0
Exp/Cntr=0.3,0.1

Type RM Length L Ch R = 1 ,45529.6 ,231.7,231.1,230.4
XS GIS Cut Line= 3
     1860429.652      235861.557      1860481.81      236022.601
     1860840.375      236436.695
#Sta/Elev= 30
       0 1440.85     9.4 1436.82    18.8 1434.05    28.2 1433.05    37.6 1432.78
   74.321433.033  181.211434.224   218.2 1434.94     228 1434.69   237.8 1432.64
   247.5 1429.71   257.3 1427.37   267.1 1426.98   276.9 1427.97   286.7  1429.7
   296.4 1431.38   306.2  1432.5     316 1432.72  326.981432.589   364.9 1431.49
   374.7 1431.66   413.8 1433.81   433.4 1434.58   472.5 1435.69     541 1436.98
   580.1  1438.5   609.4 1440.22   677.9 1446.01   697.5 1448.12     717 1450.94
#Mann= 6 ,-1 , 0
       0     .12       0   74.32     .06       0  181.21     .12       0
   247.5    .045       0   286.7     .12       0  326.98     .06       0
#XS Ineff= 2 , 0
                          314.55         1433.77
Permanent Ineff=
       F       F
Bank Sta=247.5,286.7
XS Rating Curve= 0 ,0
Exp/Cntr=0.3,0.1

Type RM Length L Ch R = 1 ,45298.5 ,204.6,220.1,235.6
XS GIS Cut Line= 4
      1860203.09      235905.827     1860289.027      236155.827
     1860494.716      236385.633     1860675.271      236524.522
#Sta/Elev= 30
       0 1451.16    29.4 1433.83    39.2 1428.95      49  1426.5    58.8 1426.35
   70.081426.454    97.9 1426.73   137.1 1427.28   264.4 1428.06  312.711429.354
   331.8 1430.04   341.5 1430.49   351.1  1430.3   360.7 1428.63  366.65 1426.79
   370.4 1425.76     380 1424.16   389.6 1424.15   399.3  1425.3   408.9  1426.8
   418.6 1427.83   428.2 1428.14     4381428.118   476.4 1427.76   524.6 1427.63
   563.1 1427.79   572.8 1428.24   696.2 1438.45   762.6 1444.38   800.6  1447.9
#Mann= 6 ,-1 , 0
       0     .12       0   70.08     .06       0  312.71     .12       0
  366.65    .045       0   408.9     .12       0     438     .06       0
#XS Ineff= 2 , 0
          341.59 1431.29
Permanent Ineff=
       F       F
Bank Sta=366.65,408.9
XS Rating Curve= 0 ,0
Exp/Cntr=0.3,0.1

Type RM Length L Ch R = 1 ,45078.4 ,289,277.2,265
XS GIS Cut Line= 3
     1860039.027      235918.848     1860237.771       236521.05
     1860578.049      236649.522
#Sta/Elev= 30
       0 1458.13   21.591453.498      39 1448.93    48.8 1445.33      78 1430.54
    87.8 1427.07    97.6 1425.75  104.871425.653   204.9 1427.18   341.5 1424.86
  385.34 1424.99   419.5 1425.69   429.3 1425.06   441.7  1421.7   448.8 1419.14
   458.5 1417.51   468.3 1418.02   481.2 1421.13   497.6 1424.15   507.3 1424.31
  551.251422.272   624.4 1418.21   693.1 1416.48   722.6 1417.04   761.9 1419.52
   781.6 1421.97   820.9 1429.82   840.6 1432.48   919.2 1438.06   997.9 1446.77
#Mann= 7 ,-1 , 0
       0     .06       0   21.59     .12       0  104.87     .06       0
  385.34     .12       0   441.7    .045       0   481.2     .12       0
  551.25     .06       0
Bank Sta=441.7,481.2
XS Rating Curve= 0 ,0
Exp/Cntr=0.3,0.1

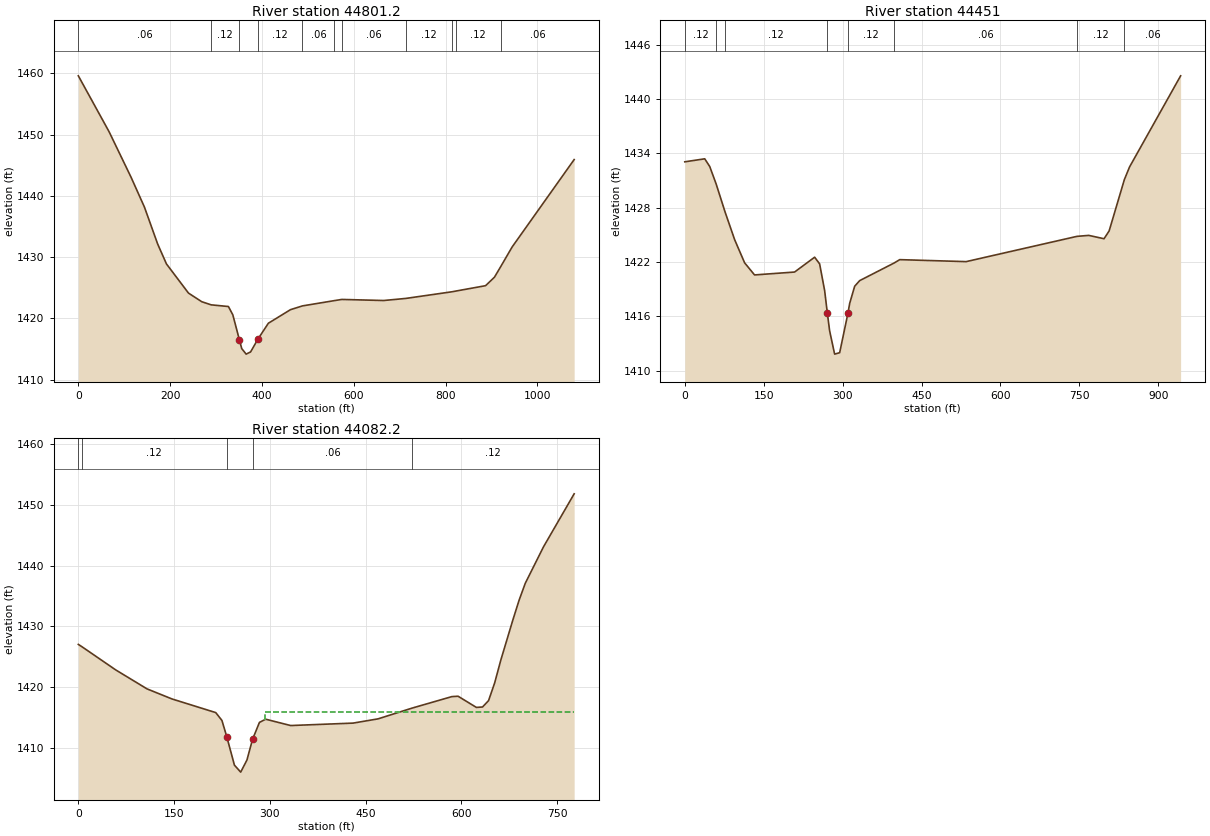
Type RM Length L Ch R = 1 ,44801.2 ,422.6,350.2,277.6
XS GIS Cut Line= 4
      1859609.34      236332.911     1859848.882      236347.439
     1860060.688      236635.633     1860529.438      236750.217
#Sta/Elev= 30
       0 1459.58    67.2 1450.43   115.2 1442.98     144 1438.16   172.8 1432.14
     192 1428.88     240 1424.12     269 1422.71  289.591422.201     327 1421.93
   336.6 1420.57  350.78 1416.53     356 1415.06   365.6 1414.16   375.3 1414.52
   391.5 1416.64     414  1419.2   462.3 1421.42  488.281422.031  557.63 1422.89
     5741423.086   665.2 1422.91  713.491423.251  814.381424.339  822.751424.456
   887.2 1425.33   906.5 1426.71  920.171428.436   945.1 1431.65  1080.2 1445.91
#Mann= 11 ,-1 , 0
       0     .06       0  289.59     .12       0  350.78    .045       0
   391.5     .12       0  488.28     .06       0  557.63     .12       0
     574     .06       0  713.49     .12       0  814.38     .06       0
  822.75     .12       0  920.17     .06       0
Bank Sta=350.78,391.5
XS Rating Curve= 0 ,0
Exp/Cntr=0.3,0.1

Type RM Length L Ch R = 1 ,44451   ,316.6,368.9,420.9
XS GIS Cut Line= 4
     1859675.271      236830.078     1859834.993      236850.911
     1859973.882       236646.05     1860491.243      236777.995
#Sta/Elev= 30
       0 1433.07    37.9  1433.4    47.4 1432.55   59.48 1430.64   76.551427.528
    94.8 1424.46   113.7 1421.91   132.6 1420.57   208.7 1420.89   246.8 1422.53
   256.3 1421.79   265.8 1418.85  271.03 1416.32   275.3  1414.4   284.8 1411.82
   294.4 1411.98  310.23 1416.37   313.4 1417.42   322.9 1419.32   332.4 1419.94
  397.651421.881   408.6 1422.26   534.8 1422.04  745.321424.831   767.8 1424.94
   796.9 1424.57   806.6 1425.43  835.531431.097   845.4  1432.5   942.5 1442.57
#Mann= 8 ,-1 , 0
       0     .12       0   59.48     .06       0   76.55     .12       0
  271.03    .045       0  310.23     .12       0  397.65     .06       0
  745.32     .12       0  835.53     .06       0
Bank Sta=271.03,310.23
XS Rating Curve= 0 ,0
Exp/Cntr=0.3,0.1

Type RM Length L Ch R = 1 ,44082.2 ,259.1,245.6,232
XS GIS Cut Line= 3
     1859706.521      236944.661     1860175.271      237142.578
     1860432.216      237218.967
#Sta/Elev= 30
       0 1427.04    5.431426.674    58.7 1422.84   107.6 1419.73   146.8 1418.07
   215.3 1415.83     225 1414.54   232.5 1411.89   244.6 1407.19   254.4 1406.04
   264.2 1408.03   272.9 1411.41   283.8 1414.22   293.6 1414.74   332.7  1413.7
   430.5  1414.1   469.7  1414.8  523.241416.576   585.4 1418.46     595 1418.52
   623.7 1416.68   633.3 1416.75   642.8  1417.8   652.4 1420.73     662 1424.47
   681.1 1431.14   690.7 1434.33   700.3 1437.09     729 1443.11   776.9  1451.8
#Mann= 5 ,-1 , 0
       0    .016       0    5.43     .12       0   232.5    .045       0
   272.9     .06       0  523.24     .12       0
#XS Ineff= 2 , 0
                          292.26         1415.91
Permanent Ineff=
       F       F
Bank Sta=232.5,272.9
XS Rating Curve= 0 ,0
Exp/Cntr=0.3,0.1