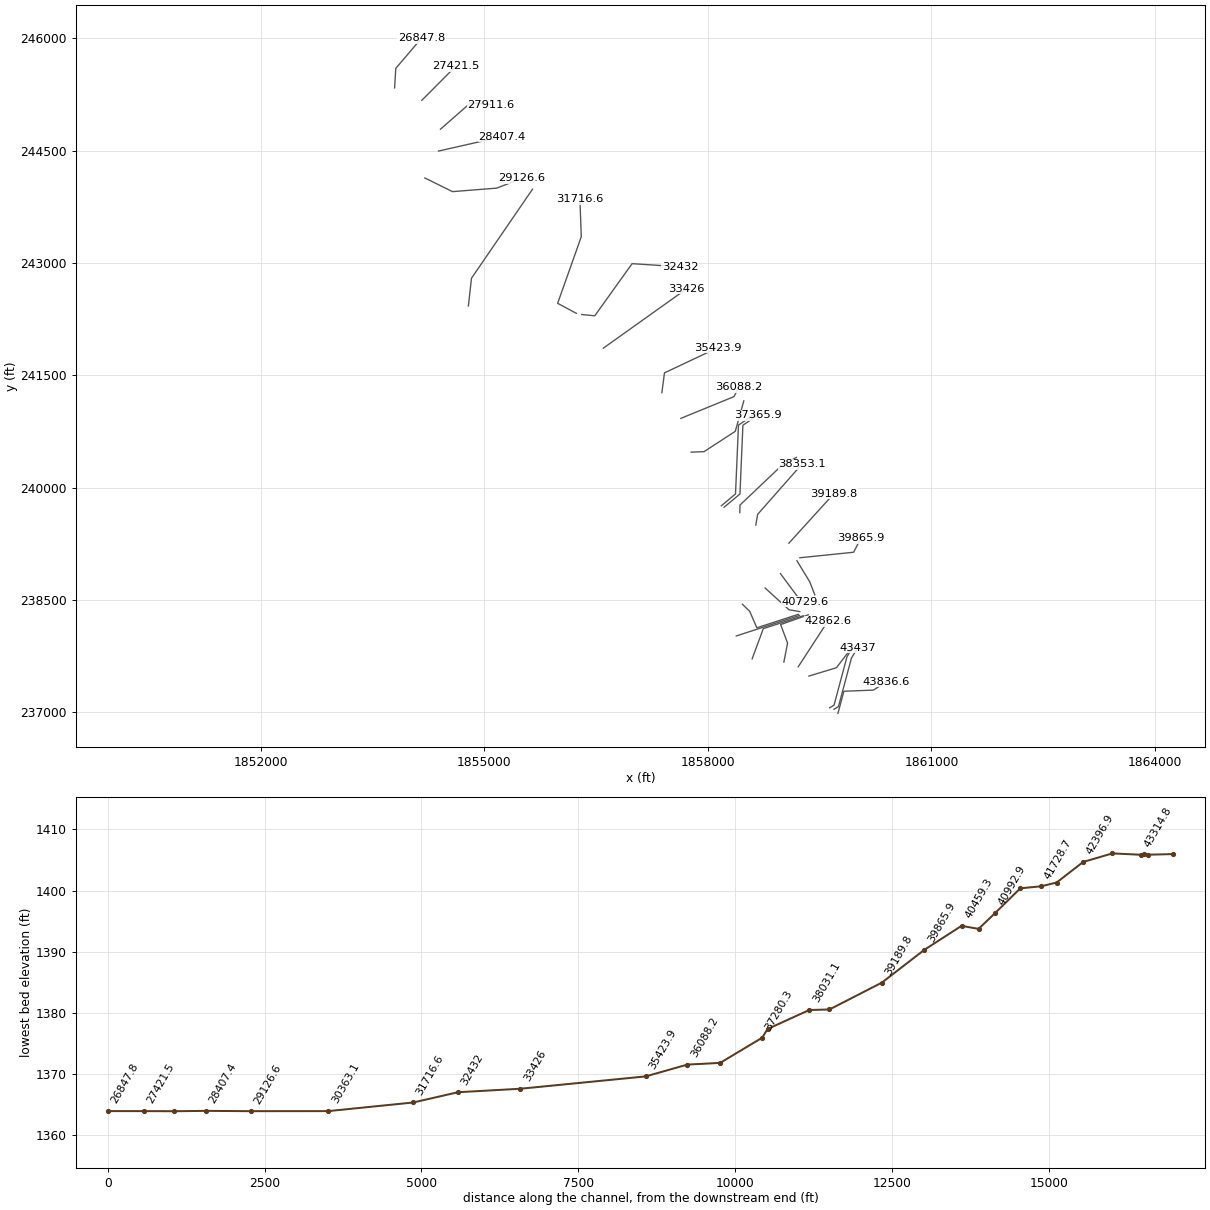
HEC-RAS study TETERCK.prj: TETERCK

--- TETERCK.g01 (geometry) --- (continued)

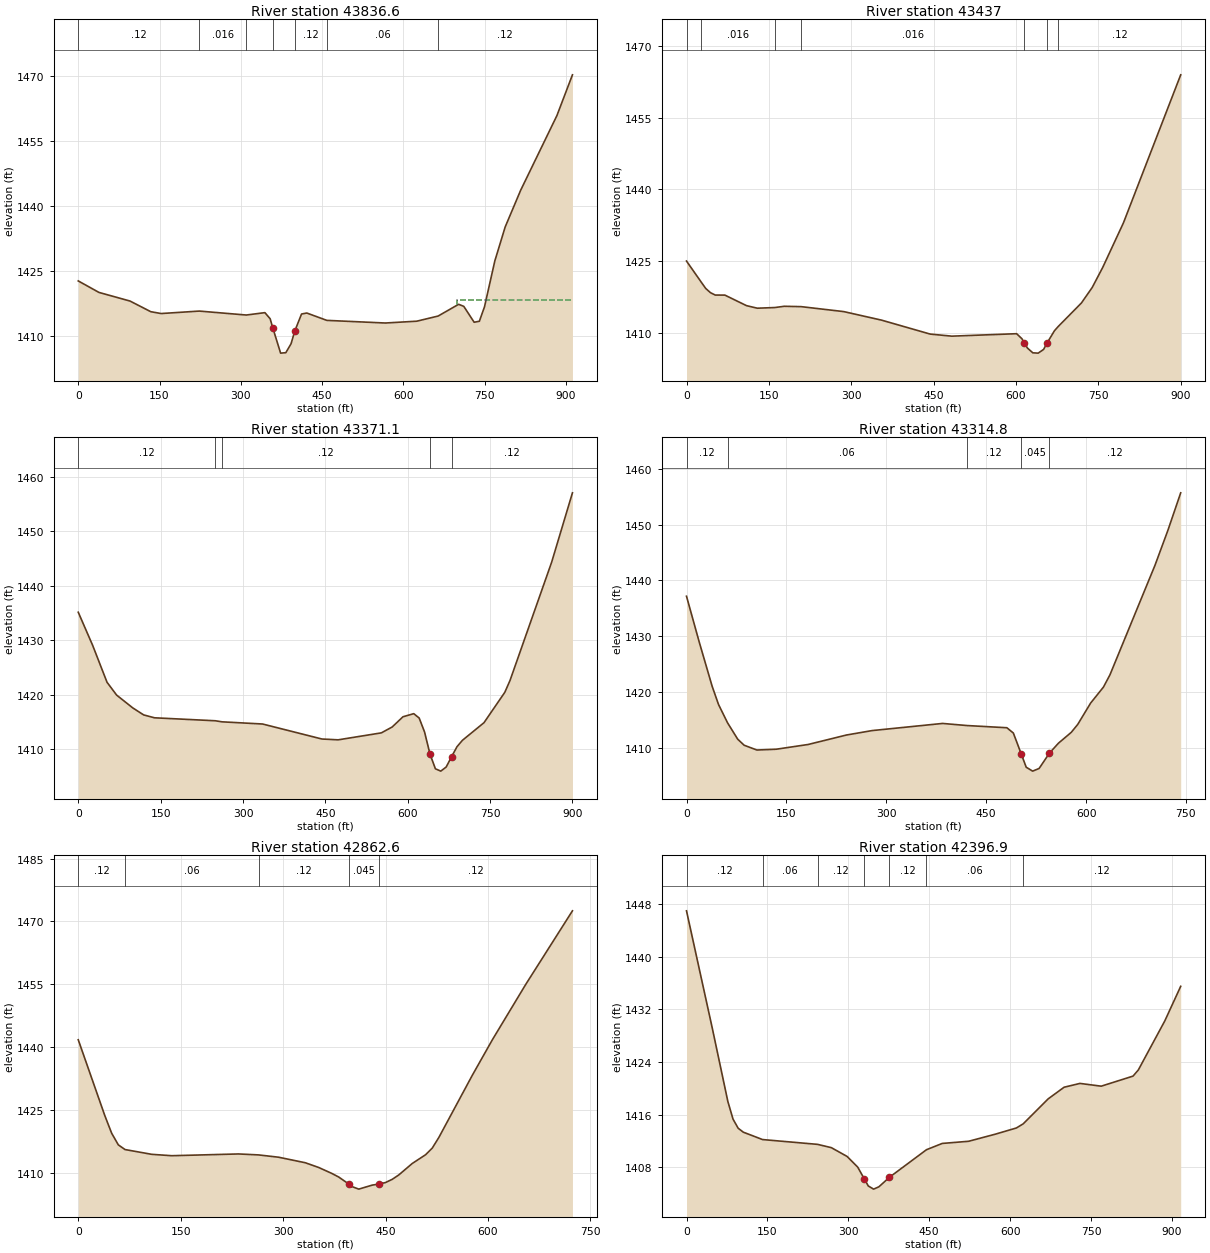
Type RM Length L Ch R = 1 ,43836.6 ,350.7,399.5,447.9
XS GIS Cut Line= 4
     1859745.294      236985.026     1859825.155      237280.165
     1860220.989       237295.79     1860398.072      237408.637
#Sta/Elev= 30
       0 1422.67    38.2 1420.01    95.6 1418.01   133.8 1415.55   152.9 1415.12
  223.321415.692   310.11414.778   344.4 1415.33   354.1 1413.91     359 1411.79
   373.4 1405.96     383 1406.06   392.7 1408.14   399.5 1411.05     412 1415.01
   421.7 1415.24  458.69 1413.54   566.6 1412.93   624.6 1413.35  664.051414.544
   701.9 1417.26   711.4 1416.78   730.5 1413.11   740.1 1413.33   749.6 1416.67
   768.7 1427.32   787.8 1435.17   816.4 1443.67   883.2 1460.93   911.9 1470.37
#Mann= 7 ,-1 , 0
       0     .12       0  223.32    .016       0   310.1     .12       0
     359    .045       0   399.5     .12       0  458.69     .06       0
  664.05     .12       0
#XS Ineff= 2 , 0
                          698.66         1418.24
Permanent Ineff=
       F       F
Bank Sta=359,399.5
XS Rating Curve= 0 ,0
Exp/Cntr=0.3,0.1

Type RM Length L Ch R = 1 ,43437   ,65,66,67.8
XS GIS Cut Line= 4
      1859692.33       237040.02     1859752.492      237075.682
     1859926.029      237721.764     1860009.196       237859.72
#Sta/Elev= 30
       0 1425.06    26.31420.754      35 1419.35    43.7 1418.46    52.4 1417.97
    69.9 1417.96   109.3 1415.76     129 1415.23  160.431415.363   178.2 1415.63
  208.821415.554   286.4 1414.52   355.2 1412.74   443.8 1409.83   483.1  1409.4
   601.2 1409.91     611 1408.84  614.74 1408.05   620.9 1406.92   630.7 1405.92
   640.5 1405.86   650.4 1406.64  656.18 1407.89     670 1410.51  676.691411.382
   719.2 1416.32   738.9 1419.56   757.9 1423.71   795.8 1433.05     900  1463.9
#Mann= 7 ,-1 , 0
       0     .12       0    26.3    .016       0  160.43     .12       0
  208.82    .016       0  614.74    .045       0  656.18    .016       0
  676.69     .12       0
Bank Sta=614.74,656.18
XS Rating Curve= 0 ,0
Exp/Cntr=0.3,0.1

Type RM Length L Ch R = 1 ,43371.1 ,71.7,56.2,39.1
XS GIS Cut Line= 4
     1859632.925      237058.736     1859693.087      237094.398
     1859866.624       237740.48     1859949.791      237878.436
#Sta/Elev= 30
       0 1435.15    26.2 1429.07    52.4 1422.28    69.9 1419.92    99.4 1417.56
   119.1 1416.28   138.8 1415.75  249.711415.203  261.941415.008   335.6 1414.61
   443.8 1411.85   473.3  1411.7     552 1412.98   571.7 1414.06   591.4 1415.94
     611 1416.51   620.9  1415.7   630.7 1413.13   640.5 1409.11   650.4 1406.38
   660.2 1405.95     670  1406.7   679.9  1408.6   689.7 1410.43   699.6 1411.61
   738.9 1414.85   776.8 1420.43   786.3 1422.61   862.1 1444.34     900 1457.09
#Mann= 5 ,-1 , 0
       0     .12       0  249.71     .06       0  261.94     .12       0
   640.5    .045       0   679.9     .12       0
Bank Sta=640.5,679.9
XS Rating Curve= 0 ,0
Exp/Cntr=0.3,0.1

Type RM Length L Ch R = 1 ,43314.8 ,449.2,452.2,455.4
XS GIS Cut Line= 3
     1859356.405       237483.29     1859724.461      237594.401
     1859943.211      237877.387
#Sta/Elev= 30
       0 1437.17    19.2 1428.93    38.4 1421.09    48.1 1417.78    61.71414.491
    76.9 1411.57    86.5 1410.49   105.7 1409.63   134.6 1409.77   182.6 1410.62
   240.3 1412.32   278.7 1413.11   384.5 1414.39  420.991414.015   481.1 1413.62
   490.8 1412.67  502.53 1408.97   510.1 1406.55   519.8 1405.85   529.5 1406.33
  545.03 1409.08   558.5 1410.85   577.8  1412.8   587.5 1414.22   606.8 1418.03
   626.1  1420.9   635.8 1423.08   703.5 1442.72   722.8 1448.95   742.1 1455.69
#Mann= 5 ,-1 , 0
       0     .12       0    61.7     .06       0  420.99     .12       0
  502.53    .045       0  545.03     .12       0
Bank Sta=502.53,545.03
XS Rating Curve= 0 ,0
Exp/Cntr=0.3,0.1

Type RM Length L Ch R = 1 ,42862.6 ,425.9,465.8,502.4
XS GIS Cut Line= 2
     1859212.308      237606.554     1859608.141      238212.456
#Sta/Elev= 30
       0 1441.74    39.1 1423.54    48.9 1419.43    58.7 1416.64   68.491415.521
   107.6 1414.38   136.9 1414.05   234.7 1414.47  264.151414.239   293.4 1413.69
   332.5 1412.37   352.1 1411.24   371.6  1409.8   381.4 1408.96  395.84 1407.33
     401 1406.67   410.8 1406.07   430.3 1407.02   440.1 1407.28   449.9 1407.64
   459.7  1408.4   469.4 1409.46     489 1412.18   508.6 1414.28   518.4 1415.87
   528.1 1418.42     577 1433.24   606.4 1441.73   655.3 1454.96   723.7 1472.53
#Mann= 5 ,-1 , 0
       0     .12       0   68.49     .06       0  264.15     .12       0
  395.84    .045       0   440.1     .12       0
Bank Sta=395.84,440.1
XS Rating Curve= 0 ,0
Exp/Cntr=0.3,0.1

Type RM Length L Ch R = 1 ,42396.9 ,449.2,422.3,395
XS GIS Cut Line= 4
     1859020.034      237669.488     1859069.947      237923.394
     1858976.631       238170.79     1859347.725      238300.998
#Sta/Elev= 30
       0 1446.95    47.9 1429.09    76.7 1417.98    86.3  1415.3    95.8 1413.92
   105.4 1413.32  141.04  1412.2  243.041411.471   268.6 1410.97   297.9 1409.63
   317.5 1408.01   329.6 1406.24   337.1 1405.15   346.9 1404.67   356.7 1405.02
   376.3 1406.47  445.021410.659   474.2 1411.61   523.2 1411.94   572.3 1413.01
   611.7 1413.96  624.231414.581   670.6 1418.38   700.2 1420.15   729.6 1420.73
     769 1420.31     828 1421.84   837.8 1422.77     887 1430.24   916.4 1435.48
#Mann= 7 ,-1 , 0
       0     .12       0  141.04     .06       0  243.04     .12       0
   329.6    .045       0   376.3     .12       0  445.02     .06       0
  624.23     .12       0
Bank Sta=329.6,376.3
XS Rating Curve= 0 ,0
Exp/Cntr=0.3,0.1

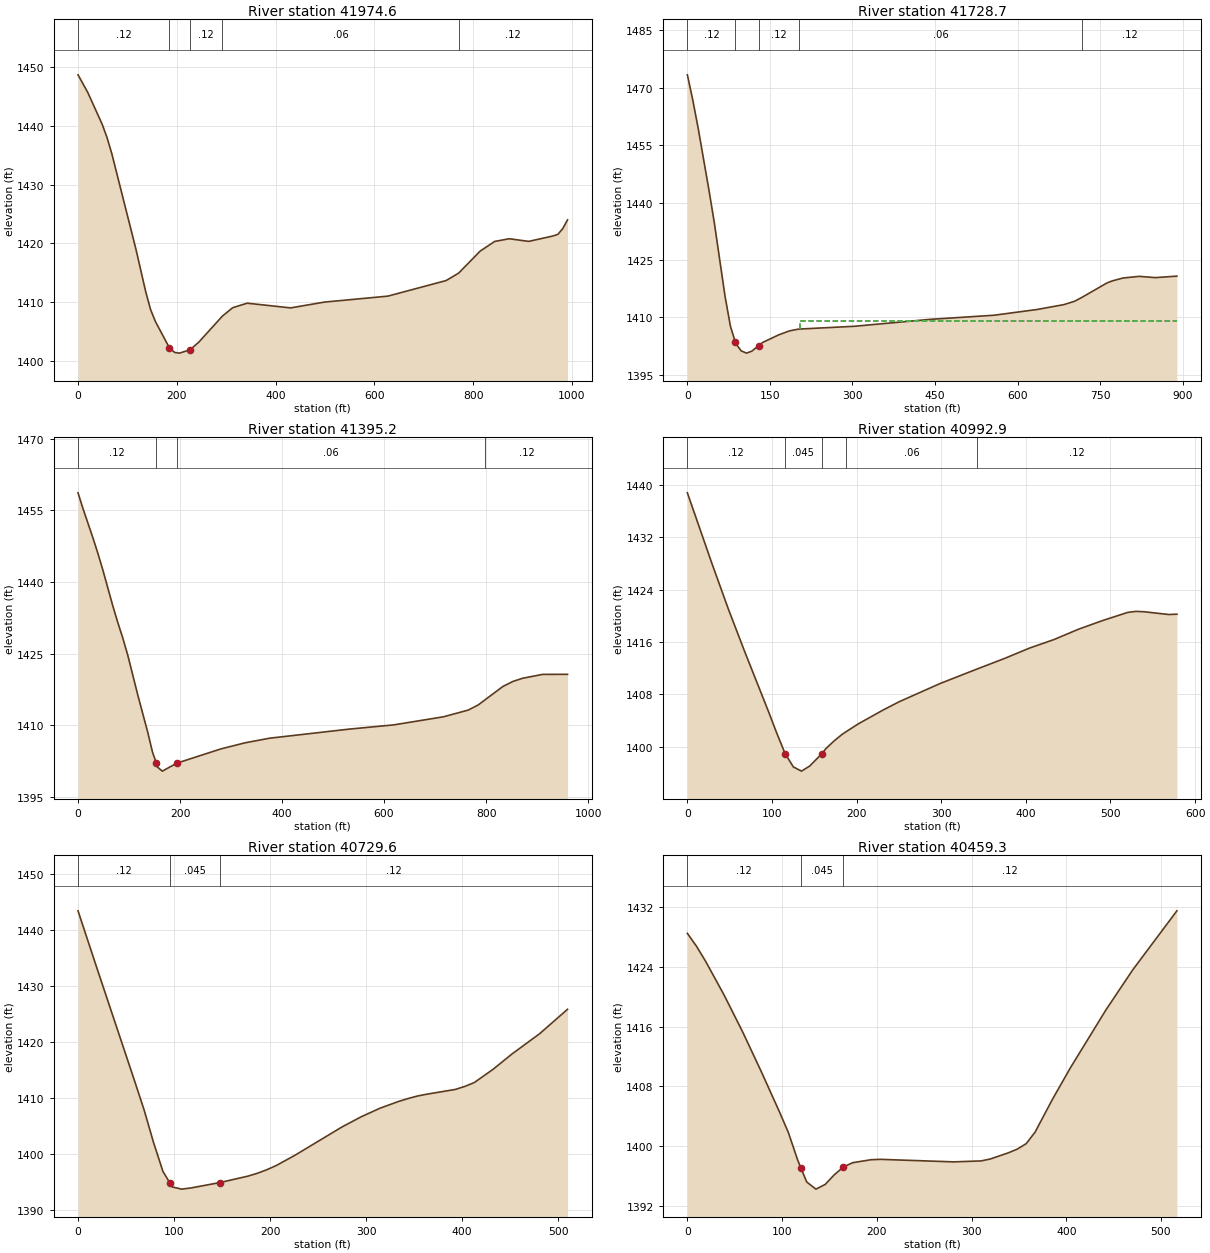
Type RM Length L Ch R = 1 ,41974.6 ,280.2,245.9,211.5
XS GIS Cut Line= 3
     1858594.687       237712.89     1858744.426      238116.536
      1859278.28      238287.977
#Sta/Elev= 30
       0 1448.68    19.6 1445.71    48.9 1440.27    58.7 1438.02    68.5 1435.24
   117.4 1418.96     137 1411.79   146.8 1408.76   156.6 1406.71     185 1402.22
   195.7 1401.43   205.5 1401.31     227 1401.89   244.6 1403.18   292.31407.609
   313.1 1409.04   342.5 1409.81   430.5 1409.01   499.4    1410   627.3 1411.01
   745.3 1413.66  770.741414.929   814.2 1418.67   843.7 1420.32   873.2 1420.78
   912.5 1420.33   961.7 1421.25   971.6 1421.52   981.4 1422.49   991.2 1423.99
#Mann= 5 ,-1 , 0
       0     .12       0     185    .045       0     227     .12       0
   292.3     .06       0  770.74     .12       0
Bank Sta=185,227
XS Rating Curve= 0 ,0
Exp/Cntr=0.3,0.1

Type RM Length L Ch R = 1 ,41728.7 ,384.3,333.6,277.9
XS GIS Cut Line= 2
     1858382.013       238018.88     1859228.367      238292.317
#Sta/Elev= 30
       0 1473.41     9.8 1466.83    19.6 1459.46    39.1 1443.39    48.9 1434.81
    68.4 1415.58    78.2 1407.72    87.2 1403.55      88 1403.18    97.7 1401.28
   107.5 1400.69   117.3 1401.22   129.4 1402.68   136.8 1403.48   166.2 1405.48
   185.7 1406.51  202.411406.973     303  1407.7   439.8  1409.5   557.1 1410.59
   635.3 1412.09   684.2 1413.37   703.7 1414.25   716.91415.265   762.4 1419.03
   772.1 1419.57   791.7 1420.32     821 1420.75   850.3 1420.42   889.4 1420.81
#Mann= 5 ,-1 , 0
       0     .12       0    87.2    .045       0   129.4     .12       0
  202.41     .06       0   716.9     .12       0
#XS Ineff= 2 , 0
                          204.33         1409.05
Permanent Ineff=
       F       F
Bank Sta=87.2,129.4
XS Rating Curve= 0 ,0
Exp/Cntr=0.3,0.1

Type RM Length L Ch R = 1 ,41395.2 ,390.7,402.3,417.5
XS GIS Cut Line= 4
     1858464.478      238442.057     1858562.135      238346.571
     1858657.621      238127.387     1859213.176      238307.508
#Sta/Elev= 30
       0 1458.67     9.8 1455.35    29.3 1449.22      39 1445.97    48.8 1442.47
    68.3 1434.95      78 1431.49    87.8 1428.24    97.6 1424.63   117.1 1416.34
   136.6 1408.55   146.1 1404.32  153.31 1402.14   155.7 1401.22   165.3 1400.36
     194 1402.04     280 1405.01   327.8  1406.3   375.7 1407.26   531.4 1409.16
     619 1410.05   716.3 1411.74     765 1413.15   784.5 1414.22  798.721415.362
   833.2 1418.11   852.6 1419.15   872.1 1419.83     911 1420.63   959.7 1420.64
#Mann= 4 ,-1 , 0
       0     .12       0  153.31    .045       0     194     .06       0
  798.72     .12       0
Bank Sta=153.31,194
XS Rating Curve= 0 ,0
Exp/Cntr=0.3,0.1

Type RM Length L Ch R = 1 ,40992.9 ,270.8,263.3,256.4
XS GIS Cut Line= 3
     1858768.298      238659.071     1859089.478      238368.272
     1859232.707      238344.401
#Sta/Elev= 30
       0 1438.77    28.9 1428.03    48.1 1421.15    67.4 1414.65    96.3 1405.25
   105.9 1402.01   115.5 1398.98   125.2 1396.95   134.8  1396.3   144.4 1397.06
  158.73 1398.93   163.7 1399.73   173.3  1400.9   182.9 1401.91  187.671402.323
   202.2 1403.53   231.1 1405.61   250.3 1406.89   298.5 1409.66  342.071411.868
   375.5 1413.53   404.4 1415.08   433.3 1416.38   462.3 1417.96   491.4 1419.31
   520.4 1420.52   530.1 1420.68   539.8 1420.62   568.8  1420.2   578.5 1420.25
#Mann= 5 ,-1 , 0
       0     .12       0   115.5    .045       0  158.73     .12       0
  187.67     .06       0  342.07     .12       0
Bank Sta=115.5,158.73
XS Rating Curve= 0 ,0
Exp/Cntr=0.3,0.1

Type RM Length L Ch R = 1 ,40729.6 ,273.7,270.3,266.7
XS GIS Cut Line= 3
     1858973.923       238851.14     1859226.527      238512.598
     1859304.652      238473.536
#Sta/Elev= 30
       0 1443.35    19.6 1433.18    58.9 1413.02    68.8 1407.86    78.6 1402.06
    88.4 1396.89    95.4  1394.9    98.2  1394.1   108.1 1393.72   117.9 1393.94
   147.4 1394.88   176.8 1396.03   186.6 1396.54   196.5 1397.17   206.3 1397.92
   225.9 1399.76     275 1404.82   294.7 1406.61   314.3 1408.14     334 1409.37
   343.8 1409.88   353.6 1410.33   363.5 1410.66   392.9  1411.5   402.8 1412.04
   412.6 1412.72   432.1 1415.08   451.5 1417.77   480.6 1421.43   509.7 1425.79
#Mann= 3 ,-1 , 0
       0     .12       0    95.4    .045       0   147.4     .12       0
Bank Sta=95.4,147.4
XS Rating Curve= 0 ,0
Exp/Cntr=0.3,0.1

Type RM Length L Ch R = 1 ,40459.3 ,546.8,593.5,636.9
XS GIS Cut Line= 3
     1859195.277      239023.015     1859367.152      238741.765
      1859434.86      238567.286
#Sta/Elev= 30
       0 1428.48     9.7 1426.74    19.4 1424.71    38.8 1420.21    58.2 1415.32
    77.6 1410.08    96.9 1404.66   106.6 1401.81   116.3 1398.17  119.82 1397.06
     126 1395.18   135.7 1394.22   145.4 1394.84   155.1 1396.14   164.8 1397.19
   174.5 1397.76   193.9 1398.16   203.6 1398.21   281.1 1397.87   310.2    1398
   319.9 1398.26     339 1399.09   348.3 1399.58   357.7 1400.31     367 1401.84
   385.8 1406.34   404.5  1410.5   441.9 1418.23     470 1423.56   516.8  1431.5
#Mann= 3 ,-1 , 0
       0     .12       0  119.82    .045       0   164.8     .12       0
Bank Sta=119.82,164.8
XS Rating Curve= 0 ,0
Exp/Cntr=0.3,0.1

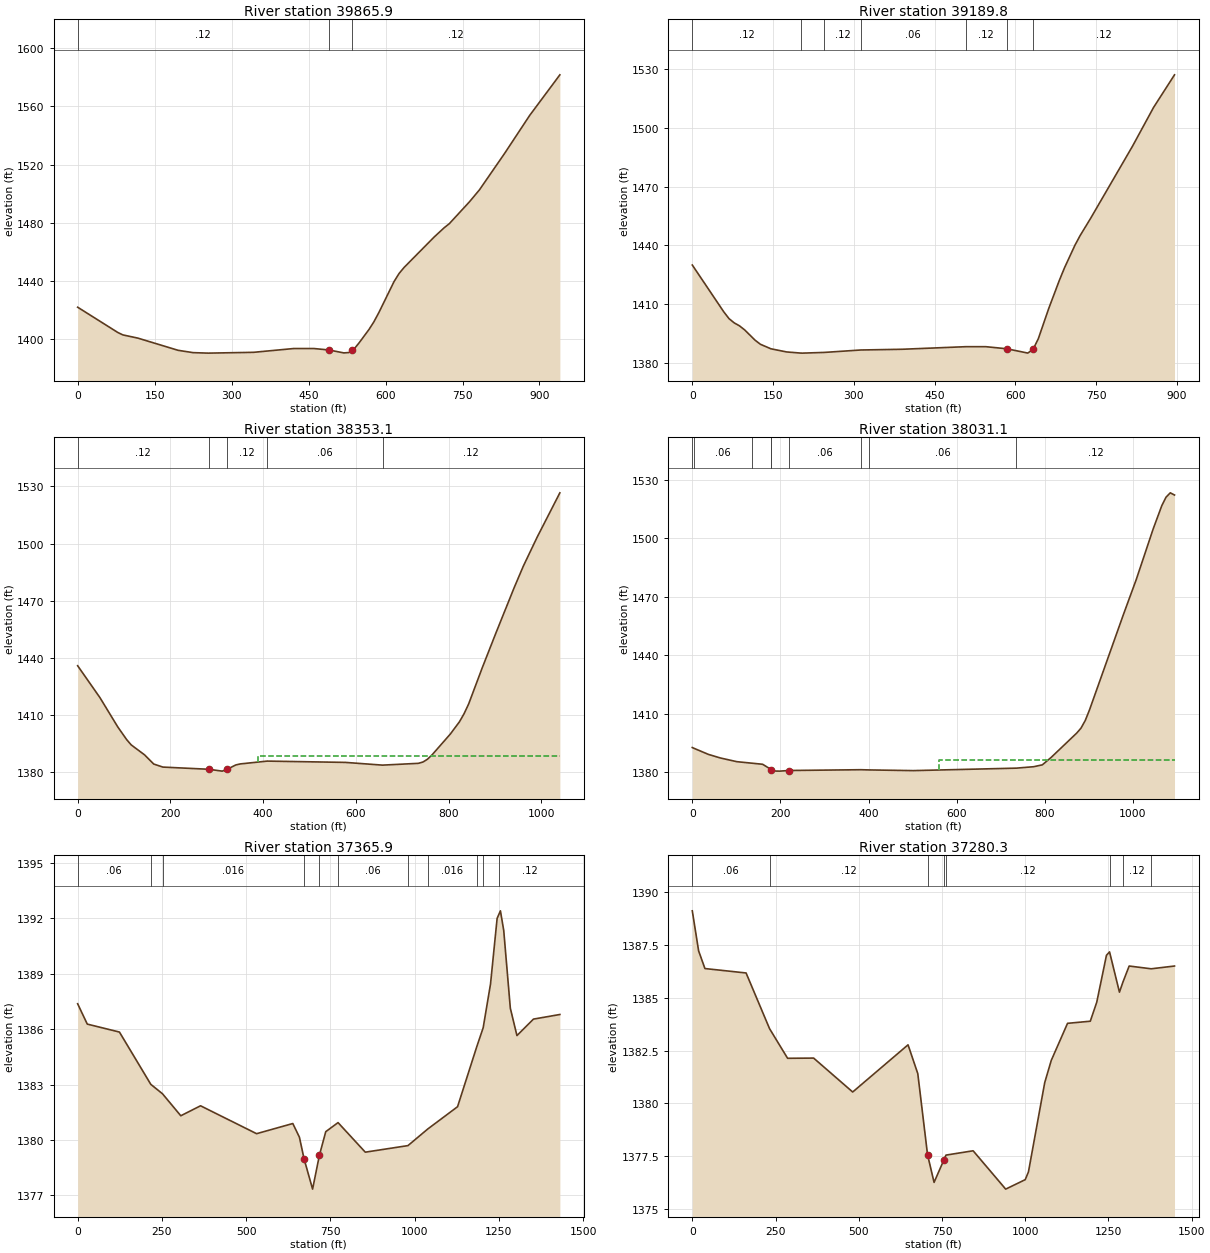
Type RM Length L Ch R = 1 ,39865.9 ,653,676,702.7
XS GIS Cut Line= 3
     1859234.878      239062.717     1859955.364      239136.502
      1860055.19      239327.474
#Sta/Elev= 30
       0 1421.88    78.3 1404.49    88.1 1402.83   117.4 1400.62   195.7 1392.24
   225.1 1390.63   254.5  1390.3   342.6 1390.85   420.8 1393.45     460 1393.47
   489.4 1392.48   518.7 1390.45   528.5  1390.7  535.59 1392.33   538.3    1393
   548.1  1397.2   567.7 1406.54   577.4  1411.9   587.2 1418.36   616.6 1439.53
   626.4  1445.1   636.2 1449.25   694.9 1470.21   714.5  1476.6   724.2  1479.3
   763.4 1494.32     783  1502.6     832 1527.65     881 1553.85   939.7  1581.7
#Mann= 3 ,-1 , 0
       0     .12       0   489.4    .045       0  535.59     .12       0
Bank Sta=489.4,535.59
XS Rating Curve= 0 ,0
Exp/Cntr=0.3,0.1

Type RM Length L Ch R = 1 ,39189.8 ,832.9,836.7,838.8
XS GIS Cut Line= 2
     1859087.308      239257.595     1859691.475      239919.054
#Sta/Elev= 30
       0 1429.97    58.4 1406.08    68.2 1402.58    77.9  1400.4    87.6  1398.9
    97.4 1396.78   116.8 1391.51   126.6 1389.46   146.1 1387.15   175.3 1385.54
  201.031384.972   204.5 1384.94  245.27  1385.3     313 1386.54   389.5 1386.91
   507.91388.228   545.3 1388.23   584.2 1387.17   623.2 1384.97   632.9 1386.81
   642.7 1392.22   662.2 1407.79   681.6 1421.94   691.4 1428.52   710.8 1440.07
   720.6 1445.09     740 1453.85     818 1490.82   856.9 1510.52   895.8 1527.19
#Mann= 7 ,-1 , 0
       0     .12       0  201.03     .06       0  245.27     .12       0
     313     .06       0   507.9     .12       0   584.2    .045       0
   632.9     .12       0
Bank Sta=584.2,632.9
XS Rating Curve= 0 ,0
Exp/Cntr=0.3,0.1

Type RM Length L Ch R = 1 ,38353.1 ,325.9,322,318.2
XS GIS Cut Line= 3
     1858643.732      239499.783     1858668.037      239642.144
     1859261.787      240312.283
#Sta/Elev= 30
       0 1435.85    48.1  1419.1    86.6 1403.71   105.9 1397.02   115.5  1394.3
   144.4 1389.06   164.1 1384.25   183.8 1382.66   282.2 1381.52   311.7 1380.54
   321.5  1381.4   341.2  1383.8     351 1384.33  408.841385.803   577.3 1385.12
  657.421383.688   734.8 1384.63   744.6 1385.32   754.4  1386.8   764.3  1389.1
   803.6    1400   823.3 1406.45   833.1 1410.61     843 1415.73   872.5 1434.81
     902 1453.09   941.4 1476.91     961 1488.12   990.6 1503.22  1039.8  1526.6
#Mann= 5 ,-1 , 0
       0     .12       0   282.2    .045       0   321.5     .12       0
  408.84     .06       0  657.42     .12       0
#XS Ineff= 2 , 0
                          388.85         1388.65
Permanent Ineff=
       F       F
Bank Sta=282.2,321.5
XS Rating Curve= 0 ,0
Exp/Cntr=0.3,0.1

Type RM Length L Ch R = 1 ,38031.1 ,618.5,665.2,696.3
XS GIS Cut Line= 4
     1858429.146      239665.189      1858430.95      239766.217
     1858985.181      240289.103     1859186.856      240403.055
#Sta/Elev= 30
       0 1392.57    2.891392.259    36.7 1389.03    64.3 1387.17     101 1385.31
  135.621384.518   159.7 1383.97  177.921381.427   179.2 1381.23     189 1380.48
   198.7 1380.45   218.9 1380.77  382.781381.173  401.881381.064   501.6 1380.71
  735.471381.982   775.1 1382.72   794.6 1383.68   814.2  1387.4   872.6 1399.98
   882.3 1402.51     892 1406.45   901.6 1411.86   978.8 1460.96  1007.8 1478.85
  1046.4 1504.94  1065.7 1516.73  1075.3 1521.08    1085 1523.34  1094.6 1522.21
#Mann= 9 ,-1 , 0
       0    .016       0    2.89     .06       0  135.62    .016       0
  177.92     .12       0   179.2    .045       0   218.9     .06       0
  382.78     .12       0  401.88     .06       0  735.47     .12       0
#XS Ineff= 2 , 0
                          560.99         1386.22
Permanent Ineff=
       F       F
Bank Sta=179.2,218.9
XS Rating Curve= 0 ,0
Exp/Cntr=0.3,0.1

Type RM Length L Ch R = 1 ,37365.9 ,95.4,85.6,324.4
XS GIS Cut Line= 4
     1858218.069      239737.352      1858430.95      239914.151
      1858470.64      240832.424     1858665.479      240964.121
#Sta/Elev= 30
       0 1387.37    28.6 1386.27     124 1385.84  217.08 1383.01  251.821382.499
   306.1 1381.31   364.7 1381.85     531 1380.34   638.5 1380.89   658.1 1380.15
   671.9 1378.98   697.2 1377.34   717.5 1379.18   736.3 1380.45  772.71 1380.94
   853.6 1379.34  980.191379.695 1039.281380.598  1127.4  1381.8 1184.681385.063
 1203.431386.073  1225.2 1388.44  1244.8 1391.99 1251.091392.253  1254.6  1392.4
  1264.4 1391.34    1284 1387.13  1303.6 1385.65  1352.6 1386.54    1431 1386.79
#Mann= 11 ,-1 , 0
       0     .06       0  217.08     .12       0  251.82    .016       0
   671.9    .045       0   717.5     .12       0  772.71     .06       0
  980.19     .12       0 1039.28    .016       0 1184.68     .12       0
 1203.43    .016       0 1251.09     .12       0
Bank Sta=671.9,717.5
XS Rating Curve= 0 ,0
Exp/Cntr=0.3,0.1

Type RM Length L Ch R = 1 ,37280.3 ,713.7,669.6,139.2
XS GIS Cut Line= 4
     1858181.988      239757.197     1858371.416      239915.955
     1858411.105      240834.228     1858645.635      240991.183
#Sta/Elev= 30
       0 1389.13      19 1387.23      38 1386.39   161.6 1386.18   232.11383.537
   286.3 1382.13   364.5 1382.14   481.8 1380.53   648.1 1382.77   677.4  1381.4
   706.7 1377.55   726.3 1376.24   755.6  1377.3     7621377.535   843.6 1377.74
   941.4 1375.92  1000.1 1376.37  1009.8 1376.74  1058.7 1380.98  1078.3 1382.03
  1127.2 1383.79  1195.5 1383.89  1214.9 1384.79  1244.1 1387.02 1253.391387.181
  1283.1 1385.27 1293.831385.758  1312.3 1386.51 1378.441386.378  1448.5 1386.51
#Mann= 8 ,-1 , 0
       0     .06       0   232.1     .12       0   706.7    .045       0
   755.6     .06       0     762     .12       0 1253.39    .016       0
 1293.83     .12       0 1378.44     .06       0
Bank Sta=706.7,755.6
XS Rating Curve= 0 ,0
Exp/Cntr=0.3,0.1

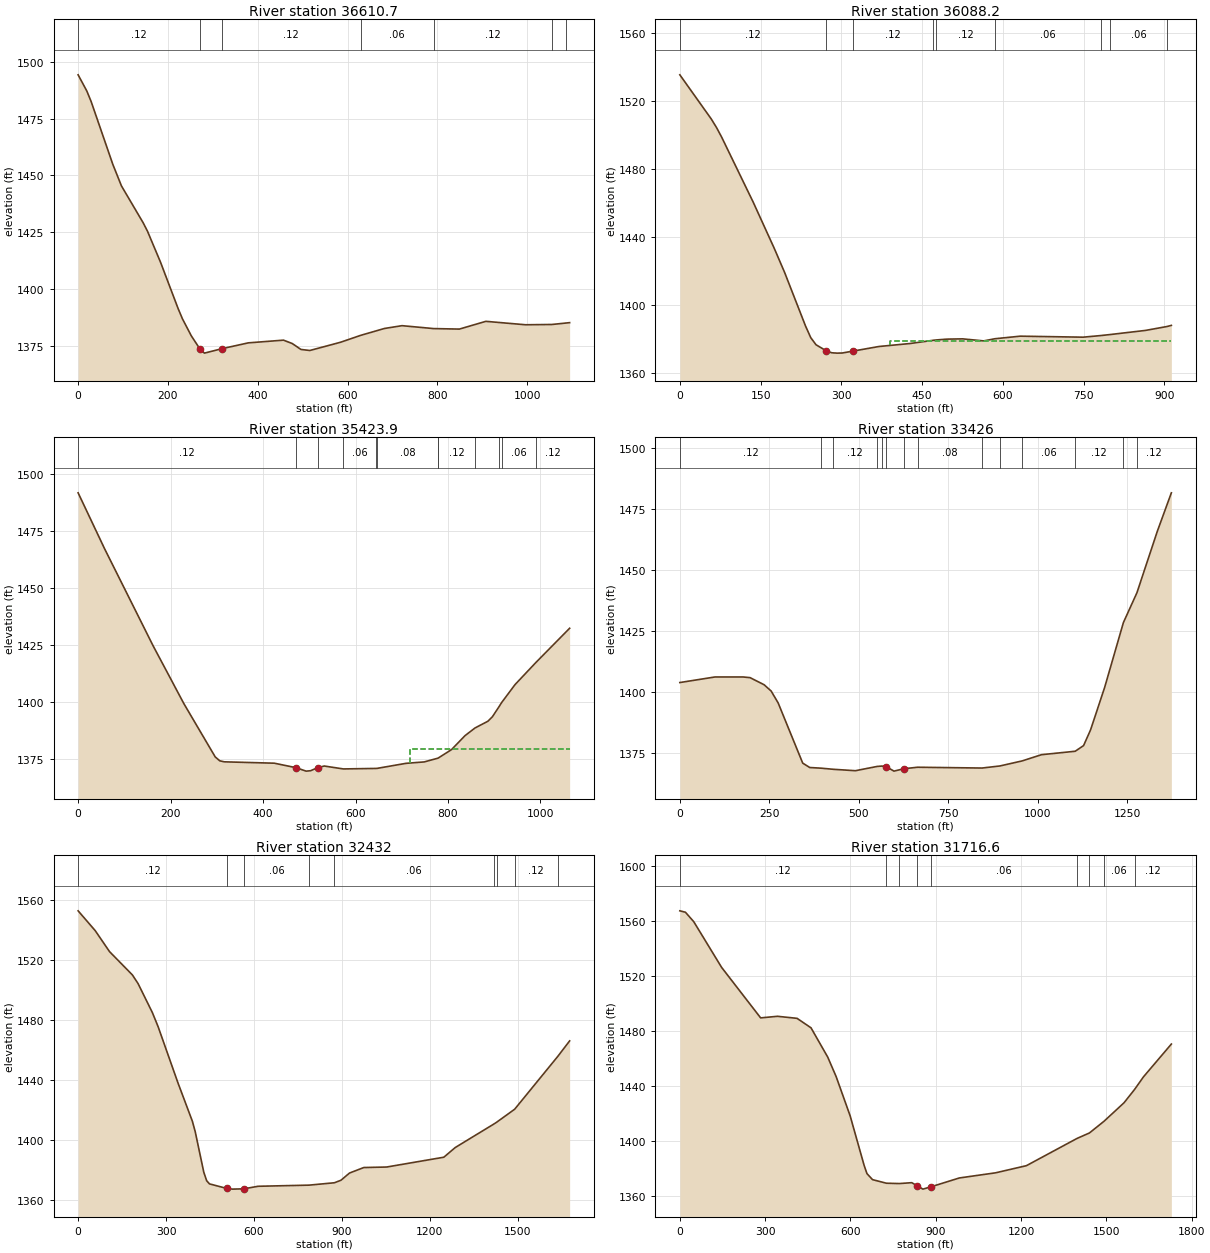
Type RM Length L Ch R = 1 ,36610.7 ,529.5,522.6,761.8
XS GIS Cut Line= 4
      1857776.09      240472.956     1857949.701      240479.901
     1858368.104      240750.734     1858482.687      241156.984
#Sta/Elev= 30
       0 1494.27    19.3 1487.18      29 1482.52    77.2 1454.91    96.5 1445.38
   144.8 1429.17   154.4 1425.47   183.5  1411.8   222.6 1391.43   232.4 1386.85
   251.9 1379.45   271.5 1373.53   281.2  1371.8   320.3 1373.76     379 1376.32
   457.2 1377.51   476.7 1376.03   496.2 1373.41   515.8 1372.96   584.2 1376.58
   628.9 1379.61     682 1382.65   721.2 1383.88  791.761382.597   848.8 1382.38
   907.8 1385.79   996.1 1384.28 1054.741384.405 1085.291385.028  1094.3 1385.21
#Mann= 7 ,-1 , 0
       0     .12       0   271.5    .045       0   320.3     .12       0
   628.9     .06       0  791.76     .12       0 1054.74     .06       0
 1085.29     .12       0
Bank Sta=271.5,320.3
XS Rating Curve= 0 ,0
Exp/Cntr=0.3,0.1

Type RM Length L Ch R = 1 ,36088.2 ,662.2,664.2,666.2
XS GIS Cut Line= 3
     1857638.937      240924.345     1858350.743      241214.276
     1858416.715      241342.748
#Sta/Elev= 30
       0 1535.19    58.4 1509.21    68.1 1504.21    77.8 1498.46   136.2 1460.35
   175.1 1433.34   194.6 1418.99   233.5 1387.45   243.2  1380.6     253 1376.44
   272.4 1372.79   282.1 1371.73   291.9 1371.52   301.6 1371.59   321.1 1372.68
   369.7 1375.41   428.1 1377.19  470.751379.071  476.261379.265   496.2 1379.75
   525.4 1379.91   564.3 1378.71  585.311379.985   632.4 1381.49   749.1  1380.9
  781.571381.839  799.131382.444   864.9 1384.87  904.921387.173     913 1387.83
#Mann= 9 ,-1 , 0
       0     .12       0   272.4    .045       0   321.1     .12       0
  470.75     .06       0  476.26     .12       0  585.31     .06       0
  781.57     .12       0  799.13     .06       0  904.92     .12       0
#XS Ineff= 2 , 0
                          390.09         1378.85
Permanent Ineff=
       F       F
Bank Sta=272.4,321.1
XS Rating Curve= 0 ,0
Exp/Cntr=0.3,0.1

Type RM Length L Ch R = 1 ,35423.9 ,1976.7,1998,1992.4
XS GIS Cut Line= 3
     1857383.584      241266.649     1857418.307      241531.406
     1858138.793      241869.947
#Sta/Elev= 30
       0 1491.67    57.2 1467.17   162.1 1424.61   228.9 1399.14   296.5 1375.84
   306.3 1374.12   316.2 1373.67   424.3 1373.07   470.8 1371.12   493.1 1369.59
   502.9 1369.77   517.9 1371.09   532.4 1371.83  573.621370.554  644.641370.773
  646.921370.808   709.3 1373.01   748.6 1373.63  778.51 1375.29  778.621375.301
   807.6 1379.02     837 1385.18  858.621388.544   886.2 1391.46     896 1393.42
   910.41397.862  916.231399.731   945.2 1407.59  991.311417.495  1063.1 1432.26
#Mann= 12 ,-1 , 0
       0     .12       0   470.8    .045       0   517.9     .12       0
  573.62     .06       0  644.64     .12       0  646.92     .08       0
  778.51     .06       0  778.62     .12       0  858.62    .016       0
   910.4     .12       0  916.23     .06       0  991.31     .12       0
#XS Ineff= 2 , 0
                          718.27         1379.16
Permanent Ineff=
       F       F
Bank Sta=470.8,517.9
XS Rating Curve= 0 ,0
Exp/Cntr=0.3,0.1

Type RM Length L Ch R = 1 ,33426   ,952,994,973.2
XS GIS Cut Line= 2
     1856597.994      241861.267     1857717.786      242655.537
#Sta/Elev= 30
       0 1403.82    98.1  1406.1   176.5  1406.1   196.1 1405.83   235.4 1402.92
     255 1400.35   274.6 1395.48   343.2 1370.85   362.8 1369.05  395.241368.773
  428.491368.323   490.3 1367.74  551.341369.493  564.211369.637   576.4 1369.39
   598.2 1367.57   625.1 1368.54   663.91369.161  844.261368.833  894.151369.688
  956.161371.748    1010 1374.29 1104.331375.705  1127.7 1378.02  1147.3 1384.47
  1186.6 1401.84 1238.941428.366 1276.731440.571  1333.6 1465.68  1372.9 1481.46
#Mann= 14 ,-1 , 0
       0     .12       0  395.24     .06       0  428.49     .12       0
  551.34     .06       0  564.21     .12       0   576.4    .045       0
   625.1     .12       0   663.9     .08       0  844.26     .06       0
  894.15     .12       0  956.16     .06       0 1104.33     .12       0
 1238.94    .016       0 1276.73     .12       0
Bank Sta=576.4,625.1
XS Rating Curve= 0 ,0
Exp/Cntr=0.3,0.1

Type RM Length L Ch R = 1 ,32432   ,700.3,715.4,727.9
XS GIS Cut Line= 4
     1856308.932      242310.919     1856483.375      242293.447
     1856984.279      242989.739     1857626.727      242948.394
#Sta/Elev= 30
       0 1552.77    58.4 1539.53   107.1 1525.56   185.1    1510   204.6 1504.19
   253.3 1484.86   272.8  1475.5     341 1437.72   389.8 1412.32   399.5 1405.34
   428.7 1378.32   438.5 1372.63   448.2  1370.5   506.7 1367.48   526.2    1367
   565.2  1367.2   613.9  1368.9  787.881369.662  874.341371.248   896.6 1372.91
   925.8 1377.73   974.6 1381.41  1052.6 1381.75  1247.6  1388.3  1286.7 1394.78
 1419.261410.565 1427.381411.595 1489.261420.335 1636.581455.647  1676.8 1465.95
#Mann= 9 ,-1 , 0
       0     .12       0   506.7    .045       0   565.2     .06       0
  787.88     .12       0  874.34     .06       0 1419.26     .12       0
 1427.38    .016       0 1489.26     .12       0 1636.58    .016       0
Bank Sta=506.7,565.2
XS Rating Curve= 0 ,0
Exp/Cntr=0.3,0.1

Type RM Length L Ch R = 1 ,31716.6 ,1257.8,1353.5,1349.6
XS GIS Cut Line= 4
     1856236.015      242326.544     1855985.336      242460.345
     1856302.855      243349.982     1856283.845      243849.435
#Sta/Elev= 30
       0 1567.68    19.6 1566.67      49 1559.76     147 1526.52   284.2 1489.83
   343.2 1490.99   412.1 1489.51   461.3 1482.62   520.3 1461.25   549.8 1447.09
     599 1418.57   648.2 1382.52   658.1 1376.59   677.7 1372.22  726.491369.615
  772.341369.371   815.5 1370.01   835.2 1367.72   854.8 1365.32   884.4 1367.08
   982.8 1373.43  1110.7 1377.19  1218.9 1382.38 1396.711402.168 1440.341406.138
 1491.471414.617    1562 1428.08 1599.111437.757  1630.6 1446.98  1728.6  1470.8
#Mann= 9 ,-1 , 0
       0     .12       0  726.49     .06       0  772.34     .12       0
   835.2    .045       0   884.4     .06       0 1396.71    .016       0
 1440.34     .12       0 1491.47     .06       0 1599.11     .12       0
Bank Sta=835.2,884.4
XS Rating Curve= 0 ,0
Exp/Cntr=0.3,0.1

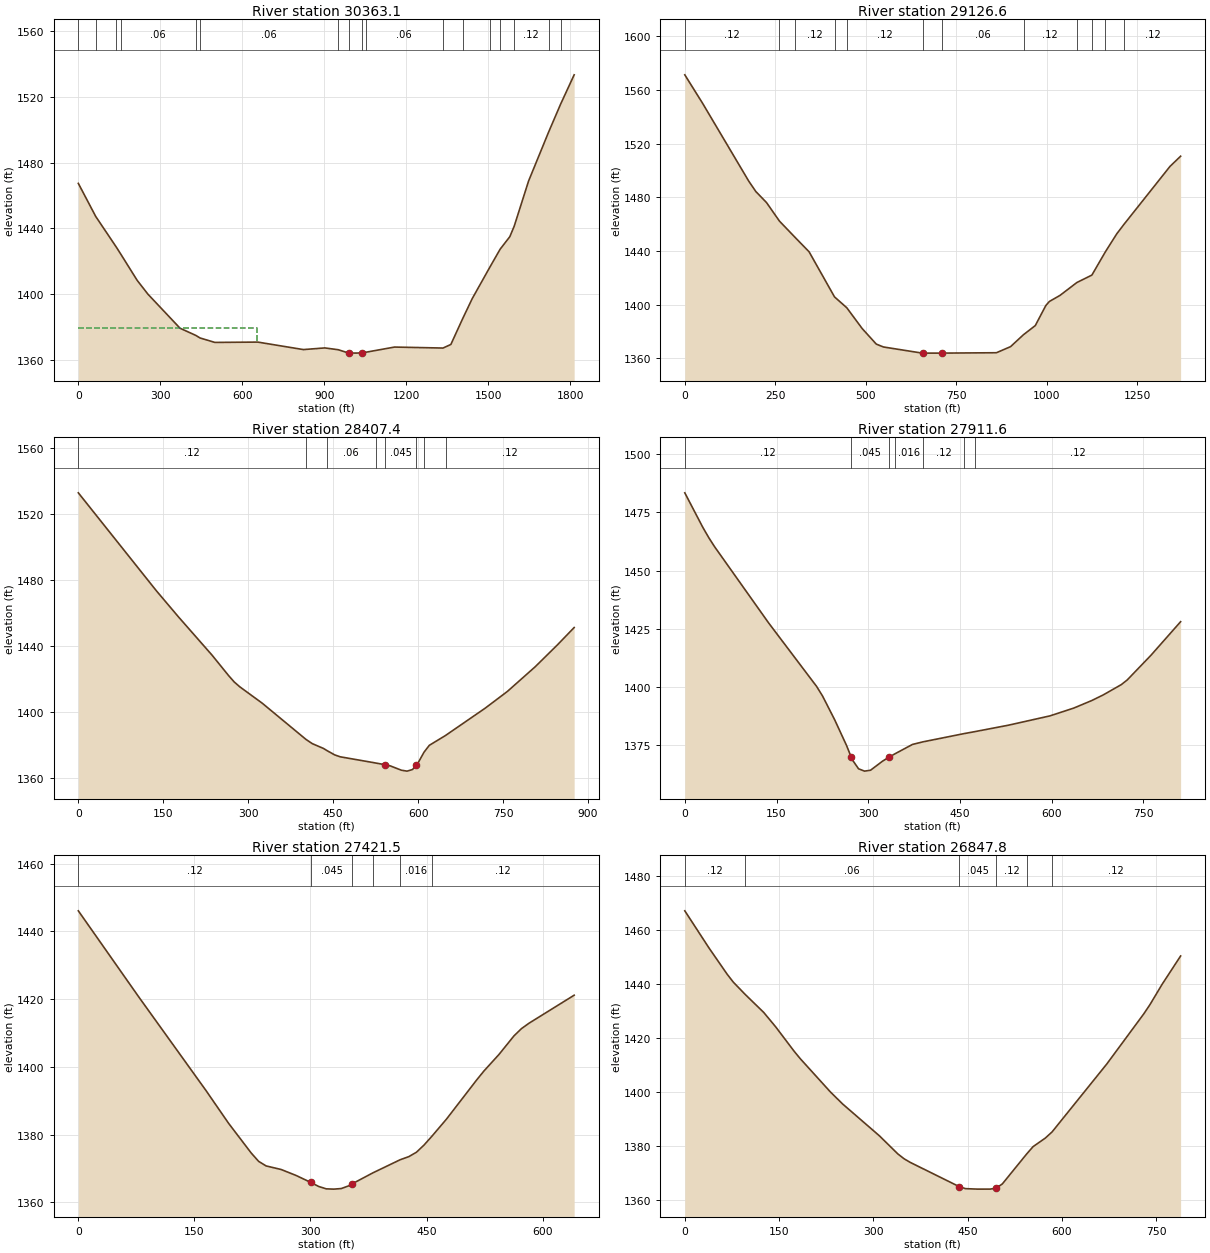
Type RM Length L Ch R = 1 ,30363.1 ,1264.9,1236.5,1196.6
XS GIS Cut Line= 3
     1854788.098      242425.503     1854829.765      242795.294
     1855647.473      243982.794
#Sta/Elev= 30
       0 1467.28   63.631447.152  138.641428.554  155.321424.198   215.4  1408.2
   254.6 1399.82   372.1 1379.07   429.51374.727   445.21373.142   499.6 1370.43
   656.6 1370.63   823.3 1366.07   901.8 1367.08  950.661365.986     990 1363.91
  1039.1    1364 1050.971364.428  1156.8  1367.6 1334.041367.005  1362.8 1369.18
    14061384.896  1441.2 1397.16  1505.31416.211 1543.181427.227  1578.5 1434.82
 1594.491441.164  1647.2 1468.74 1720.04 1498.36 1764.53 1515.61  1813.9  1533.4
#Mann= 17 ,-1 , 0
       0     .12       0   63.63     .06       0  138.64     .12       0
  155.32     .06       0   429.5     .12       0   445.2     .06       0
  950.66     .12       0     990    .045       0  1039.1     .12       0
 1050.97     .06       0 1334.04     .12       0    1406     .06       0
  1505.3     .12       0 1543.18    .016       0 1594.49     .12       0
 1720.04    .016       0 1764.53     .12       0
#XS Ineff= 2 , 0
          652.22 1379.16
Permanent Ineff=
       F       F
Bank Sta=990,1039.1
XS Rating Curve= 0 ,0
Exp/Cntr=0.3,0.1

Type RM Length L Ch R = 1 ,29126.6 ,719.2,719.2,724.6
XS GIS Cut Line= 4
     1854204.765      244133.836     1854574.557      243951.544
     1855168.307      243998.419     1855506.848      244128.628
#Sta/Elev= 30
       0 1571.31    49.1 1550.14   176.7 1492.12   196.3 1484.36   225.8 1476.14
  261.761462.265  305.25 1450.05   343.6 1439.42  413.831405.825  447.84  1397.7
   490.4 1382.19   529.4 1370.61     549 1368.49   656.4  1363.9     658  1363.9
   710.1 1363.91   861.4 1364.19   900.5 1368.73  936.331377.651   968.8 1384.41
   998.1 1399.42  1007.9 1402.41  1037.3 1406.95 1083.741416.511 1125.291422.056
 1162.881439.521  1194.1 1452.82 1214.751460.125  1341.2 1503.05  1370.6 1510.66
#Mann= 12 ,-1 , 0
       0     .12       0  261.76    .016       0  305.25     .12       0
  413.83    .016       0  447.84     .12       0     658    .045       0
   710.1     .06       0  936.33     .12       0 1083.74    .016       0
 1125.29     .12       0 1162.88    .016       0 1214.75     .12       0
Bank Sta=658,710.1
XS Rating Curve= 0 ,0
Exp/Cntr=0.3,0.1

Type RM Length L Ch R = 1 ,28407.4 ,477.1,495.8,514.5
XS GIS Cut Line= 2
     1854387.057      244493.211     1855241.223      244685.919
#Sta/Elev= 30
       0 1532.83   137.7 1473.44   177.1 1457.44   236.1 1434.35   265.6 1421.83
   275.5 1417.99   285.3 1415.07   324.7 1405.19  401.951383.214   413.2 1380.62
   432.9 1377.71  438.531376.532   452.6 1373.82   462.4 1372.65  525.161368.875
   541.1 1367.88     551 1367.12   570.6 1364.49   580.5 1363.95   590.3 1364.94
  596.81 1367.79   600.2 1369.08  610.461375.426   619.8  1379.6  648.421385.575
   718.2 1402.08   757.6 1412.28   806.8 1427.28   846.1 1440.58   875.6 1451.08
#Mann= 8 ,-1 , 0
       0     .12       0  401.95    .016       0  438.53     .06       0
  525.16     .12       0   541.1    .045       0  596.81     .12       0
  610.46    .016       0  648.42     .12       0
Bank Sta=541.1,596.81
XS Rating Curve= 0 ,0
Exp/Cntr=0.3,0.1

Type RM Length L Ch R = 1 ,27911.6 ,487.5,490.2,492.6
XS GIS Cut Line= 3
     1854413.098      244784.878     1854819.348      245139.044
     1855090.182      245113.003
#Sta/Elev= 30
       0 1483.38    29.4 1468.59    39.2 1464.14      49 1460.14   137.2 1427.49
   215.6 1400.26   225.4  1396.1     245 1386.02   264.6 1374.88  272.14 1369.94
   274.4 1368.62   284.2 1364.89     294 1363.89   303.8 1364.27   323.4 1368.16
   333.2 1369.76  344.361371.408   372.4 1375.35   389.41376.448   456.61379.988
  474.971380.874   529.2  1383.6   597.3 1387.61   636.1 1390.95   665.3 1394.15
   684.7 1396.65   713.9 1401.02   723.6 1403.02   762.4 1413.61     811 1428.05
#Mann= 7 ,-1 , 0
       0     .12       0  272.14    .045       0   333.2     .12       0
  344.36    .016       0   389.4     .12       0   456.6     .06       0
  474.97     .12       0
Bank Sta=272.14,333.2
XS Rating Curve= 0 ,0
Exp/Cntr=0.3,0.1

Type RM Length L Ch R = 1 ,27421.5 ,570.8,573.7,576.6
XS GIS Cut Line= 2
     1854163.098      245170.294     1854616.223      245623.419
#Sta/Elev= 30
       0 1446.07    77.7 1420.78   165.1 1392.98   194.2 1383.34   223.3 1374.61
     233 1372.11   242.7 1370.76   262.2  1369.7   281.6 1367.93   300.5 1365.88
   310.7 1364.69   320.4 1363.99   330.1 1363.91   339.8 1364.08   349.5 1364.88
   353.9 1365.47  380.821368.729  415.911372.583   427.2 1373.51   436.9 1374.79
   446.6 1376.88  457.091379.557   475.8 1384.58   514.6 1396.08   524.3 1398.81
   543.7 1403.68   563.1 1409.17   572.8 1411.31   582.6 1412.91   640.8 1421.16
#Mann= 6 ,-1 , 0
       0     .12       0   300.5    .045       0   353.9     .06       0
  380.82     .12       0  415.91    .016       0  457.09     .12       0
Bank Sta=300.5,353.9
XS Rating Curve= 0 ,0
Exp/Cntr=0.3,0.1

Type RM Length L Ch R = 1 ,26847.8 ,594.6,607.3,619.8
XS GIS Cut Line= 3
     1853798.515      245336.961      1853814.14      245597.378
      1854157.89      245998.419
#Sta/Elev= 30
       0 1467.04    38.6 1453.25    67.6 1443.49    77.3 1440.59   96.181436.045
   125.6 1429.39   144.9 1423.97   173.9 1415.04   183.6 1412.29   231.9 1399.88
   251.2 1395.46   309.8 1383.65   339.1 1376.95   348.9 1375.17   358.7 1373.83
     437 1364.81   446.7 1364.09   466.3 1363.91   485.9 1363.92   495.6 1364.26
   505.4 1365.85  543.891376.879   554.3 1379.66   573.9 1382.85  584.481385.101
   671.7 1410.31   730.4 1428.84   740.2 1432.24   759.7 1439.83   789.1 1450.31
#Mann= 6 ,-1 , 0
       0     .12       0   96.18     .06       0     437    .045       0
   495.6     .12       0  543.89    .016       0  584.48     .12       0
Bank Sta=437,495.6
XS Rating Curve= 0 ,0
Exp/Cntr=0.3,0.1