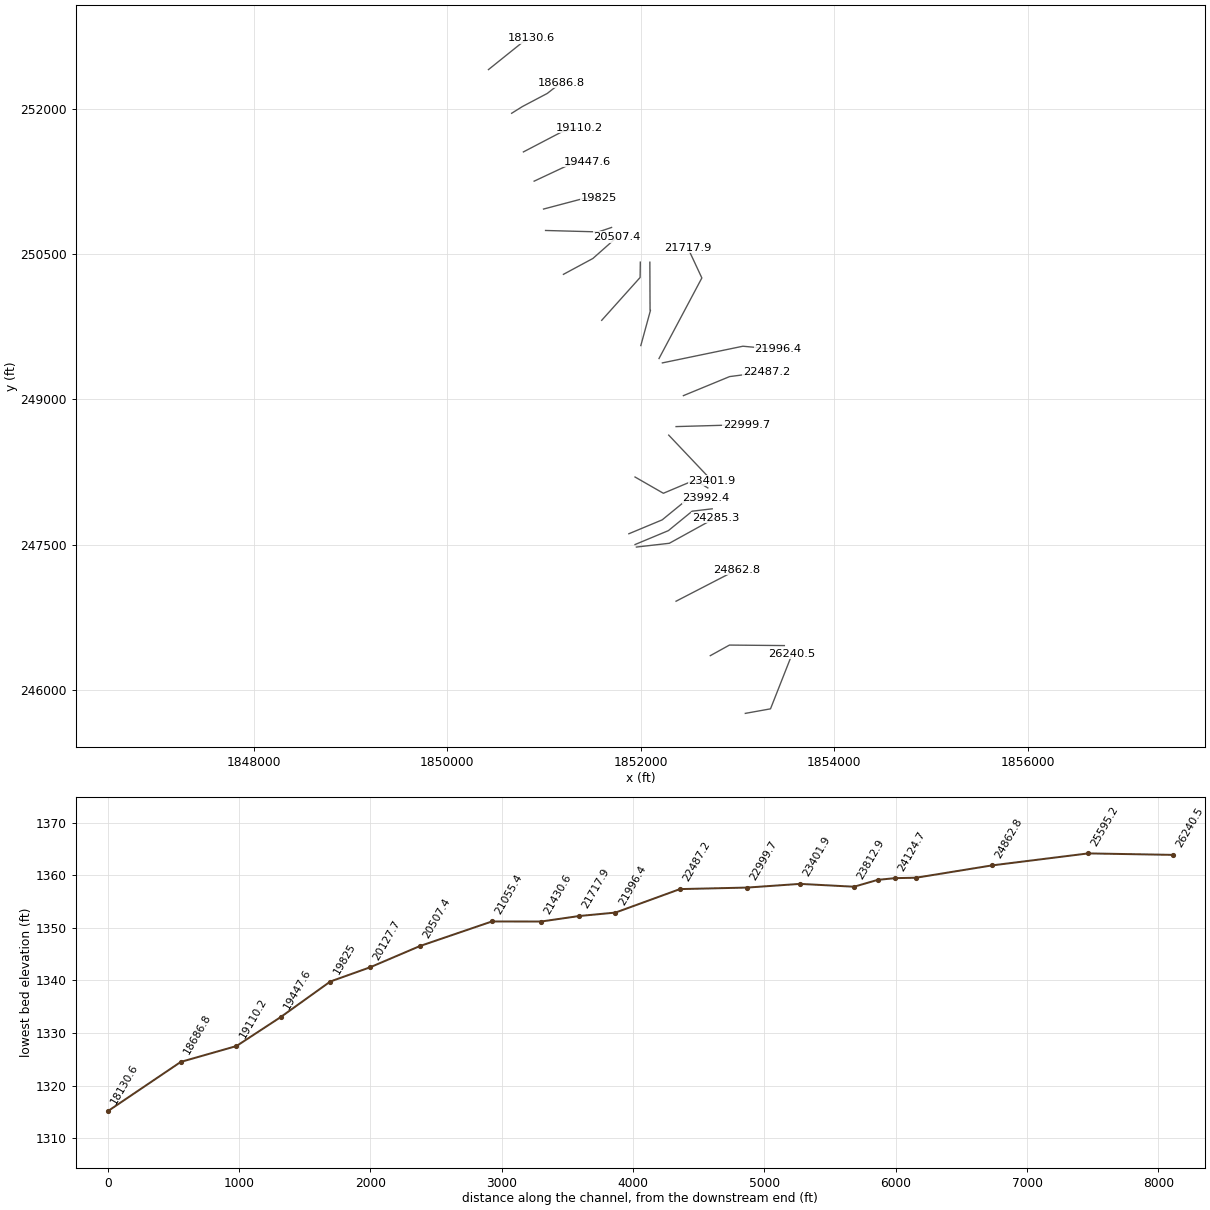
HEC-RAS study TETERCK.prj: TETERCK

--- TETERCK.g01 (geometry) --- (continued)

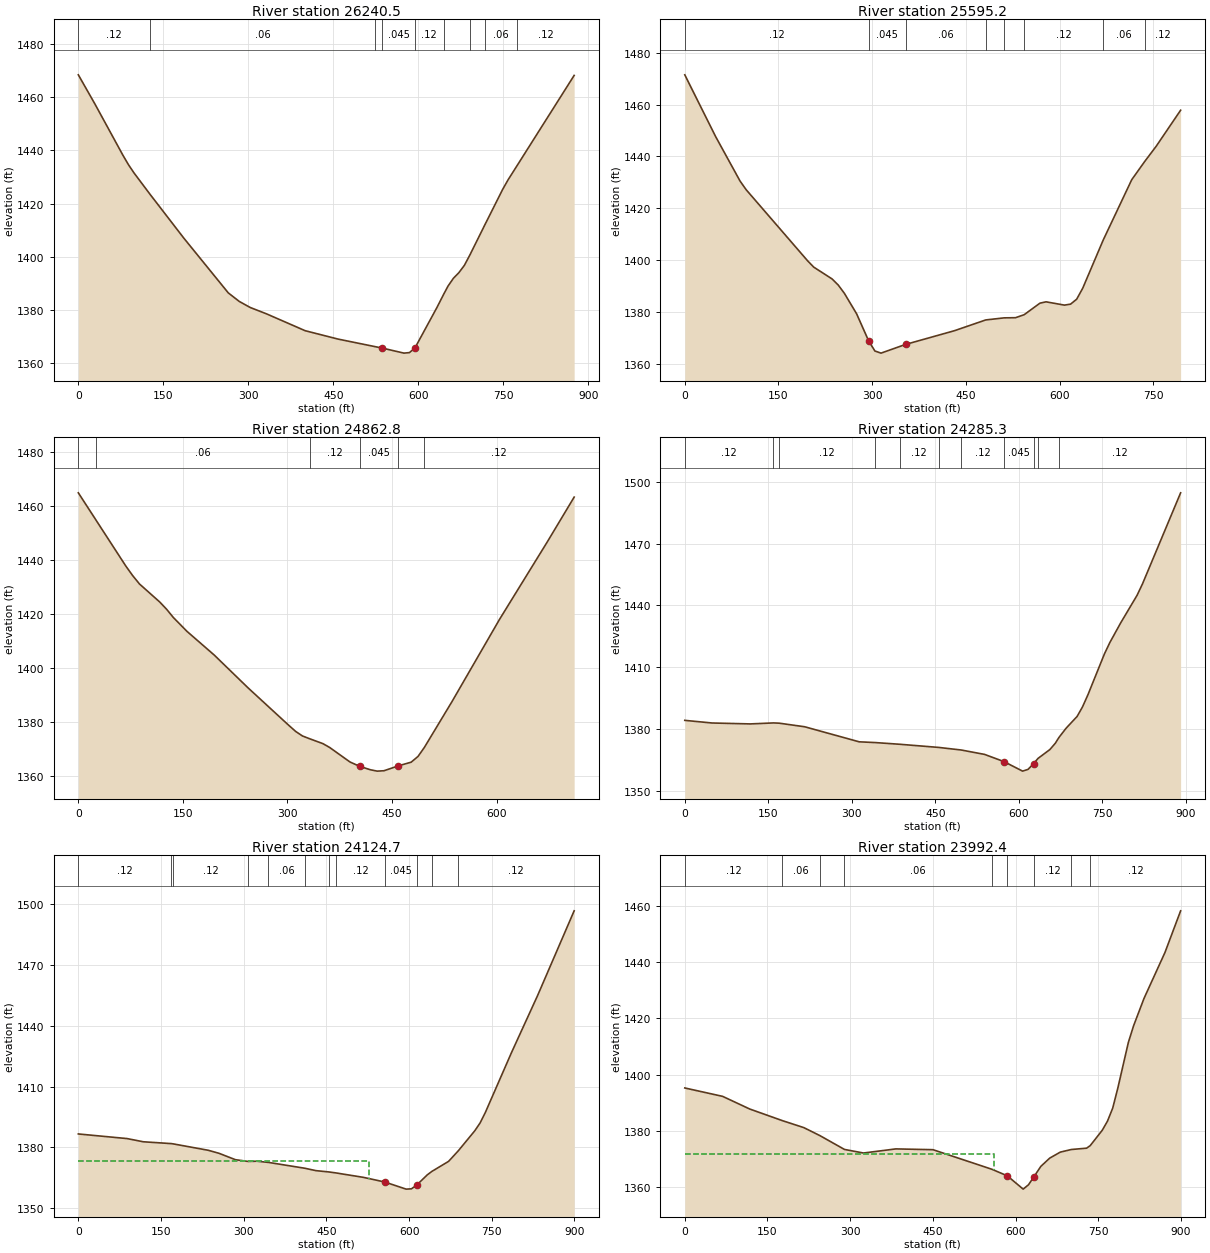
Type RM Length L Ch R = 1 ,26240.5 ,691.1,645.3,599.6
XS GIS Cut Line= 3
     1853082.369      245756.232     1853342.786      245803.107
     1853566.744      246370.815
#Sta/Elev= 30
       0 1468.32    29.4 1457.33    78.4 1438.25    88.2 1434.68      98 1431.57
  126.111423.595   186.2 1407.01   264.6 1386.47     284 1383.26   303.4 1380.98
   332.4 1378.57   400.2 1372.28   458.3 1369.13  523.391366.306   535.8 1365.78
   574.6 1363.86   584.3 1364.06     594 1365.81   632.7 1380.96  644.411385.848
   652.1 1388.94   661.8 1391.95   671.5 1394.06   681.2 1396.81  691.151400.799
  717.321412.018     749 1425.42   758.6 1429.01  774.021434.182   874.9  1468.1
#Mann= 9 ,-1 , 0
       0     .12       0  126.11     .06       0  523.39     .12       0
   535.8    .045       0     594     .12       0  644.41    .016       0
  691.15     .12       0  717.32     .06       0  774.02     .12       0
Bank Sta=535.8,594
XS Rating Curve= 0 ,0
Exp/Cntr=0.3,0.1

Type RM Length L Ch R = 1 ,25595.2 ,713.4,732.4,750.8
XS GIS Cut Line= 3
      1852720.39      246352.586     1852918.307      246461.961
     1853486.015      246456.753
#Sta/Elev= 30
       0 1471.45    49.2 1447.71    88.5 1430.48    98.3 1427.14   196.6 1399.75
   206.5  1397.3   235.9 1392.73   245.7 1390.39   255.5 1387.21   275.1 1379.31
   294.6 1368.75   304.4 1364.96   314.2 1364.14   353.4 1367.49   431.7 1372.78
   481.81376.931  511.341377.739   529.6  1377.8  543.331378.949   568.7 1383.41
   578.5 1383.92   607.9 1382.65   617.7 1383.03   627.5 1384.94   637.2  1389.2
  669.971407.751   715.6    1431  736.271437.993   754.7 1443.88   793.9  1457.8
#Mann= 8 ,-1 , 0
       0     .12       0   294.6    .045       0   353.4     .06       0
   481.8     .12       0  511.34    .016       0  543.33     .12       0
  669.97     .06       0  736.27     .12       0
Bank Sta=294.6,353.4
XS Rating Curve= 0 ,0
Exp/Cntr=0.3,0.1

Type RM Length L Ch R = 1 ,24862.8 ,576.4,577.5,578.5
XS GIS Cut Line= 2
     1852366.223      246915.086     1852998.168      247241.475
#Sta/Elev= 30
       0 1464.89   25.921454.572    68.2 1437.75      78 1434.23    87.7 1431.15
   116.9 1424.44   126.7 1421.76   136.4 1418.71   155.9 1413.59   194.9 1404.84
   243.6 1392.65     302 1378.78   311.8 1376.55   321.5 1374.88  331.681373.858
   350.8 1372.04   360.5 1370.62   389.7 1365.24   403.6 1363.63     419 1362.36
   428.7 1361.86   438.4    1362   459.1 1363.82   477.4 1365.17   487.2 1367.29
   496.3 1370.62   535.9 1387.57   604.1 1418.02   672.3 1446.57   711.2 1463.31
#Mann= 6 ,-1 , 0
       0     .12       0   25.92     .06       0  331.68     .12       0
   403.6    .045       0   459.1    .016       0   496.3     .12       0
Bank Sta=403.6,459.1
XS Rating Curve= 0 ,0
Exp/Cntr=0.3,0.1

Type RM Length L Ch R = 1 ,24285.3 ,153.8,160.6,168
XS GIS Cut Line= 3
     1851956.397      247474.723     1852296.762      247513.681
     1852776.554      247778.181
#Sta/Elev= 30
       0 1384.17    48.9 1382.89   117.5 1382.44  158.961382.921   169.41382.805
   215.3 1381.06   313.2 1373.75     3421373.386  386.441372.553  456.021371.029
  496.491369.773   538.3 1367.65  573.19 1364.15   606.7 1359.52   616.5 1360.37
   626.3 1363.12  634.451365.706   655.7    1370   665.4 1373.04  672.08 1375.91
     685 1380.41   704.6 1386.07   714.4 1390.77   724.1 1396.64   753.5 1416.33
   763.3 1421.91   782.8 1431.47   812.2 1444.85     822 1450.42   890.5 1494.64
#Mann= 11 ,-1 , 0
       0     .12       0  158.96     .06       0   169.4     .12       0
     342    .016       0  386.44     .12       0  456.02     .06       0
  496.49     .12       0  573.19    .045       0   626.3     .12       0
  634.45    .016       0  672.08     .12       0
Bank Sta=573.19,626.3
XS Rating Curve= 0 ,0
Exp/Cntr=0.3,0.1

Type RM Length L Ch R = 1 ,24124.7 ,132.3,132.3,132.3
XS GIS Cut Line= 4
     1851942.456      247500.761     1852286.922      247644.288
     1852532.969      247845.227     1852740.059      247869.831
#Sta/Elev= 30
       0 1386.68    88.4  1384.4   117.8 1382.82  168.641381.915  172.561381.759
   235.7 1378.62   255.3 1377.12   284.8 1373.98  308.06 1373.11   324.1 1373.22
  344.781372.641  411.04 1369.74   430.9 1368.57  454.261367.933  467.341367.438
   517.6 1365.23   556.1 1362.93   594.6 1359.44   604.2 1359.59   613.8 1361.43
   633.1 1366.52  641.621368.242   671.6 1373.14  689.41 1378.42   719.3  1388.3
   728.8 1392.12   738.2 1397.23   785.6 1426.77     833 1454.97   899.4 1496.85
#Mann= 12 ,-1 , 0
       0     .12       0  168.64     .06       0  172.56     .12       0
  308.06    .016       0  344.78     .06       0  411.04     .12       0
  454.26     .06       0  467.34     .12       0   556.1    .045       0
   613.8     .12       0  641.62    .016       0  689.41     .12       0
#XS Ineff= 2 , 0
          527.35 1373.24
Permanent Ineff=
       F       F
Bank Sta=556.1,613.8
XS Rating Curve= 0 ,0
Exp/Cntr=0.3,0.1

Type RM Length L Ch R = 1 ,23992.4 ,190.2,179.5,168.1
XS GIS Cut Line= 4
     1851878.482      247612.099     1852222.948      247755.627
     1852468.995      247956.565     1852676.085       247981.17
#Sta/Elev= 30
       0  1395.2    68.7  1392.2   117.8 1387.69  177.061383.543     216 1381.05
   245.61378.147  289.581373.277   324.1 1371.99   382.8 1373.46   450.2 1373.18
  557.091366.193     585 1363.86   613.8 1359.11   623.5 1360.67   633.1 1363.48
   645.8 1367.22     662 1370.18   681.2 1372.32  701.081373.245   728.8 1373.72
  735.311374.606   757.2  1380.1   766.7 1383.36   776.2    1388   785.6 1395.24
   804.6 1411.46   814.1  1417.4     833 1427.16     871 1443.54   899.4  1458.4
#Mann= 9 ,-1 , 0
       0     .12       0  177.06     .06       0   245.6     .12       0
  289.58     .06       0  557.09     .12       0     585    .045       0
   633.1     .12       0  701.08    .016       0  735.31     .12       0
#XS Ineff= 2 , 0
          560.37 1371.62
Permanent Ineff=
       F       F
Bank Sta=585,633.1
XS Rating Curve= 0 ,0
Exp/Cntr=0.3,0.1

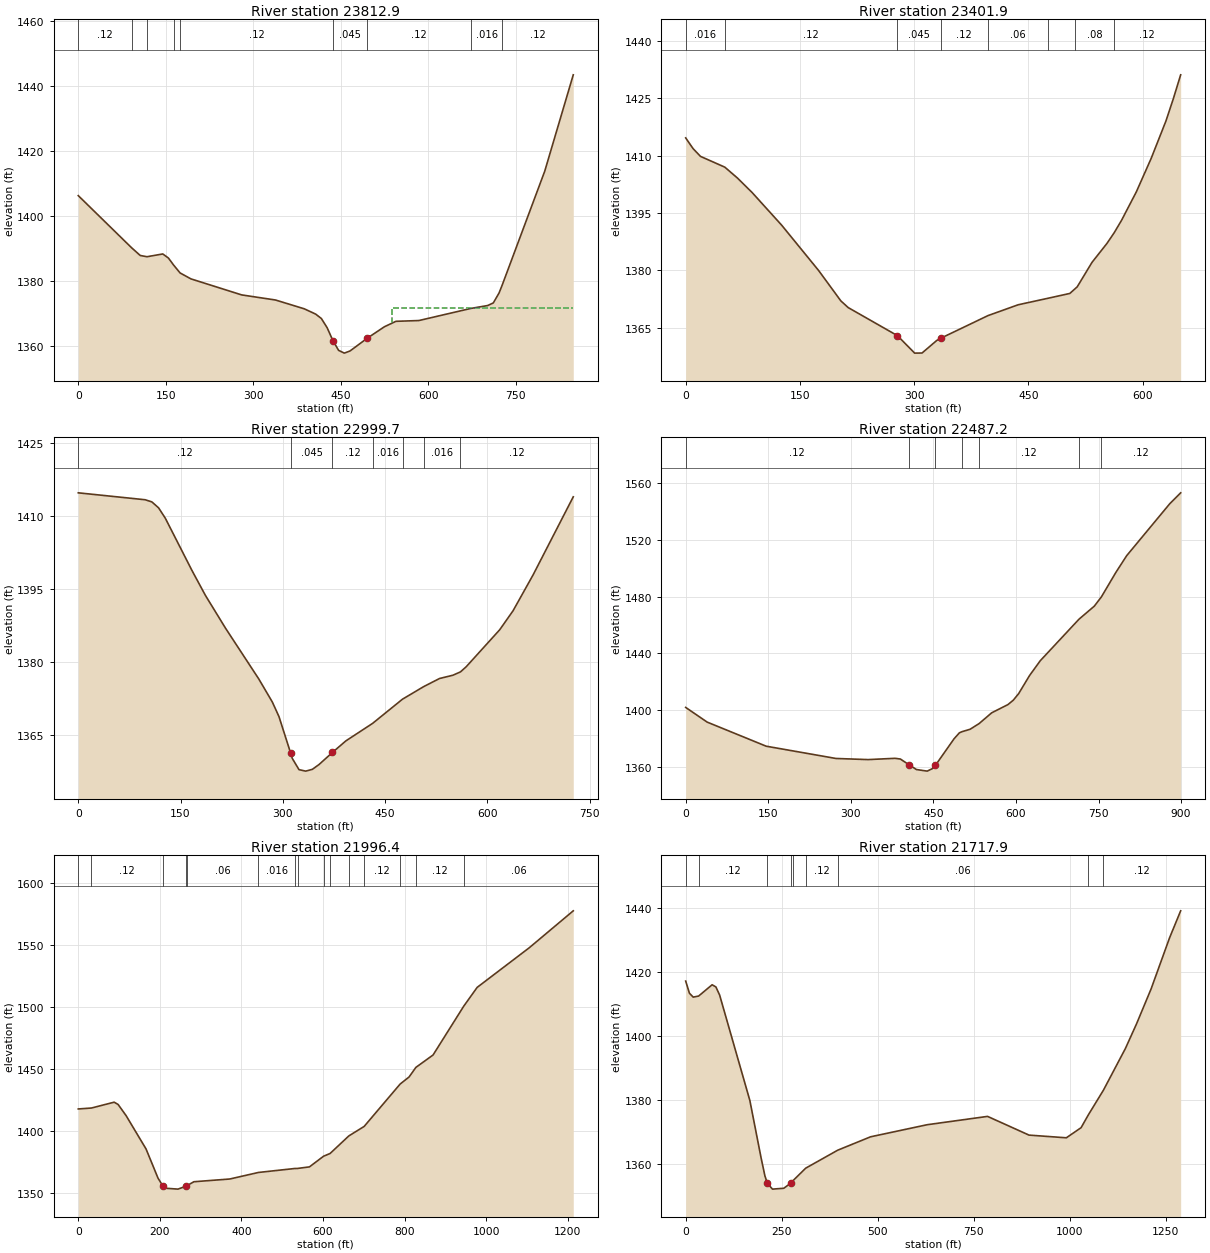
Type RM Length L Ch R = 1 ,23812.9 ,456.8,411,365.2
XS GIS Cut Line= 4
     1851942.044      248198.512      1852235.25      248030.379
     1852561.263      248167.756     1852694.538       248085.74
#Sta/Elev= 30
       0  1406.2   91.321390.193   106.2 1387.81  117.851387.431   144.8 1388.28
   154.5 1387.02  163.431384.857  174.461382.445   193.1 1380.62     280  1375.7
     338 1374.13   387.1 1371.44   406.8  1369.8   416.6 1368.44   426.4 1365.65
   436.3 1361.69   446.1 1358.67   455.9 1357.81   465.7 1358.47   495.2 1362.39
   524.7 1365.92   544.4 1367.58   583.7 1367.82  672.881371.549   701.6 1372.43
   711.3 1373.24   721.1 1376.28  726.331378.628   799.4 1413.71   848.3 1443.32
#Mann= 9 ,-1 , 0
       0     .12       0   91.32     .06       0  117.85    .016       0
  163.43     .06       0  174.46     .12       0   436.3    .045       0
   495.2     .12       0  672.88    .016       0  726.33     .12       0
#XS Ineff= 2 , 0
                          537.67         1371.62
Permanent Ineff=
       F       F
Bank Sta=436.3,495.2
XS Rating Curve= 0 ,0
Exp/Cntr=0.3,0.1

Type RM Length L Ch R = 1 ,23401.9 ,369.9,402.2,434.1
XS GIS Cut Line= 2
     1852290.611      248631.145     1852737.597      248159.554
#Sta/Elev= 30
       0 1414.67     9.7 1411.87    19.4 1409.84   51.341407.021    67.9 1404.18
    87.3 1400.36   126.1 1391.81   174.6 1379.95   203.7 1372.02   213.4 1370.26
     278 1362.92   300.6 1358.35   310.3 1358.38   329.7 1361.68   334.6 1362.22
  396.811368.165   436.4    1371  476.281372.736   504.3 1373.97  511.641375.279
     514  1375.7   533.4  1382.1   552.8    1387  562.351389.796   572.2 1393.11
   591.6 1400.55     611 1409.27   630.4 1419.06   640.1 1424.88   649.8 1431.18
#Mann= 8 ,-1 , 0
       0    .016       0   51.34     .12       0     278    .045       0
   334.6     .12       0  396.81     .06       0  476.28    .016       0
  511.64     .08       0  562.35     .12       0
Bank Sta=278,334.6
XS Rating Curve= 0 ,0
Exp/Cntr=0.3,0.1

Type RM Length L Ch R = 1 ,22999.7 ,498.4,512.5,526.1
XS GIS Cut Line= 2
     1852366.476      248719.311     1853092.315      248739.815
#Sta/Elev= 30
       0 1414.74    98.1 1413.32   107.9 1412.88   117.8 1411.66   127.6 1409.55
   166.8  1398.8   186.4 1393.72   215.9 1386.99   264.9 1376.53   284.6 1371.84
   294.4 1368.84  311.31 1361.44     314 1360.24   323.8 1357.95   333.6 1357.65
   343.4 1358.02   353.2 1359.01   372.9 1361.49   392.5 1363.85  431.791367.449
  475.62 1372.41  506.641374.984   529.9 1376.65   549.5 1377.32  560.641378.008
   569.1 1379.07   618.2 1386.65   637.8 1390.55   667.2 1397.91   726.1 1413.92
#Mann= 7 ,-1 , 0
       0     .12       0  311.31    .045       0   372.9     .12       0
  431.79    .016       0  475.62     .06       0  506.64    .016       0
  560.64     .12       0
Bank Sta=311.31,372.9
XS Rating Curve= 0 ,0
Exp/Cntr=0.3,0.1

Type RM Length L Ch R = 1 ,22487.2 ,497.3,490.8,483.3
XS GIS Cut Line= 3
      1852442.34      249039.173     1852920.082       249236.01
     1853299.404       249285.22
#Sta/Elev= 30
       0 1402.11      39  1391.8   146.2 1374.88     273 1366.25   331.5 1365.46
   380.2 1366.36     390 1365.86   405.6 1361.86   419.2 1358.48   438.7 1357.36
   448.5 1359.18  453.75 1361.45   487.5 1380.06   497.2 1384.25  501.941385.077
   516.7 1386.78  533.171390.807   555.9 1398.33   585.4  1404.1   595.2 1407.22
     605 1411.88   624.6 1424.47   644.2 1434.95  714.571464.121   742.3 1473.26
  755.371479.879   781.5 1496.97   801.1 1508.71   879.6 1545.31   899.2 1552.88
#Mann= 7 ,-1 , 0
       0     .12       0   405.6    .045       0  453.75     .12       0
  501.94    .016       0  533.17     .12       0  714.57    .016       0
  755.37     .12       0
Bank Sta=405.6,453.75
XS Rating Curve= 0 ,0
Exp/Cntr=0.3,0.1

Type RM Length L Ch R = 1 ,21996.4 ,245.4,278.6,311.8
XS GIS Cut Line= 3
     1852224.999      249377.487     1853057.458       249549.72
     1853419.262      249516.102
#Sta/Elev= 30
       0 1417.53    32.31418.277    87.9 1422.99    97.7 1421.12   117.2 1412.15
   166.1 1385.29   195.4 1361.79     207 1355.59     215  1353.6   244.3  1352.9
   264.7 1355.35  265.271355.491   283.4 1358.85   371.3 1361.05  441.681366.339
  530.221369.507  537.631369.584   566.7 1370.84  601.391379.449  617.211381.617
  663.111395.761  700.771403.437  788.951437.592     811 1443.34  827.531451.017
   869.7 1461.03  945.091500.474   977.8 1515.53  1105.4 1547.44  1213.4 1577.25
#Mann= 15 ,-1 , 0
       0    .016       0    32.3     .12       0     207    .045       0
   264.7     .04       0  265.27     .06       0  441.68    .016       0
  530.22     .06       0  537.63     .12       0  601.39    .016       0
  617.21     .12       0  663.11    .016       0  700.77     .12       0
  788.95    .016       0  827.53     .12       0  945.09     .06       0
Bank Sta=207,264.7
XS Rating Curve= 0 ,0
Exp/Cntr=0.3,0.1

Type RM Length L Ch R = 1 ,21717.9 ,278.8,287.2,295.7
XS GIS Cut Line= 3
     1852190.142      249422.596     1852633.027      250255.055
      1852486.97      250568.185
#Sta/Elev= 30
       0 1417.17     9.8 1413.37    19.6 1412.17   33.591412.496    68.8 1416.02
    78.6 1415.35    88.4  1412.8     167 1379.92   196.4 1361.93   206.3 1356.35
   212.7 1354.03   225.9 1352.24   255.4 1352.51     275 1354.25  279.291354.872
  312.461358.784  395.711364.388   481.3 1368.57   628.6 1372.34   785.8 1374.94
   893.8  1369.1   990.9 1368.26  1029.3 1371.42 1048.021375.388  1087.51383.131
  1144.5  1396.1  1173.3 1403.73  1211.7 1414.78  1259.7  1430.7  1288.5  1439.1
#Mann= 9 ,-1 , 0
       0    .016       0   33.59     .12       0   212.7    .045       0
     275     .04       0  279.29     .06       0  312.46     .12       0
  395.71     .06       0 1048.02    .016       0  1087.5     .12       0
Bank Sta=212.7,275
XS Rating Curve= 0 ,0
Exp/Cntr=0.3,0.1

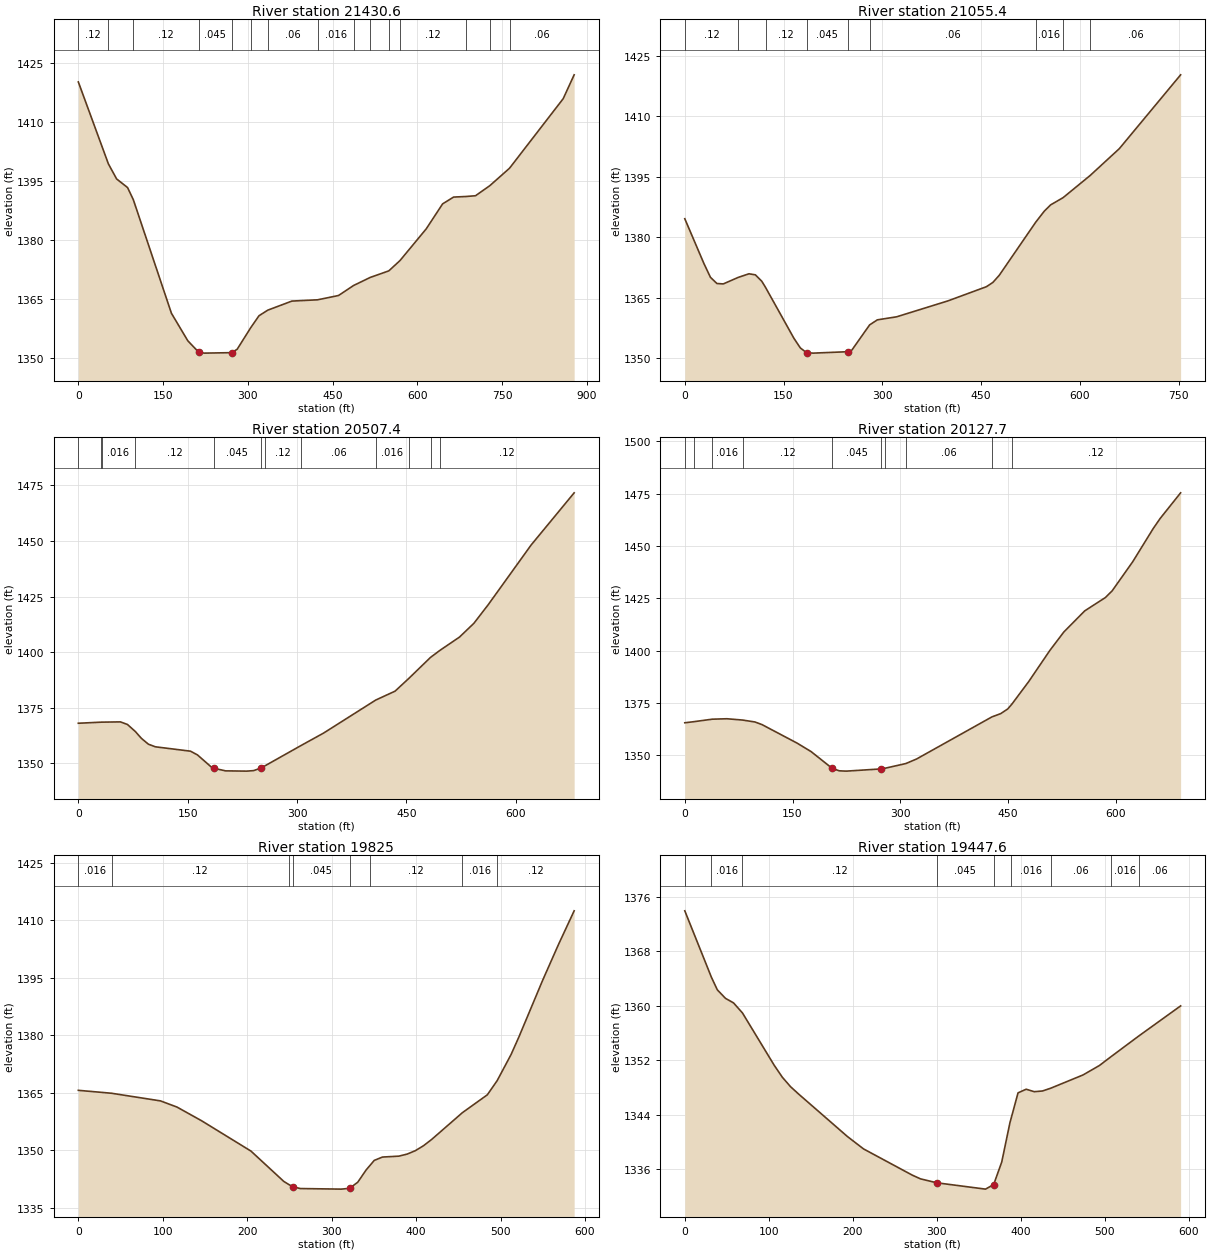
Type RM Length L Ch R = 1 ,21430.6 ,392.8,375.2,357.7
XS GIS Cut Line= 4
       1852002.1      249556.405     1852101.927      249920.989
     1852097.586      249923.159     1852095.416       250417.95
#Sta/Elev= 30
       0  1420.3    53.21399.426    67.8 1395.58    87.2 1393.38   97.411390.269
   164.8 1361.35   193.8 1354.34   213.2 1351.42   222.9  1351.2   271.4 1351.32
   281.1 1352.18  304.771357.598   319.8 1360.73  335.261362.146     378 1364.46
  423.541364.787   460.5 1365.88  487.051368.421  516.591370.484  549.521372.157
  569.331374.782   615.7 1382.85   644.8 1389.23   664.2 1390.96  685.971391.107
     703  1391.3  728.43 1393.88  763.161398.305   858.2 1416.03   877.6 1422.11
#Mann= 15 ,-1 , 0
       0     .12       0    53.2    .016       0   97.41     .12       0
   213.2    .045       0   271.4     .04       0  304.77     .12       0
  335.26     .06       0  423.54    .016       0  487.05     .06       0
  516.59     .12       0  549.52     .06       0  569.33     .12       0
  685.97    .016       0  728.43     .12       0  763.16     .06       0
Bank Sta=213.2,271.4
XS Rating Curve= 0 ,0
Exp/Cntr=0.3,0.1

Type RM Length L Ch R = 1 ,21055.4 ,561,548,534.9
XS GIS Cut Line= 3
     1851597.586      249817.256     1851994.722      250259.964
     1851996.892      250418.384
#Sta/Elev= 30
       0 1384.53    29.2 1373.37      39    1370    48.8 1368.47    58.5 1368.37
   81.211369.989    97.5 1370.88   107.2 1370.62     117 1369.02   122.61367.523
   165.8 1354.88   175.5  1352.5   185.2 1351.29     195 1351.21   247.5 1351.56
   253.5  1351.9  280.781358.212   292.5 1359.46   321.7 1360.21   399.7 1364.16
   458.2 1367.68     468 1368.74   477.7 1370.51  533.051383.666     546 1386.39
   555.7 1387.96  574.651389.755  615.651395.237     660 1401.89   753.2 1420.21
#Mann= 9 ,-1 , 0
       0     .12       0   81.21    .016       0   122.6     .12       0
   185.2    .045       0   247.5     .04       0  280.78     .06       0
  533.05    .016       0  574.65     .12       0  615.65     .06       0
Bank Sta=185.2,247.5
XS Rating Curve= 0 ,0
Exp/Cntr=0.3,0.1

Type RM Length L Ch R = 1 ,20507.4 ,399.2,379.7,360
XS GIS Cut Line= 3
     1851202.187      250292.516     1851506.875      250456.579
     1851756.875      250677.933
#Sta/Elev= 30
       0 1368.06   30.581368.531   31.781368.553    57.7 1368.67    67.3 1367.52
   78.111364.373    86.5 1361.27    96.1 1358.64   105.7 1357.47   153.8 1355.51
   163.4 1353.83   182.6 1348.32  186.15 1347.81   201.9 1346.66   230.7 1346.54
   240.3 1346.76   249.9 1347.86   256.6 1349.04  305.181358.001   336.4 1363.65
  407.921378.489   434.4 1382.48  453.391388.253  483.011397.658  495.85  1400.8
   522.8  1406.8   542.5 1412.98   562.1 1421.32     621 1448.17     680 1471.62
#Mann= 12 ,-1 , 0
       0     .06       0   30.58     .12       0   31.78    .016       0
   78.11     .12       0  186.15    .045       0   249.9     .04       0
   256.6     .12       0  305.18     .06       0  407.92    .016       0
  453.39     .12       0  483.01     .06       0  495.85     .12       0
Bank Sta=186.15,249.9
XS Rating Curve= 0 ,0
Exp/Cntr=0.3,0.1

Type RM Length L Ch R = 1 ,20127.7 ,291.5,302.7,313.2
XS GIS Cut Line= 3
     1851017.291      250745.641     1851564.262      250730.972
     1851699.583      250776.891
#Sta/Elev= 30
       0  1365.6   12.321366.108    38.11367.312    58.6 1367.52   80.351366.904
    97.7 1365.98   107.5 1364.72   156.3 1355.88   175.9 1351.81   205.2 1343.81
     215 1342.65   224.7  1342.5   273.6 1343.56  278.151343.834  307.681346.127
   322.4 1348.26  427.451368.409   439.7 1369.97   449.5 1372.21  455.371374.564
   478.8 1385.35   508.1 1400.16   527.6 1408.99   556.7 1419.08   585.3 1425.41
   594.8 1428.63   623.4 1442.52     652 1458.42   661.5 1463.16   690.1 1475.46
#Mann= 10 ,-1 , 0
       0     .06       0   12.32     .12       0    38.1    .016       0
   80.35     .12       0   205.2    .045       0   273.6     .04       0
  278.15     .12       0  307.68     .06       0  427.45    .016       0
  455.37     .12       0
Bank Sta=205.2,273.6
XS Rating Curve= 0 ,0
Exp/Cntr=0.3,0.1

Type RM Length L Ch R = 1 ,19825   ,370.1,377.4,383.9
XS GIS Cut Line= 3
     1850996.458      250966.995      1851410.52       251076.37
     1851569.375       251076.37
#Sta/Elev= 30
       0 1365.59   39.371364.823    97.3 1362.83   116.8 1361.22     146 1357.64
   204.4 1349.73   243.3 1341.81  249.291340.997   253.9 1340.44   262.8 1339.95
   311.5  1339.8   321.2 1340.01   330.9 1341.61   340.7 1344.78  345.121345.928
   350.4  1347.3   360.1 1348.17   379.6 1348.41   389.3 1348.94   399.1 1349.84
   408.8 1351.14   418.5 1352.79  454.791359.759   484.3 1364.42  495.931368.113
   512.4 1374.93   521.7 1379.53   549.7 1394.26   568.4 1403.58   587.1 1412.44
#Mann= 8 ,-1 , 0
       0    .016       0   39.37     .12       0  249.29     .04       0
   253.9    .045       0   321.2     .04       0  345.12     .12       0
  454.79    .016       0  495.93     .12       0
Bank Sta=253.9,321.2
XS Rating Curve= 0 ,0
Exp/Cntr=0.3,0.1

Type RM Length L Ch R = 1 ,19447.6 ,335.5,337.4,338.7
XS GIS Cut Line= 3
     1850899.236       251255.19     1851284.652      251435.745
     1851447.847      251456.579
#Sta/Elev= 30
       0 1373.92   31.691364.163    38.7 1362.32    48.4 1361.07      58  1360.4
   68.631358.925   106.4 1351.24   116.1 1349.48   125.8  1348.1   135.4 1347.02
   193.5 1340.78   212.8 1338.95   270.8  1335.1   280.5 1334.56   299.9 1333.98
   357.9 1333.05   367.6 1333.72   377.2 1337.03   386.9 1342.77  388.341343.426
   396.6 1347.19   406.3 1347.72   415.9 1347.36   425.6 1347.46  435.391347.864
     474 1349.82   493.4  1351.2  507.781352.548  540.251355.533   590.1 1359.96
#Mann= 9 ,-1 , 0
       0     .12       0   31.69    .016       0   68.63     .12       0
   299.9    .045       0   367.6     .04       0  388.34    .016       0
  435.39     .06       0  507.78    .016       0  540.25     .06       0
Bank Sta=299.9,367.6
XS Rating Curve= 0 ,0
Exp/Cntr=0.3,0.1

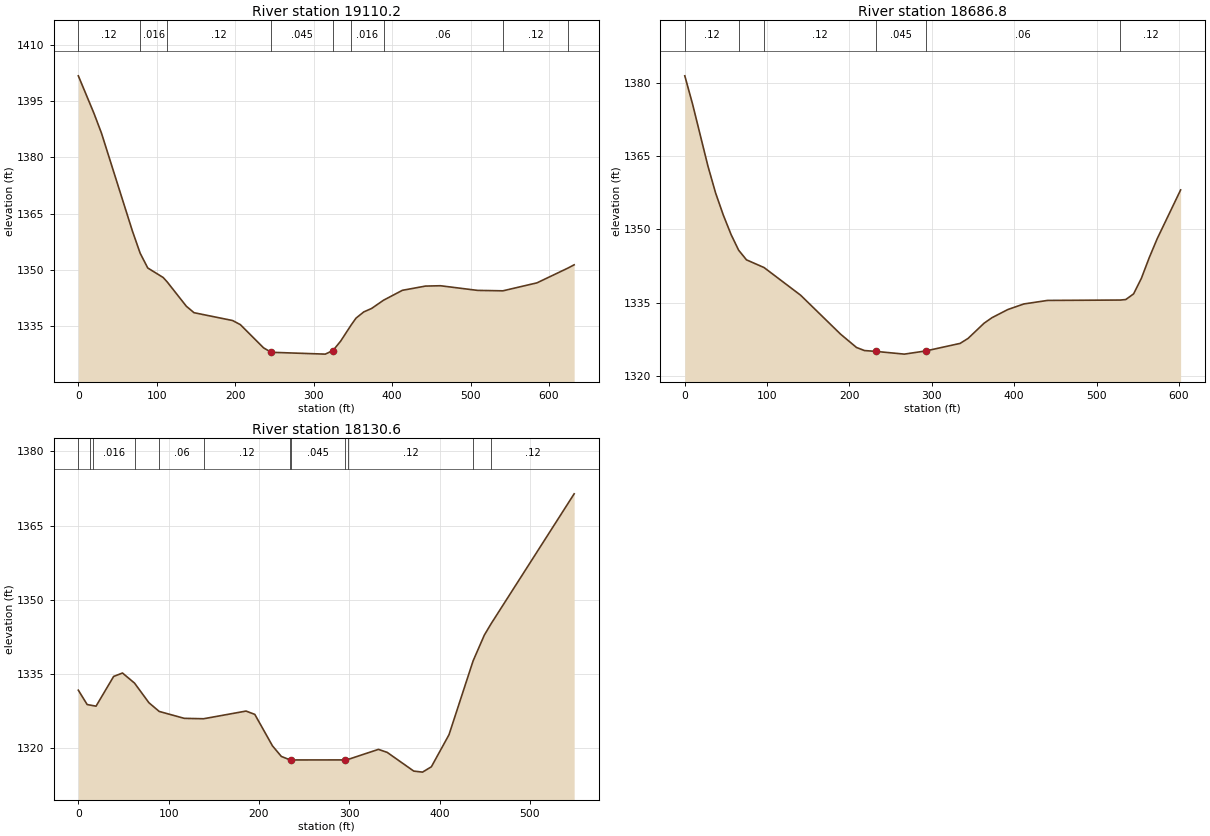
Type RM Length L Ch R = 1 ,19110.2 ,423.5,423.5,423.9
XS GIS Cut Line= 3
     1850788.125      251557.273     1851180.486      251762.134
     1851364.513      251807.273
#Sta/Elev= 30
       0 1401.77    19.7 1391.89    29.5 1386.49    68.8 1360.47   78.781354.477
    88.5 1350.52   108.2 1347.97  113.551346.731   137.7 1340.31   147.5 1338.59
   196.7  1336.5   206.6  1335.4   236.1 1329.22   245.9 1328.03   314.8 1327.54
   324.6 1328.49   334.4    1331  347.891335.335   354.1 1337.16   363.9  1338.8
   373.8 1339.71  389.111341.923   413.1 1344.56   442.6 1345.69   461.6 1345.78
   508.9 1344.54  541.261344.425   584.7 1346.55  624.181350.493   632.1 1351.36
#Mann= 9 ,-1 , 0
       0     .12       0   78.78    .016       0  113.55     .12       0
   245.9    .045       0   324.6     .04       0  347.89    .016       0
  389.11     .06       0  541.26     .12       0  624.18     .06       0
Bank Sta=245.9,324.6
XS Rating Curve= 0 ,0
Exp/Cntr=0.3,0.1

Type RM Length L Ch R = 1 ,18686.8 ,548.7,556.2,563
XS GIS Cut Line= 4
     1850666.597      251956.579     1850777.708      252026.023
     1851034.652       252161.44     1851177.013      252272.551
#Sta/Elev= 30
       0 1381.38     9.4 1375.63    28.1 1362.94    37.4 1357.45    46.8 1352.92
    56.2 1348.96   65.361345.769    74.9 1343.79   96.291342.212   140.7 1336.56
   189.1 1328.62   208.5 1325.89   218.2 1325.26   232.6 1325.08   266.6 1324.53
   292.9 1325.19   334.3 1326.72     344 1327.74   363.4 1330.84   373.1 1331.98
   392.4 1333.65   411.8 1334.78   440.5  1335.5  528.961335.577   535.5 1335.68
     545 1336.84   554.5 1340.04     564 1344.24   573.6 1348.09   602.1 1358.07
#Mann= 6 ,-1 , 0
       0     .12       0   65.36    .016       0   96.29     .12       0
   232.6    .045       0   292.9     .06       0  528.96     .12       0
Bank Sta=232.6,292.9
XS Rating Curve= 0 ,0
Exp/Cntr=0.3,0.1

Type RM Length L Ch R = 1 ,18130.6 ,501.3,505.6,509.1
XS GIS Cut Line= 3
     1850427.013      252407.968     1850777.708      252689.218
     1850867.986      252730.884
#Sta/Elev= 30
       0 1331.72     9.8 1328.82   12.791328.719   16.021328.611    19.6 1328.49
    39.1  1334.5    48.9 1335.19   62.281333.143    78.2 1329.18   89.541327.428
   117.3 1326.03  138.691325.948   185.7  1327.5   195.4 1326.83     215 1320.46
   224.8 1318.33  234.561317.629     235 1317.62   295.7 1317.63  298.91 1317.74
   332.3 1319.76     342 1319.15   371.4 1315.37   381.1 1315.16   390.9 1316.24
   410.4 1322.71  437.091337.636   449.5 1342.84  456.641345.037     549 1371.41
#Mann= 12 ,-1 , 0
       0     .12       0   12.79     .06       0   16.02    .016       0
   62.28     .12       0   89.54     .06       0  138.69     .12       0
  234.56     .04       0     235    .045       0   295.7     .04       0
  298.91     .12       0  437.09     .06       0  456.64     .12       0
Bank Sta=235,295.7
XS Rating Curve= 0 ,0
Exp/Cntr=0.3,0.1