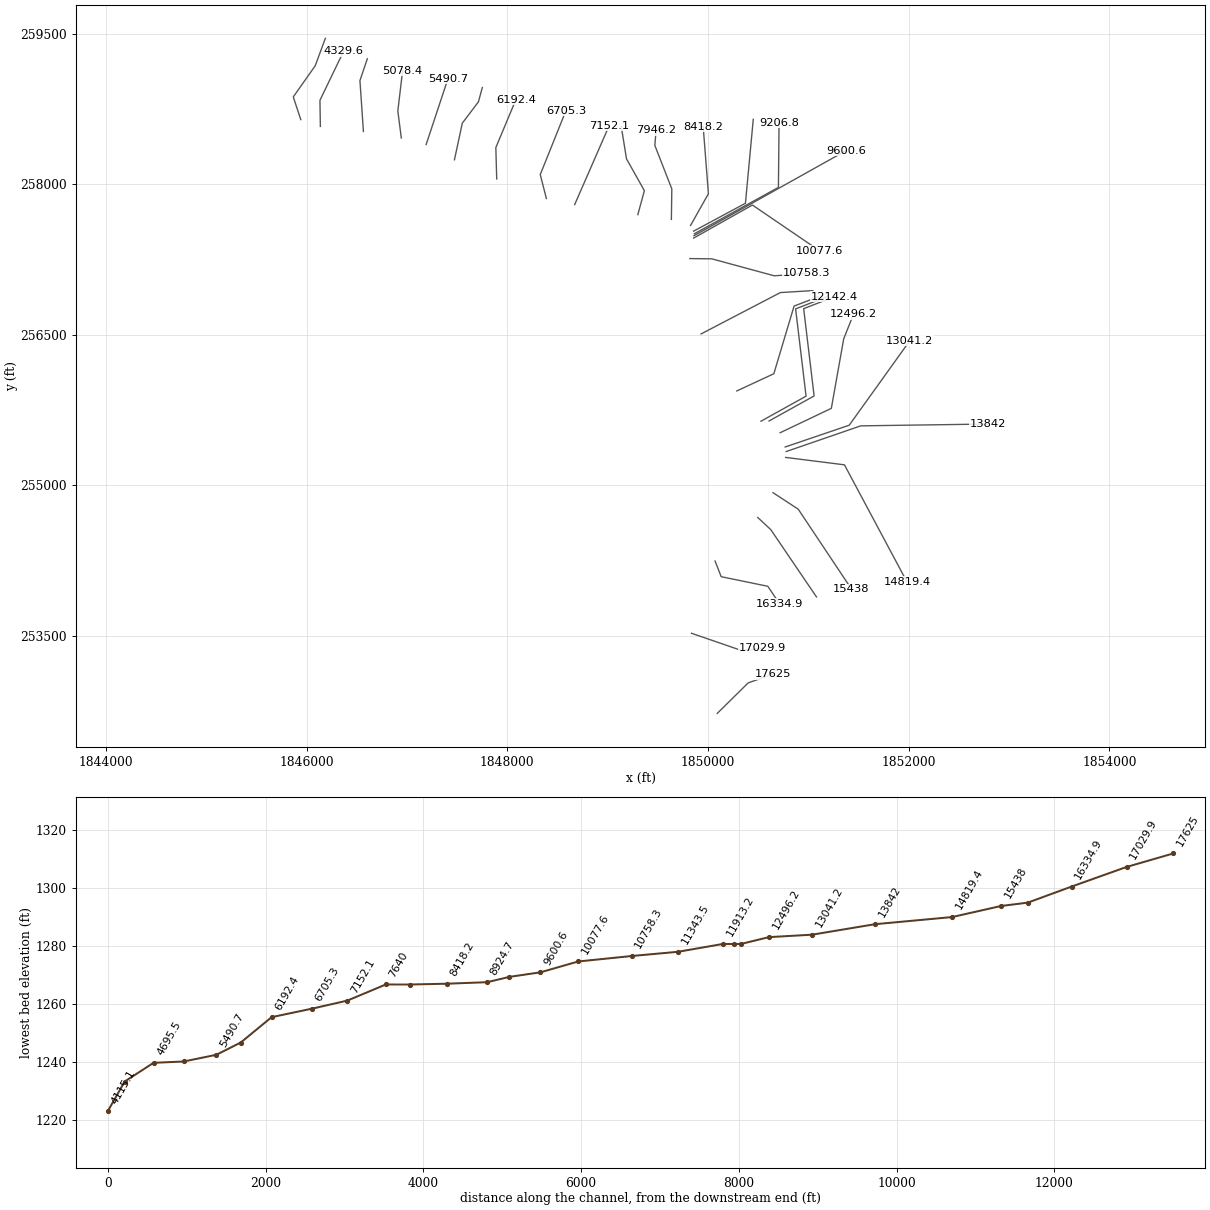
HEC-RAS study TETERCK.prj: TETERCK

--- TETERCK.g01 (geometry) --- (continued)

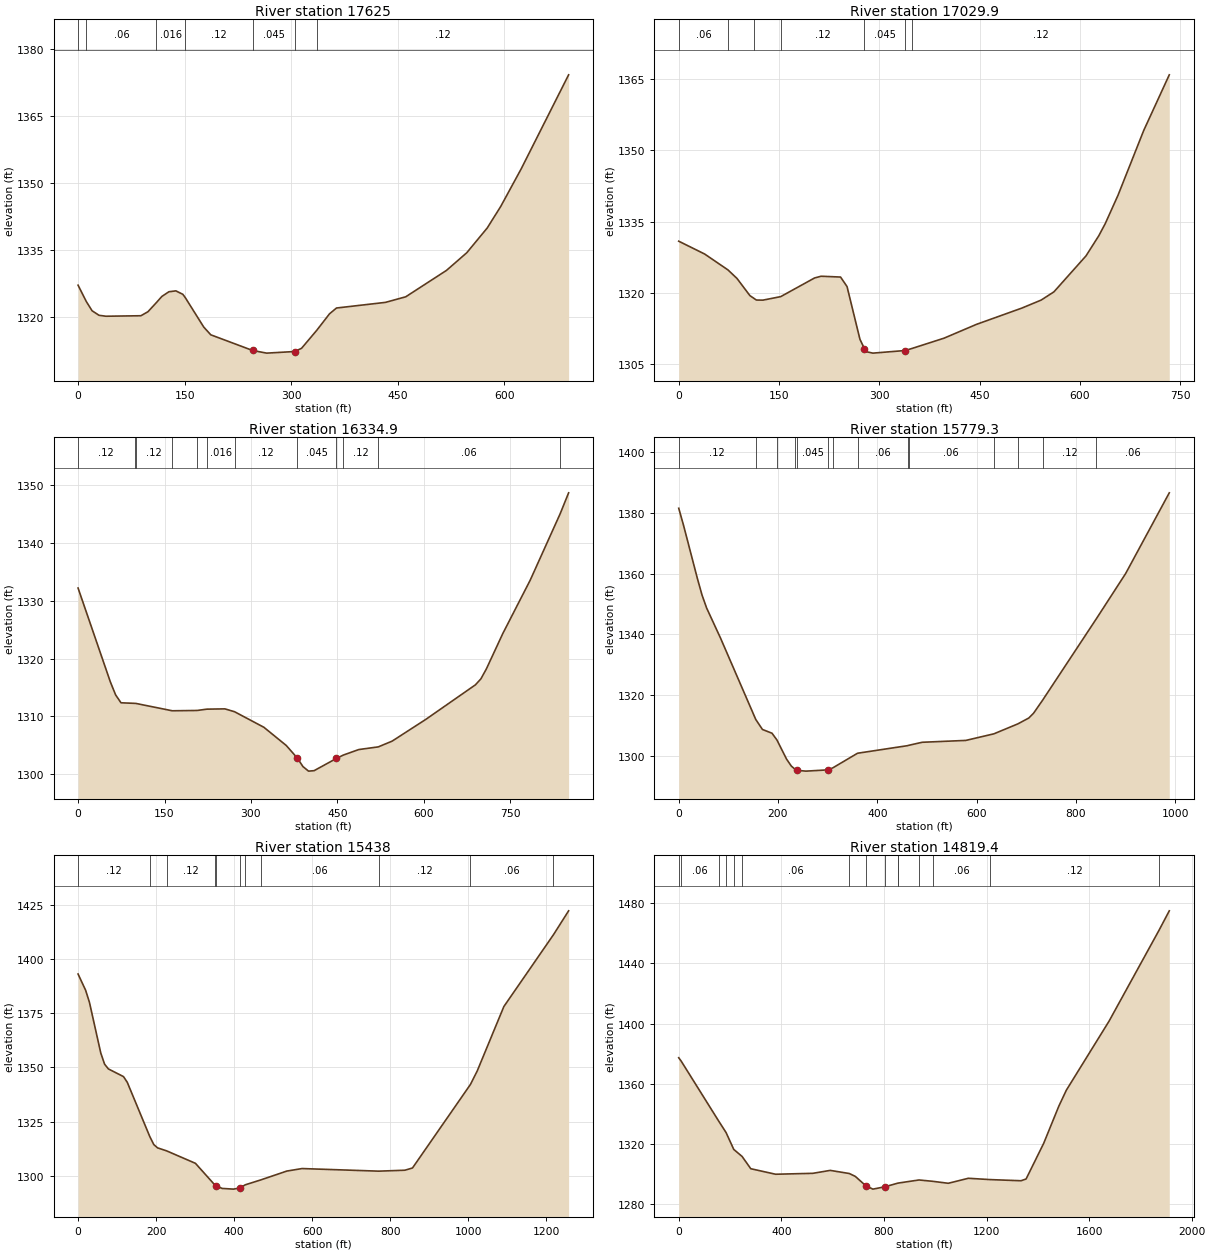
Type RM Length L Ch R = 1 ,17625   ,636.9,595.1,554
XS GIS Cut Line= 3
     1850091.944      252724.808     1850400.104      253028.627
     1850643.159      253115.433
#Sta/Elev= 30
       0 1327.21   11.661323.537    19.7 1321.49    29.5 1320.47    39.3 1320.26
    88.5 1320.37    98.4 1321.27  110.141323.286     118 1324.69   127.9 1325.74
   137.7 1325.94   147.5 1325.17  150.971324.431     177 1317.83   186.9  1316.1
   245.9 1312.59   265.6    1312   304.9 1312.36   314.7 1313.08  336.041317.093
   354.1  1320.8   363.9  1322.1   432.8 1323.36   461.4 1324.61   518.8 1330.52
   547.4 1334.48   576.1    1340   595.2 1344.84   623.9 1353.22   690.8 1374.31
#Mann= 7 ,-1 , 0
       0     .12       0   11.66     .06       0  110.14    .016       0
  150.97     .12       0   245.9    .045       0   304.9     .04       0
  336.04     .12       0
Bank Sta=245.9,304.9
XS Rating Curve= 0 ,0
Exp/Cntr=0.3,0.1

Type RM Length L Ch R = 1 ,17029.9 ,690.3,695,699
XS GIS Cut Line= 3
     1849835.868      253523.419      1850339.34      253349.808
     1850538.993       253375.85
#Sta/Elev= 30
       0 1330.86    38.7 1328.17   73.631324.823    87.2 1323.02   106.5 1319.41
  112.34 1318.85   116.2 1318.48   125.9 1318.46  152.541319.197   203.3 1323.13
     213 1323.49   242.1 1323.32   251.8 1321.32   271.1 1310.22  277.74 1308.27
   280.8  1307.6   290.5 1307.31   338.9 1307.86  349.091308.295     397 1310.46
   445.4 1313.36   513.2 1316.78   542.2 1318.47   561.3  1320.2   609.3 1327.77
   628.4    1332     638 1334.53   657.2 1340.53   695.6 1354.14   733.9 1365.87
#Mann= 7 ,-1 , 0
       0     .06       0   73.63     .12       0  112.34    .016       0
  152.54     .12       0  277.74    .045       0   338.9     .04       0
  349.09     .12       0
Bank Sta=277.74,338.9
XS Rating Curve= 0 ,0
Exp/Cntr=0.3,0.1

Type RM Length L Ch R = 1 ,16334.9 ,584.6,555.6,526.1
XS GIS Cut Line= 4
     1850070.243      254243.905     1850131.006      254087.655
     1850595.416      253992.169     1850712.604      253818.558
#Sta/Elev= 30
       0 1332.22    55.9 1316.02    65.2 1313.73    74.5 1312.37   98.131312.273
   100.21312.262  163.491310.988  206.641311.043  223.541311.269   254.7 1311.32
  271.541310.826   322.5 1308.13   361.2 1304.99   380.5 1302.81   390.2 1301.34
   399.9 1300.55   409.6 1300.63   448.2 1302.74  460.121303.321     487 1304.28
     5211304.744     545 1305.74   603.1 1309.48   689.4 1315.47   698.9  1316.5
   708.4 1318.21     737 1324.35   784.6 1333.59  836.591345.084   851.2 1348.69
#Mann= 12 ,-1 , 0
       0     .12       0   98.13     .06       0   100.2     .12       0
  163.49     .06       0  206.64     .12       0  223.54    .016       0
  271.54     .12       0   380.5    .045       0   448.2     .04       0
  460.12     .12       0     521     .06       0  836.59     .12       0
Bank Sta=380.5,448.2
XS Rating Curve= 0 ,0
Exp/Cntr=0.3,0.1

Type RM Length L Ch R = 1 ,15779.3 ,341.6,341.3,341.1
XS GIS Cut Line= 3
      1850495.59      254677.933     1850625.798      254556.405
      1851080.72      253885.894
#Sta/Elev= 30
       0 1381.46     9.4 1376.03    37.5 1358.42    46.9 1352.94    56.2 1348.66
    84.4 1338.69  155.221311.992   168.7  1308.7   187.9 1307.47  197.851305.249
   217.2 1298.97   226.9 1296.65   233.91295.693   238.3 1295.26   256.2    1295
   300.9 1295.41  310.721296.102  360.261300.882  461.041303.375  463.161303.478
   490.5 1304.49   578.4  1305.1  634.991307.266  683.091310.528   705.3 1312.46
     715 1314.06   733.31318.365  841.461345.116   900.5    1360   988.4 1386.54
#Mann= 14 ,-1 , 0
       0     .12       0  155.22    .016       0  197.85     .12       0
   233.9     .04       0   238.3    .045       0   300.9     .04       0
  310.72     .12       0  360.26     .06       0  461.04    .016       0
  463.16     .06       0  634.99     .12       0  683.09     .08       0
   733.3     .12       0  841.46     .06       0
Bank Sta=238.3,300.9
XS Rating Curve= 0 ,0
Exp/Cntr=0.3,0.1

Type RM Length L Ch R = 1 ,15438   ,622.2,618.6,614.8
XS GIS Cut Line= 3
       1850647.5      254925.329     1850899.236      254760.398
     1851429.679      253964.019
#Sta/Elev= 30
       0 1393.15    19.4 1385.64    29.1 1380.14    58.2 1356.68      68 1351.52
    77.7 1349.33   116.5 1345.78   126.2 1343.14  183.78 1318.14   194.2 1314.39
   203.9 1312.87  226.931311.496     301 1305.73  351.341295.604   352.6 1295.46
   369.3 1294.15   398.6 1293.82   415.4 1294.38  428.581295.811  468.091298.051
   535.3 1302.16   574.3 1303.32  770.88 1302.12     838 1302.55   857.5 1303.59
 1006.071342.158  1023.5  1348.4  1091.8 1378.14 1218.941411.299  1257.8 1422.33
#Mann= 11 ,-1 , 0
       0     .12       0  183.78    .016       0  226.93     .12       0
  351.34     .04       0   352.6    .045       0   415.4     .12       0
  428.58    .016       0  468.09     .06       0  770.88     .12       0
 1006.07     .06       0 1218.94     .12       0
Bank Sta=352.6,415.4
XS Rating Curve= 0 ,0
Exp/Cntr=0.3,0.1

Type RM Length L Ch R = 1 ,14819.4 ,935.5,977.4,1019.3
XS GIS Cut Line= 3
     1850773.368      255276.891     1851359.305      255203.107
     1851981.762      254036.935
#Sta/Elev= 30
       0 1377.31    10.21374.906  155.071335.429  184.781327.535  214.491316.409
  247.151311.698   280.8 1303.58   377.6  1299.9   522.8 1300.51   590.6 1302.46
  665.031300.381   688.5 1298.46   729.5 1292.22     757 1290.01     806 1291.65
  854.131293.984  854.731294.012  936.85 1296.09   991.91295.173  1050.8 1293.89
  1129.1 1297.21 1215.141296.334  1334.7 1295.58  1354.3 1296.76  1422.9 1320.45
  1481.6 1345.03    1511  1355.7  1677.5 1401.56 1872.231461.915  1912.5 1474.93
#Mann= 15 ,-1 , 0
       0     .12       0    10.2     .06       0  155.07     .12       0
  184.78     .06       0  214.49    .016       0  247.15     .06       0
  665.03     .12       0   729.5    .045       0     806    .016       0
  854.13     .12       0  854.73     .06       0  936.85     .12       0
   991.9     .06       0 1215.14     .12       0 1872.23     .06       0
Bank Sta=729.5,806
XS Rating Curve= 0 ,0
Exp/Cntr=0.3,0.1

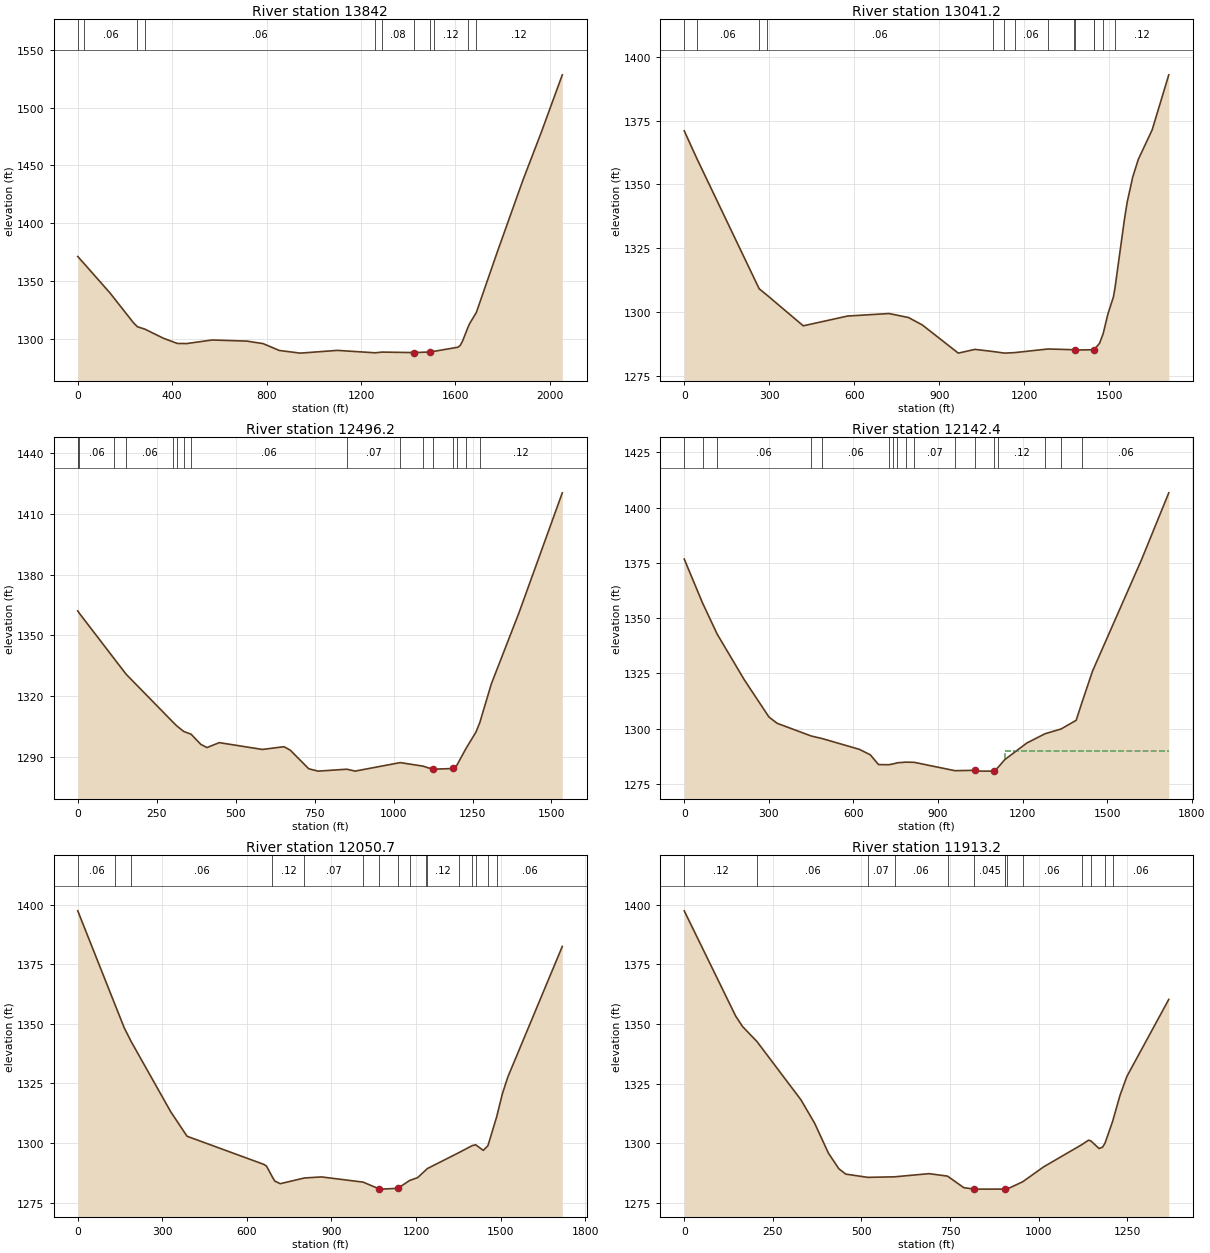
Type RM Length L Ch R = 1 ,13842   ,765.9,800.8,835.7
XS GIS Cut Line= 3
     1850779.328      255335.602     1851521.516      255591.679
     1852789.054      255609.852
#Sta/Elev= 30
       0 1371.19   26.441365.129   137.4 1339.42   235.5 1313.94  253.01 1310.36
  284.141308.324   363.1  1300.4     422 1295.91   461.3 1295.82   569.2 1298.91
   716.4 1297.94   785.1 1295.77   853.9 1289.84   942.4 1287.54  1099.6 1289.91
 1259.95 1287.83 1289.491288.441  1423.9 1288.01  1492.7 1288.53 1508.991289.075
  1610.6 1292.66  1620.4 1294.22  1630.2 1297.96 1653.281309.927  1659.7 1312.94
 1688.421322.629  1777.6 1375.23  1885.7 1437.11  1964.4 1479.02  2052.8 1528.43
#Mann= 11 ,-1 , 0
       0     .12       0   26.44     .06       0  253.01    .016       0
  284.14     .06       0 1259.95     .12       0 1289.49     .08       0
  1423.9    .045       0  1492.7     .04       0 1508.99     .12       0
 1653.28    .016       0 1688.42     .12       0
Bank Sta=1423.9,1492.7
XS Rating Curve= 0 ,0
Exp/Cntr=0.3,0.1

Type RM Length L Ch R = 1 ,13041.2 ,527.9,545,561.7
XS GIS Cut Line= 3
     1850769.027      255381.058     1851407.048      255598.072
     1852010.347      256440.086
#Sta/Elev= 30
       0 1371.01   44.661360.133  264.351309.138   293.51306.497     420 1294.61
   576.2 1298.44   722.8 1299.42   791.2 1297.86     840 1294.96   967.1 1283.91
  1025.7 1285.38 1090.251284.535 1130.121283.919 1165.721284.106 1283.311285.529
 1374.831285.242  1377.5 1285.13  1445.9 1285.24 1446.891285.358  1465.4 1287.74
 1478.46 1291.58  1494.8 1299.16  1514.3 1305.86 1519.661309.185  1553.4 1336.36
  1563.2 1343.12  1582.7 1352.94  1602.3 1359.83  1651.1 1371.36  1709.8 1392.95
#Mann= 14 ,-1 , 0
       0     .12       0   44.66     .06       0  264.35    .016       0
   293.5     .06       0 1090.25     .12       0 1130.12     .04       0
 1165.72     .06       0 1283.31     .12       0 1374.83     .04       0
  1377.5    .045       0  1445.9     .04       0 1446.89     .12       0
 1478.46    .016       0 1519.66     .12       0
Bank Sta=1377.5,1445.9
XS Rating Curve= 0 ,0
Exp/Cntr=0.3,0.1

Type RM Length L Ch R = 1 ,12496.2 ,340.9,353.8,366.7
XS GIS Cut Line= 4
      1850718.68      255523.094     1851228.663      255766.149
     1851352.361      256460.594     1851450.017      256705.819
#Sta/Elev= 30
       0 1362.14    1.861361.707    4.741361.036  115.171338.582  153.451330.837
  300.271307.445  313.53  1305.4  335.441302.648  358.711301.315   389.6 1296.29
   409.1  1294.7   448.1 1297.13   584.5 1293.77   653.1 1295.12   672.7 1293.44
   731.5 1284.23   760.9 1283.07   851.91284.014   878.4 1283.09 1021.111287.275
  1093.91285.515  1123.4    1284  1188.6 1284.37 1199.481285.717 1229.391294.267
  1260.5 1302.22 1272.891306.949  1309.4 1326.03  1397.4 1361.34  1534.3  1420.4
#Mann= 17 ,-1 , 0
       0     .06       0    1.86     .12       0    4.74     .06       0
  115.17     .12       0  153.45     .06       0  300.27     .12       0
  313.53     .06       0  335.44    .016       0  358.71     .06       0
   851.9     .07       0 1021.11     .06       0  1093.9     .12       0
  1123.4    .045       0  1188.6     .04       0 1199.48     .12       0
 1229.39    .016       0 1272.89     .12       0
Bank Sta=1123.4,1188.6
XS Rating Curve= 0 ,0
Exp/Cntr=0.3,0.1

Type RM Length L Ch R = 1 ,12142.4 ,91.7,91.7,91.7
XS GIS Cut Line= 4
     1850608.003      255640.281     1851057.222      255889.847
     1850953.055      256760.073     1851259.045       256879.43
#Sta/Elev= 30
       0 1376.71   65.141356.787  116.921342.725   213.3 1322.01   300.6  1305.2
   329.7 1302.35  450.741296.599  490.391295.416     621 1290.58     660  1288.1
   689.2 1283.68  725.861283.609  742.181284.008  755.921284.486  785.731284.775
  815.541284.703  960.461280.906  1032.6 1281.09  1049.5 1280.71    1098 1280.72
 1112.311282.275  1137.1 1285.92    1215 1293.41 1279.941297.642  1336.61299.779
  1390.3 1303.72 1412.211312.318  1448.3 1325.98  1622.2 1376.43  1718.8 1406.69
#Mann= 17 ,-1 , 0
       0     .06       0   65.14     .12       0  116.92     .06       0
  450.74    .016       0  490.39     .06       0  725.86     .07       0
  742.18     .12       0  755.92     .06       0  785.73     .12       0
  815.54     .07       0  960.46     .12       0  1032.6    .045       0
    1098     .04       0 1112.31     .12       0 1279.94    .016       0
  1336.6     .12       0 1412.21     .06       0
#XS Ineff= 2 , 0
                          1138.7          1289.7
Permanent Ineff=
       F       F
Bank Sta=1032.6,1098
XS Rating Curve= 0 ,0
Exp/Cntr=0.3,0.1

Type RM Length L Ch R = 1 ,12050.7 ,154.7,137.5,120.3
XS GIS Cut Line= 4
     1850527.708      255638.111     1850976.927      255887.677
      1850872.76      256757.903      1851178.75       256877.26
#Sta/Elev= 30
       0 1397.36   132.81357.827   164.8 1348.34  190.05 1342.43   329.7 1313.15
   387.8 1302.86     660 1291.08   669.7 1290.32  690.391285.781   698.9 1284.07
   718.4 1282.98  803.94 1285.37   864.5 1285.82 1012.331283.635    1070 1280.75
  1078.7  1280.7  1135.5 1281.05 1176.791284.302  1205.3 1285.51  1236.4 1288.89
 1240.511289.343 1352.551296.035 1399.33 1298.95 1411.531299.293  1438.6 1296.94
 1455.021298.914 1485.741310.927  1506.2 1320.66  1525.6 1327.72  1718.8 1382.44
#Mann= 16 ,-1 , 0
       0     .06       0   132.8     .12       0  190.05     .06       0
  690.39     .12       0  803.94     .07       0 1012.33     .12       0
    1070    .045       0  1135.5     .04       0 1176.79     .12       0
  1236.4     .06       0 1240.51     .12       0 1352.55     .06       0
 1399.33     .12       0 1411.53    .016       0 1455.02     .12       0
 1485.74     .06       0
Bank Sta=1070,1135.5
XS Rating Curve= 0 ,0
Exp/Cntr=0.3,0.1

Type RM Length L Ch R = 1 ,11913.2 ,600.1,569.7,539.4
XS GIS Cut Line= 4
     1850286.822       255939.76     1850655.746      256111.201
     1850857.569      256786.114     1851096.284       256877.26
#Sta/Elev= 30
       0 1397.49   145.3 1353.28   164.7 1348.91  205.48 1342.59   329.3 1318.17
   368.1 1308.29   406.8  1295.8   436.2 1289.25   455.7 1287.01  517.791285.647
  593.521285.878   690.6  1287.2  742.741286.166   788.4 1281.34   817.7 1280.71
   905.8 1280.72  906.231280.724  911.241280.776  954.481283.771  1013.4 1290.02
 1121.89 1299.41  1140.7 1301.27 1147.451300.895  1170.2 1297.74    1180 1298.32
 1186.85 1299.96 1208.21 1309.05  1229.2 1320.04  1248.8 1328.06  1366.8 1360.32
#Mann= 14 ,-1 , 0
       0     .12       0  205.48     .06       0  517.79     .07       0
  593.52     .06       0  742.74     .12       0   817.7    .045       0
   905.8     .04       0  906.23     .12       0  911.24     .04       0
  954.48     .06       0 1121.89     .12       0 1147.45    .016       0
 1186.85     .12       0 1208.21     .06       0
Bank Sta=817.7,905.8
XS Rating Curve= 0 ,0
Exp/Cntr=0.3,0.1

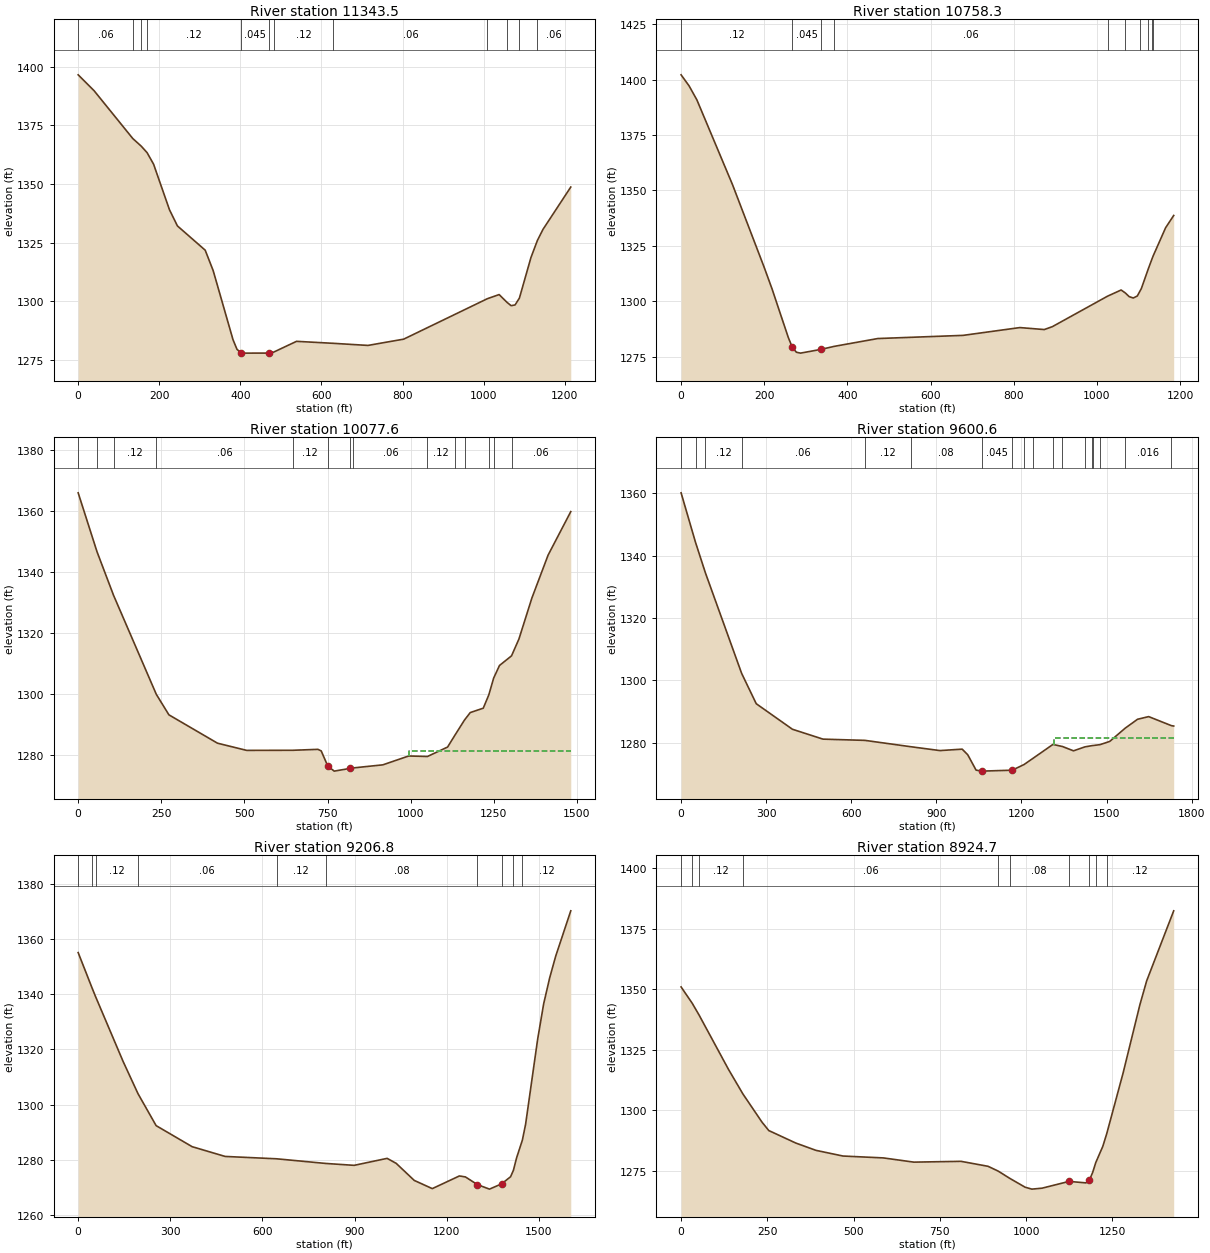
Type RM Length L Ch R = 1 ,11343.5 ,613.4,585.2,556.8
XS GIS Cut Line= 3
      1849930.92      256508.337      1850720.85      256920.663
     1851044.201      256940.194
#Sta/Elev= 30
       0 1396.46    39.2 1389.71  134.741369.339  155.521366.102  170.021363.325
     186 1358.43   225.2 1339.03   244.8 1332.15   313.3 1321.82   332.9 1313.18
   381.9 1283.72   391.7 1279.63   401.5 1278.13   411.3    1278     470 1278.02
  482.031278.416   538.6 1283.02  629.331282.171   714.8 1281.28   802.9 1283.95
 1009.421301.179  1038.3 1302.92 1057.461299.662  1067.8  1298.2  1077.6 1298.51
 1088.29 1301.43  1116.8  1318.7 1132.671325.948  1146.3 1330.63    1215 1348.69
#Mann= 12 ,-1 , 0
       0     .06       0  134.74     .12       0  155.52     .06       0
  170.02     .12       0   401.5    .045       0     470     .04       0
  482.03     .12       0  629.33     .06       0 1009.42     .12       0
 1057.46    .016       0 1088.29     .12       0 1132.67     .06       0
Bank Sta=401.5,470
XS Rating Curve= 0 ,0
Exp/Cntr=0.3,0.1

Type RM Length L Ch R = 1 ,10758.3 ,693.2,680.7,667.6
XS GIS Cut Line= 4
     1849818.941      257259.639     1850037.691      257257.035
     1850660.086      257087.764     1850980.399      257111.201
#Sta/Elev= 30
       0 1402.16      19 1397.24      38 1390.85   123.6 1352.63   199.7 1315.36
   218.8 1305.53   257.9 1283.59   267.6 1279.12   277.4 1276.95   287.2 1276.55
     336 1278.22  368.241279.599   472.9 1283.13   678.1 1284.56   814.9 1288.08
   873.5 1287.19     893 1288.49  1025.91302.266  1058.4 1305.04 1068.261303.749
  1077.9 1302.04  1087.6 1301.43  1097.4 1302.34 1103.351304.395  1107.1 1305.69
 1124.141314.768 1132.771319.105 1135.36 1320.37  1165.5 1333.16  1184.9 1338.68
#Mann= 10 ,-1 , 0
       0     .12       0   267.6    .045       0     336     .12       0
  368.24     .06       0  1025.9     .12       0 1068.26    .016       0
 1103.35     .12       0 1124.14     .06       0 1132.77     .12       0
 1135.36     .06       0
Bank Sta=267.6,336
XS Rating Curve= 0 ,0
Exp/Cntr=0.3,0.1

Type RM Length L Ch R = 1 ,10077.6 ,422,477,522.3
XS GIS Cut Line= 3
     1849856.267      257463.632     1850442.204      257793.493
     1851110.607      257337.764
#Sta/Elev= 30
       0 1366.01   56.711346.659  106.371332.378  234.991299.862   272.9 1293.13
     419 1283.82   506.7 1281.46  645.241281.491   721.1  1281.8   730.9 1281.29
   750.4 1276.37   769.9 1274.65   818.6 1275.56  827.671275.708   916.1 1276.71
     994 1279.62 1050.431279.455    1111 1282.56 1133.22 1286.49 1161.811291.427
  1179.2 1293.88  1218.2 1295.31  1234.81299.644 1249.561305.208    1267 1309.33
 1303.221312.493  1325.4 1317.99  1364.4 1331.46  1413.2 1345.56  1481.4 1359.84
#Mann= 14 ,-1 , 0
       0     .12       0   56.71     .06       0  106.37     .12       0
  234.99     .06       0  645.24     .12       0   750.4    .045       0
   818.6     .04       0  827.67     .06       0 1050.43     .12       0
 1133.22     .06       0 1161.81    .016       0  1234.8     .06       0
 1249.56     .12       0 1303.22     .06       0
#XS Ineff= 2 , 0
                          995.67         1281.28
Permanent Ineff=
       F       F
Bank Sta=750.4,818.6
XS Rating Curve= 0 ,0
Exp/Cntr=0.3,0.1

Type RM Length L Ch R = 1 ,9600.6  ,367.3,393.8,429.6
XS GIS Cut Line= 2
     1849859.524      257487.269     1851374.965      258335.515
#Sta/Elev= 30
       0 1360.18    50.81344.311   85.431334.588  213.461302.267   264.9 1292.54
   392.5 1284.34   500.4 1281.17  648.051280.774  808.95 1278.75   912.5  1277.5
     991 1277.96  1010.6 1276.16    1040 1271.23  1059.7 1270.91  1167.6 1271.21
  1209.5 1273.05 1239.04 1274.91 1310.851279.471  1344.51278.805  1383.5 1277.42
 1423.56 1278.69 1448.681279.084 1451.641279.114 1477.071279.405    1511 1280.43
 1565.741284.691  1609.1 1287.54  1648.4  1288.4 1728.411285.505  1736.7 1285.37
#Mann= 18 ,-1 , 0
       0     .12       0    50.8     .06       0   85.43     .12       0
  213.46     .06       0  648.05     .12       0  808.95     .08       0
  1059.7    .045       0  1167.6     .08       0  1209.5     .12       0
 1239.04     .06       0 1310.85    .016       0  1344.5     .06       0
 1423.56     .12       0 1448.68     .06       0 1451.64     .12       0
 1477.07     .06       0 1565.74    .016       0 1728.41     .06       0
#XS Ineff= 2 , 0
                         1315.17         1281.69
Permanent Ineff=
       F       F
Bank Sta=1059.7,1167.6
XS Rating Curve= 0 ,0
Exp/Cntr=0.3,0.1

Type RM Length L Ch R = 1 ,9206.8  ,284.8,282.1,278.6
XS GIS Cut Line= 3
     1849863.706      257506.988      1850701.38      257969.227
      1850707.89      258615.929
#Sta/Elev= 30
       0 1355.16   44.211342.613    56.51339.224   146.4 1315.63  194.771303.968
   253.8 1292.37     371 1284.74   478.4  1281.2  645.881280.344  805.621278.659
   898.2 1277.97  1005.7  1280.5  1035.1  1278.7  1093.9 1272.51  1152.7 1269.52
  1240.9 1274.12  1260.5 1273.77  1299.7 1270.97  1338.9 1269.34  1378.1 1271.24
  1407.5 1273.83 1416.721276.154  1427.1 1280.68 1445.981287.136  1456.5  1292.9
  1495.7 1323.75  1515.3  1336.6  1534.9 1346.03  1554.5  1353.9  1603.5 1370.31
#Mann= 10 ,-1 , 0
       0     .12       0   44.21     .06       0    56.5     .12       0
  194.77     .06       0  645.88     .12       0  805.62     .08       0
  1299.7    .045       0  1378.1     .04       0 1416.72    .016       0
 1445.98     .12       0
Bank Sta=1299.7,1378.1
XS Rating Curve= 0 ,0
Exp/Cntr=0.3,0.1

Type RM Length L Ch R = 1 ,8924.7  ,501,506.6,512.4
XS GIS Cut Line= 3
     1849856.267      257533.076      1850372.76      257810.854
     1850450.885      258648.528
#Sta/Elev= 30
       0 1350.95   32.191344.224   51.891339.415   136.8 1317.07  179.041306.808
   234.6 1295.13   254.1 1291.68   332.3 1286.53     391  1283.5   469.2 1281.16
   586.4 1280.38   674.5 1278.64   811.4 1278.97   889.7 1276.92  919.39 1274.92
  952.031271.995   997.3 1268.28  1016.9  1267.5  1046.2 1267.89  1124.5 1270.69
  1173.4 1270.08  1183.2 1271.16    1193 1274.41 1201.821278.424  1222.3 1285.15
 1233.791290.428    1281 1315.35  1329.9 1343.65  1349.5 1353.48  1427.8 1382.36
#Mann= 10 ,-1 , 0
       0     .12       0   32.19     .06       0   51.89     .12       0
  179.04     .06       0  919.39     .12       0  952.03     .08       0
  1124.5    .045       0  1183.2     .04       0 1201.82    .016       0
 1233.79     .12       0
Bank Sta=1124.5,1183.2
XS Rating Curve= 0 ,0
Exp/Cntr=0.3,0.1

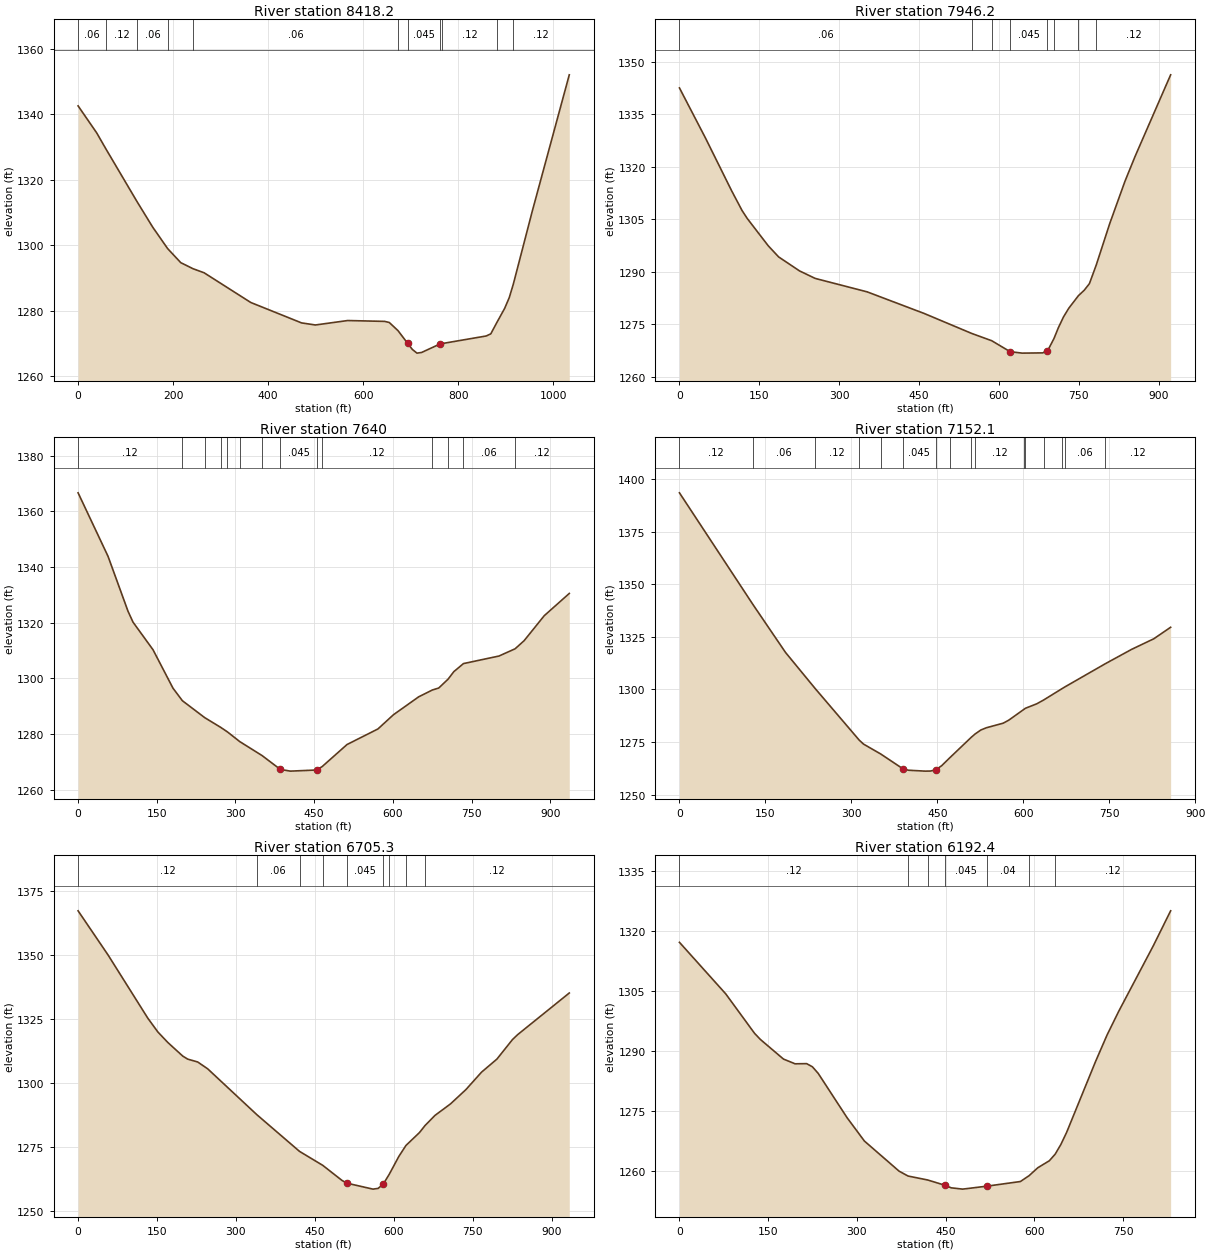
Type RM Length L Ch R = 1 ,8418.2  ,460.9,472,482.9
XS GIS Cut Line= 3
     1849825.885        257589.5     1850003.836       257906.34
     1849951.753      258574.743
#Sta/Elev= 30
       0 1342.55    39.3 1334.26   58.561329.387  124.261313.235   157.1 1305.47
  188.471298.929   216.1 1294.63  242.111292.765   265.2 1291.54   363.4 1282.46
   470.3 1276.22   499.4 1275.58   567.4 1276.94   645.2 1276.68   654.9 1276.35
   673.31273.857   693.8 1269.93   703.5 1268.11   713.2 1266.98   722.9 1267.18
   761.8 1269.78  766.791269.919   858.9 1272.22   868.6 1272.87  881.511276.381
   897.8 1280.66   907.5 1283.96  915.961288.033   956.1 1310.47  1033.8 1352.04
#Mann= 11 ,-1 , 0
       0     .06       0   58.56     .12       0  124.26     .06       0
  188.47     .12       0  242.11     .06       0   673.3     .12       0
   693.8    .045       0   761.8     .04       0  766.79     .12       0
  881.51    .016       0  915.96     .12       0
Bank Sta=693.8,761.8
XS Rating Curve= 0 ,0
Exp/Cntr=0.3,0.1

Type RM Length L Ch R = 1 ,7946.2  ,300.8,306.2,311.4
XS GIS Cut Line= 4
     1849634.913      257650.264     1849639.253      257954.083
     1849469.982      258388.111     1849483.003      258540.021
#Sta/Elev= 30
       0 1342.58      49  1328.2      98 1313.14   117.6 1307.49   127.4  1305.2
   166.6 1297.43   186.2 1294.23   225.4 1290.23   254.8 1288.08   352.4 1284.23
   459.1 1278.07     5491272.315  586.28 1270.25   620.9 1267.11   643.6  1266.7
   682.4 1266.77   689.6 1267.42   692.1 1267.64  703.061270.842   711.5    1274
   721.2  1277.1   730.9 1279.53  749.051283.136     760  1284.7   769.7 1286.59
  782.461291.878   807.8 1303.75   836.4 1315.85   855.5 1323.01   922.2 1346.33
#Mann= 8 ,-1 , 0
       0     .06       0     549    .016       0  586.28     .12       0
   620.9    .045       0   689.6     .04       0  703.06     .12       0
  749.05    .016       0  782.46     .12       0
Bank Sta=620.9,689.6
XS Rating Curve= 0 ,0
Exp/Cntr=0.3,0.1

Type RM Length L Ch R = 1 ,7640    ,522.5,487.9,453.2
XS GIS Cut Line= 4
     1849300.711      257698.007     1849365.816      257936.722
     1849187.864      258253.562     1849135.781      258574.743
#Sta/Elev= 30
       0  1366.7    57.1 1343.87    95.2 1324.13   104.7 1320.23   142.8 1310.32
   180.8 1296.53  198.711292.017  241.341285.927  271.871282.425  284.731280.791
  308.171277.315  350.741272.287   385.5 1267.33   404.6 1266.71   454.5 1267.11
   465.21268.345   512.6 1276.27   571.5 1281.86     601 1286.96   649.1  1293.4
  675.341295.866   687.4 1296.57  705.341299.779   716.1 1302.44  734.471305.345
   802.2 1308.06  832.931310.661   850.1 1313.57   888.4 1322.54   936.2 1330.55
#Mann= 14 ,-1 , 0
       0     .12       0  198.71     .06       0  241.34     .12       0
  271.87     .06       0  284.73     .12       0  308.17    .016       0
  350.74     .12       0   385.5    .045       0   454.5     .04       0
   465.2     .12       0  675.34    .016       0  705.34     .12       0
  734.47     .06       0  832.93     .12       0
Bank Sta=385.5,454.5
XS Rating Curve= 0 ,0
Exp/Cntr=0.3,0.1

Type RM Length L Ch R = 1 ,7152.1  ,445.9,446.8,447.7
XS GIS Cut Line= 2
     1848671.371      257797.833     1849014.253      258583.423
#Sta/Elev= 30
       0 1393.42   128.41340.273   185.1 1317.55  236.96 1300.36   313.81275.848
   321.4 1273.96  351.191269.292   389.3 1262.38   399.4 1261.57   428.6 1261.14
   438.3 1261.18   448.1 1261.86   457.8 1263.77  471.411267.395   509.21277.205
  516.011278.805     526 1280.69   535.7 1281.76     565 1283.93   574.7 1285.36
  600.96 1290.47  603.751291.011   623.4 1293.12  635.751294.971  667.751300.358
  672.061301.073  743.481312.235     789    1319   827.9 1324.06   857.2 1329.52
#Mann= 16 ,-1 , 0
       0     .12       0   128.4     .06       0  236.96     .12       0
   313.8    .016       0  351.19     .12       0   389.3    .045       0
   448.1     .04       0  471.41     .12       0   509.2     .06       0
  516.01     .12       0  600.96     .06       0  603.75    .016       0
  635.75     .06       0  667.75     .12       0  672.06     .06       0
  743.48     .12       0
Bank Sta=389.3,448.1
XS Rating Curve= 0 ,0
Exp/Cntr=0.3,0.1

Type RM Length L Ch R = 1 ,6705.3  ,513.6,512.9,512.1
XS GIS Cut Line= 3
     1848389.253      257858.597     1848328.489      258097.312
     1848584.566      258735.333
#Sta/Elev= 30
       0 1367.11    56.8 1349.91   132.6 1325.14   151.6 1319.78   170.5 1315.68
     199 1310.34   208.4 1309.16   227.4 1308.04   246.3 1305.38  339.771287.458
  421.071273.094   465.2 1267.64   501.7 1261.76   511.5 1260.66   560.6 1258.36
   570.4 1258.64   580.2 1260.35  591.681264.214   609.7 1271.11   623.31275.426
     649 1280.46  659.491283.185   678.5 1287.17   707.9 1291.65   737.4 1297.28
   766.9 1304.05   796.3 1309.19   825.8  1316.8   835.6 1318.72   933.8    1335
#Mann= 9 ,-1 , 0
       0     .12       0  339.77     .06       0  421.07    .016       0
   465.2     .06       0   511.5    .045       0   580.2     .04       0
  591.68     .12       0   623.3    .016       0  659.49     .12       0
Bank Sta=511.5,580.2
XS Rating Curve= 0 ,0
Exp/Cntr=0.3,0.1

Type RM Length L Ch R = 1 ,6192.4  ,401.4,391.8,382.3
XS GIS Cut Line= 3
     1847894.461       258053.91     1847885.781       258366.41
     1848085.434       258843.84
#Sta/Elev= 30
       0  1317.1    78.2 1304.22     127 1294.34   136.8 1292.82   175.8 1287.92
   195.4 1286.74   214.9 1286.78   224.7 1285.99   234.5 1284.34   283.3 1273.27
   312.6 1267.43   371.2 1259.91  386.351258.691  419.471257.704   449.5 1256.35
   459.1 1255.75   478.6 1255.42   519.6 1256.16   576.2 1257.32  590.881258.782
   605.5 1260.75   625.1 1262.51   634.91264.145   644.6 1266.58   654.4 1269.63
   703.2 1287.31   722.7 1293.95   742.2 1299.81   800.8 1316.23   830.1 1324.97
#Mann= 7 ,-1 , 0
       0     .12       0  386.35    .016       0  419.47     .12       0
   449.5    .045       0   519.6     .04       0  590.88    .016       0
   634.9     .12       0
Bank Sta=449.5,519.6
XS Rating Curve= 0 ,0
Exp/Cntr=0.3,0.1

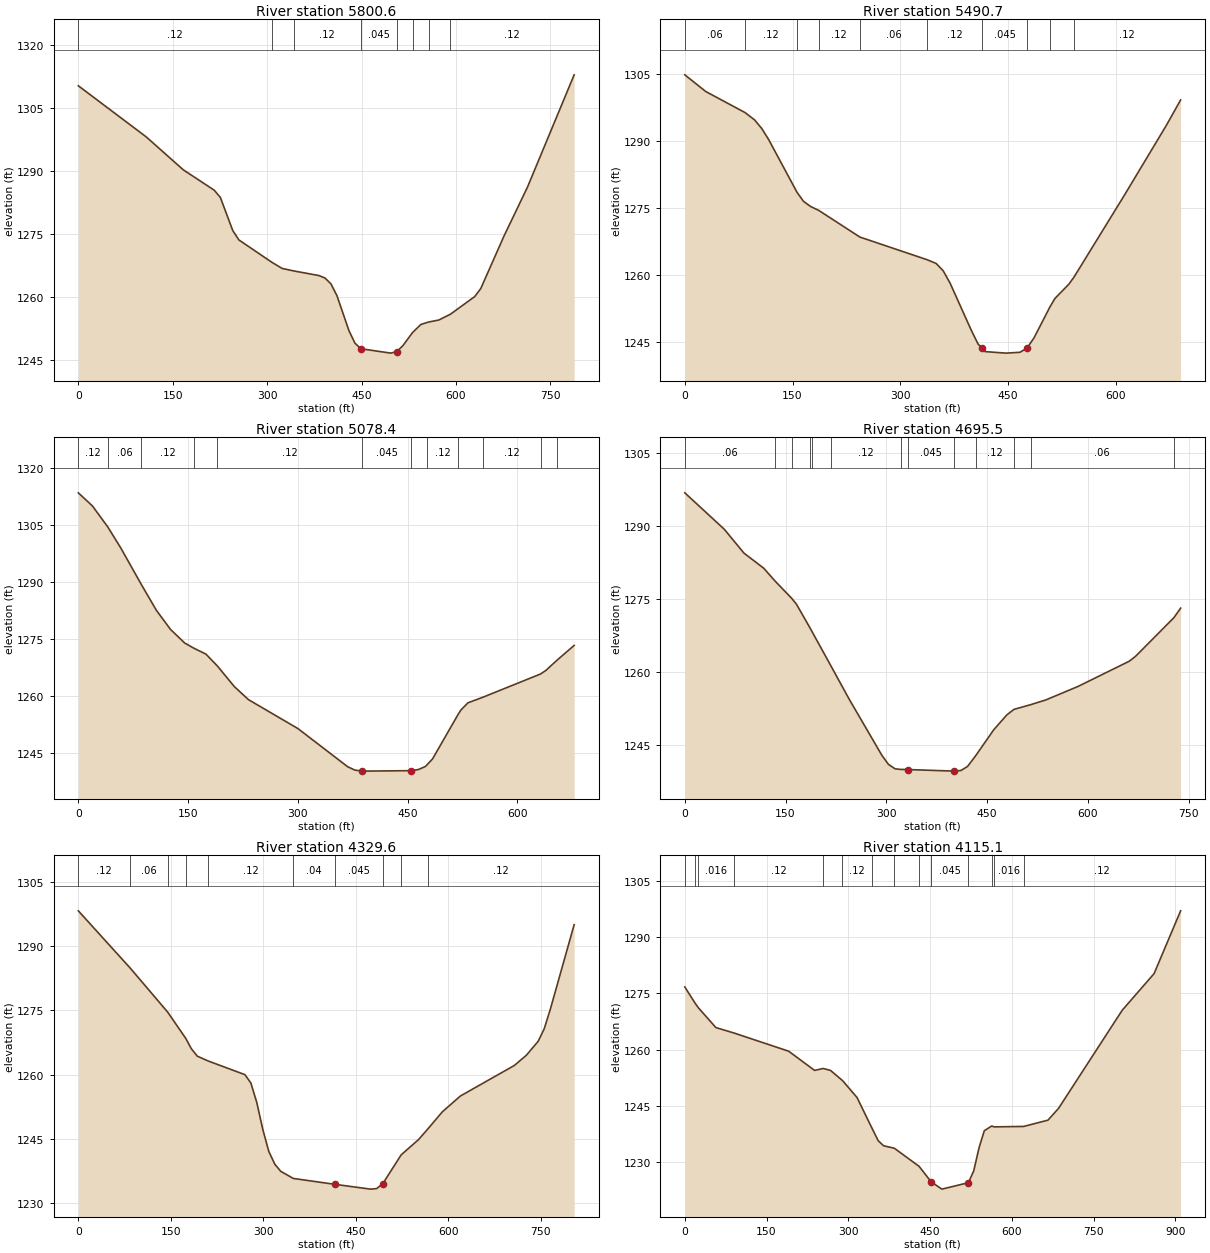
Type RM Length L Ch R = 1 ,5800.6  ,297.4,309.9,322
XS GIS Cut Line= 4
     1847473.454      258244.882     1847551.579      258609.465
      1847712.17      258822.139     1847751.232      258965.368
#Sta/Elev= 30
       0 1310.39   107.9  1298.2   166.8 1290.35   215.9  1285.5   225.7 1283.76
   245.3  1275.9   255.1 1273.64  307.821268.276   323.8 1266.84  341.961266.255
   382.4 1265.14   391.9 1264.56   401.4 1263.16   410.9 1260.36     430    1252
   439.5 1249.03     449 1247.69   496.6 1246.65   506.1 1247.03   515.6 1248.42
   531.21251.586   544.2 1253.48   556.41254.058   572.7 1254.54  591.25 1255.93
   629.8 1260.13   639.4 1262.04   676.5 1274.62   713.6 1286.21   787.8    1313
#Mann= 8 ,-1 , 0
       0     .12       0  307.82    .016       0  341.96     .12       0
     449    .045       0   506.1     .04       0   531.2     .12       0
   556.4    .016       0  591.25     .12       0
Bank Sta=449,506.1
XS Rating Curve= 0 ,0
Exp/Cntr=0.3,0.1

Type RM Length L Ch R = 1 ,5490.7  ,404.6,412.4,419.8
XS GIS Cut Line= 2
     1847191.336      258396.791      1847408.35      259052.173
#Sta/Elev= 30
       0 1304.76    29.2 1301.02   83.72 1296.32    97.2 1294.66     107 1292.76
   116.7 1290.28  156.341278.424   165.3 1276.42     175 1275.28  186.641274.375
  243.781268.415  337.441263.336     350  1262.5   359.8 1260.86   369.5 1258.06
   398.7 1247.61   408.4 1244.44   413.7 1243.52   418.1 1242.75   447.3 1242.41
   466.7  1242.6   476.5 1243.54   486.2 1245.81  508.231252.699   515.4 1254.66
   534.8 1257.86  542.041259.465   612.6 1277.92   670.9 1293.54   690.4 1299.13
#Mann= 10 ,-1 , 0
       0     .06       0   83.72     .12       0  156.34    .016       0
  186.64     .12       0  243.78     .06       0  337.44     .12       0
   413.7    .045       0   476.5     .04       0  508.23    .016       0
  542.04     .12       0
Bank Sta=413.7,476.5
XS Rating Curve= 0 ,0
Exp/Cntr=0.3,0.1

Type RM Length L Ch R = 1 ,5078.4  ,376,382.9,390
XS GIS Cut Line= 3
     1846943.941      258461.896     1846909.218      258730.993
     1846956.961      259134.639
#Sta/Elev= 30
       0 1313.37    19.4 1309.89    40.11304.436    58.1 1298.83   85.861289.334
   106.6 1282.47     126 1277.41   145.4 1273.83  157.621272.496   174.4 1270.91
  189.77 1267.85   213.2 1262.37   232.6 1258.92   300.4 1251.28   368.1 1241.27
   377.8 1240.39   387.5  1240.1   455.2 1240.22   464.9 1240.52   474.6 1241.34
     4771241.833   484.2 1243.31  519.461255.124     523 1256.19   532.6 1258.08
  553.281259.572  631.841265.672   639.1  1266.6   654.41269.309   677.8  1273.2
#Mann= 12 ,-1 , 0
       0     .12       0    40.1     .06       0   85.86     .12       0
  157.62    .016       0  189.77     .12       0   387.5    .045       0
   455.2     .04       0     477     .12       0  519.46    .016       0
  553.28     .12       0  631.84     .06       0   654.4     .12       0
Bank Sta=387.5,455.2
XS Rating Curve= 0 ,0
Exp/Cntr=0.3,0.1

Type RM Length L Ch R = 1 ,4695.5  ,385.6,365.9,346
XS GIS Cut Line= 3
     1846566.336         258527.     1846531.614      259034.812
     1846605.399      259251.826
#Sta/Elev= 30
       0 1296.73    58.7 1289.27    88.1 1284.36   117.5 1281.27  134.451278.622
  159.05 1275.11   166.4 1273.85   185.91269.145   188.71268.448  216.931261.389
   244.7 1254.41   293.6 1242.84   303.4    1241   313.2 1240.11  321.63 1239.99
   332.8 1239.96   401.3 1239.64   411.1 1239.77   420.9 1240.59  433.271242.838
   460.1 1248.15   479.6 1251.19  490.131252.309  515.031253.277   537.6 1254.25
   585.4 1257.01   661.8 1262.19   671.4 1263.23  728.181271.117   738.2 1273.07
#Mann= 13 ,-1 , 0
       0     .06       0  134.45    .016       0  159.05     .06       0
   185.9     .12       0   188.7     .06       0  216.93     .12       0
  321.63     .04       0   332.8    .045       0   401.3     .04       0
  433.27     .12       0  490.13    .016       0  515.03     .06       0
  728.18     .12       0
Bank Sta=332.8,401.3
XS Rating Curve= 0 ,0
Exp/Cntr=0.3,0.1

Type RM Length L Ch R = 1 ,4329.6  ,221,214.5,207.6
XS GIS Cut Line= 3
     1846137.202      258577.428     1846133.156      258837.773
     1846369.219      259327.437
#Sta/Elev= 30
       0 1298.31   84.211284.898  144.791274.626  174.341268.431   183.2 1266.05
   192.9  1264.3  210.36 1263.18   270.1 1259.97   279.8 1258.01   289.5 1253.39
   299.2 1247.11   308.9 1241.99   318.6 1239.02   328.3 1237.34  348.751235.674
   415.7 1234.31   473.9 1233.18   483.6  1233.3   493.4 1234.39  523.521241.206
   551.6 1244.76   567.21247.344   590.4 1251.29   619.5 1254.97   706.9 1262.11
   726.3 1264.48   745.7 1267.78   755.4 1270.69   765.1 1275.15     804 1295.07
#Mann= 10 ,-1 , 0
       0     .12       0   84.21     .06       0  144.79     .12       0
  174.34    .016       0  210.36     .12       0  348.75     .04       0
   415.7    .045       0   493.4     .12       0  523.52    .016       0
   567.2     .12       0
Bank Sta=415.7,493.4
XS Rating Curve= 0 ,0
Exp/Cntr=0.3,0.1

Type RM Length L Ch R = 1 ,4115.1  ,94.1,94.6,95.1
XS GIS Cut Line= 4
     1845942.091      258645.442     1845867.415      258871.496
     1846085.943      259181.752     1846187.113      259455.586
#Sta/Elev= 30
       0 1276.69   19.221272.305   24.811271.164    57.1 1265.88   89.921264.456
   190.5  1259.6   238.1 1254.49  253.741255.003   267.3 1254.49  289.271251.798
   315.9 1247.29  343.011239.224   354.8 1235.79   364.6 1234.45  384.361233.788
  429.781228.966   452.1 1224.82   471.6 1222.91   520.2 1224.62     530 1227.77
   539.7 1233.89   549.4 1238.45  562.931239.695   567.51239.469  621.581239.586
   666.2 1241.26   685.7 1244.42   802.4  1270.5   860.8 1280.23   909.5 1296.94
#Mann= 14 ,-1 , 0
       0     .12       0   19.22     .06       0   24.81    .016       0
   89.92     .12       0  253.74     .06       0  289.27     .12       0
  343.01    .016       0  384.36     .12       0  429.78     .06       0
   452.1    .045       0   520.2     .04       0  562.93     .12       0
   567.5    .016       0  621.58     .12       0
Bank Sta=452.1,520.2
XS Rating Curve= 0 ,0
Exp/Cntr=0.3,0.1