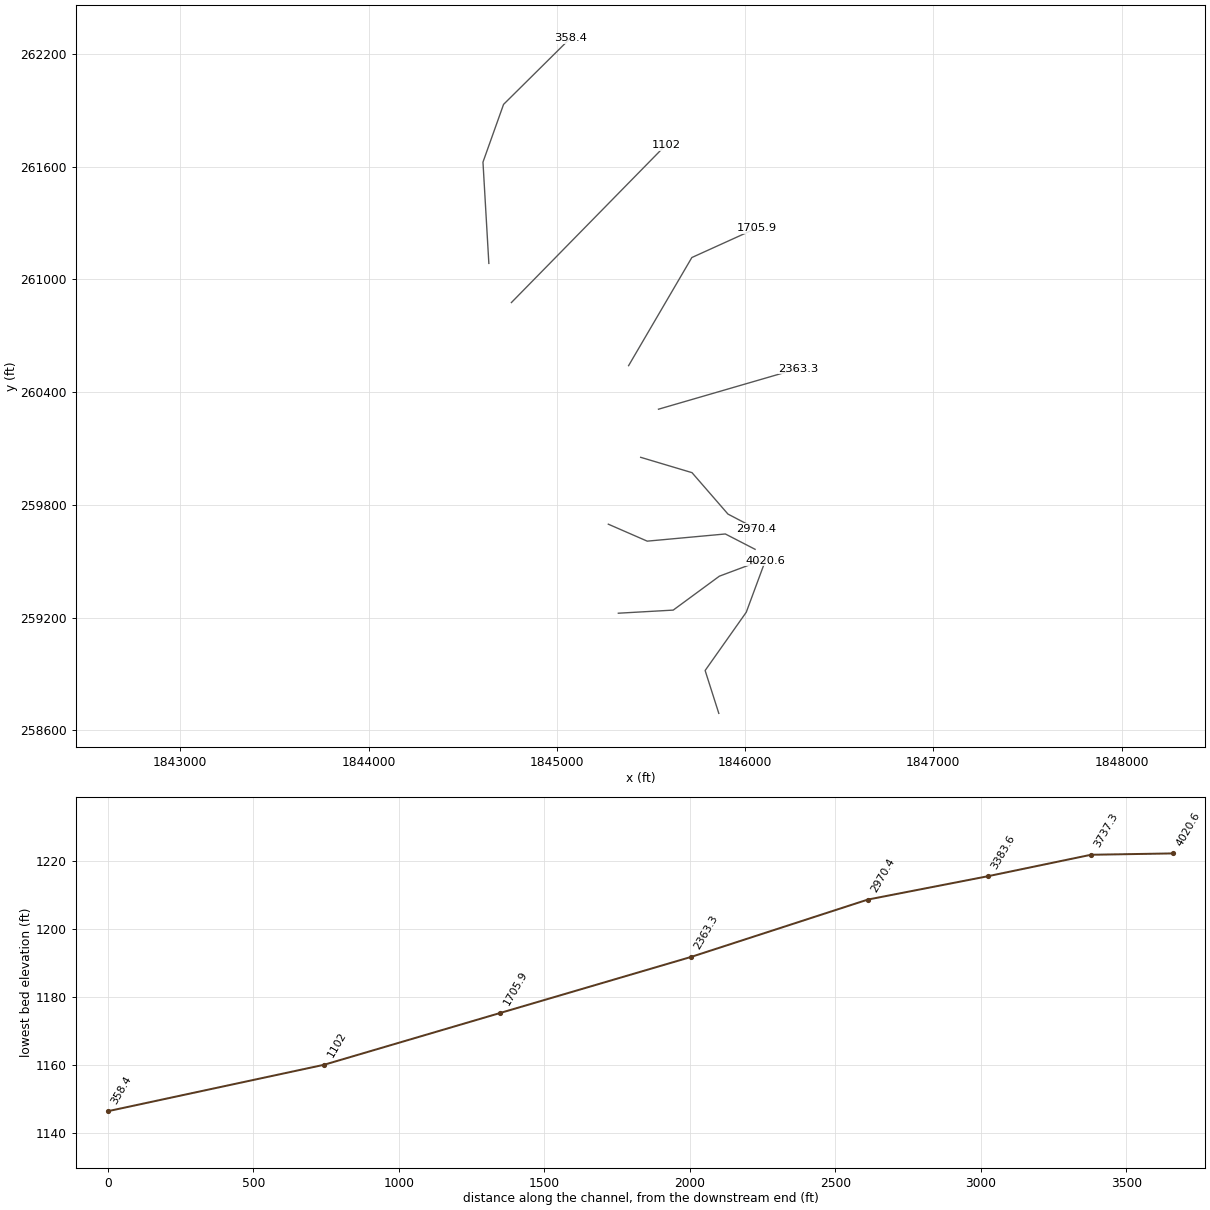
HEC-RAS study TETERCK.prj: TETERCK

--- TETERCK.g01 (geometry) --- (continued)

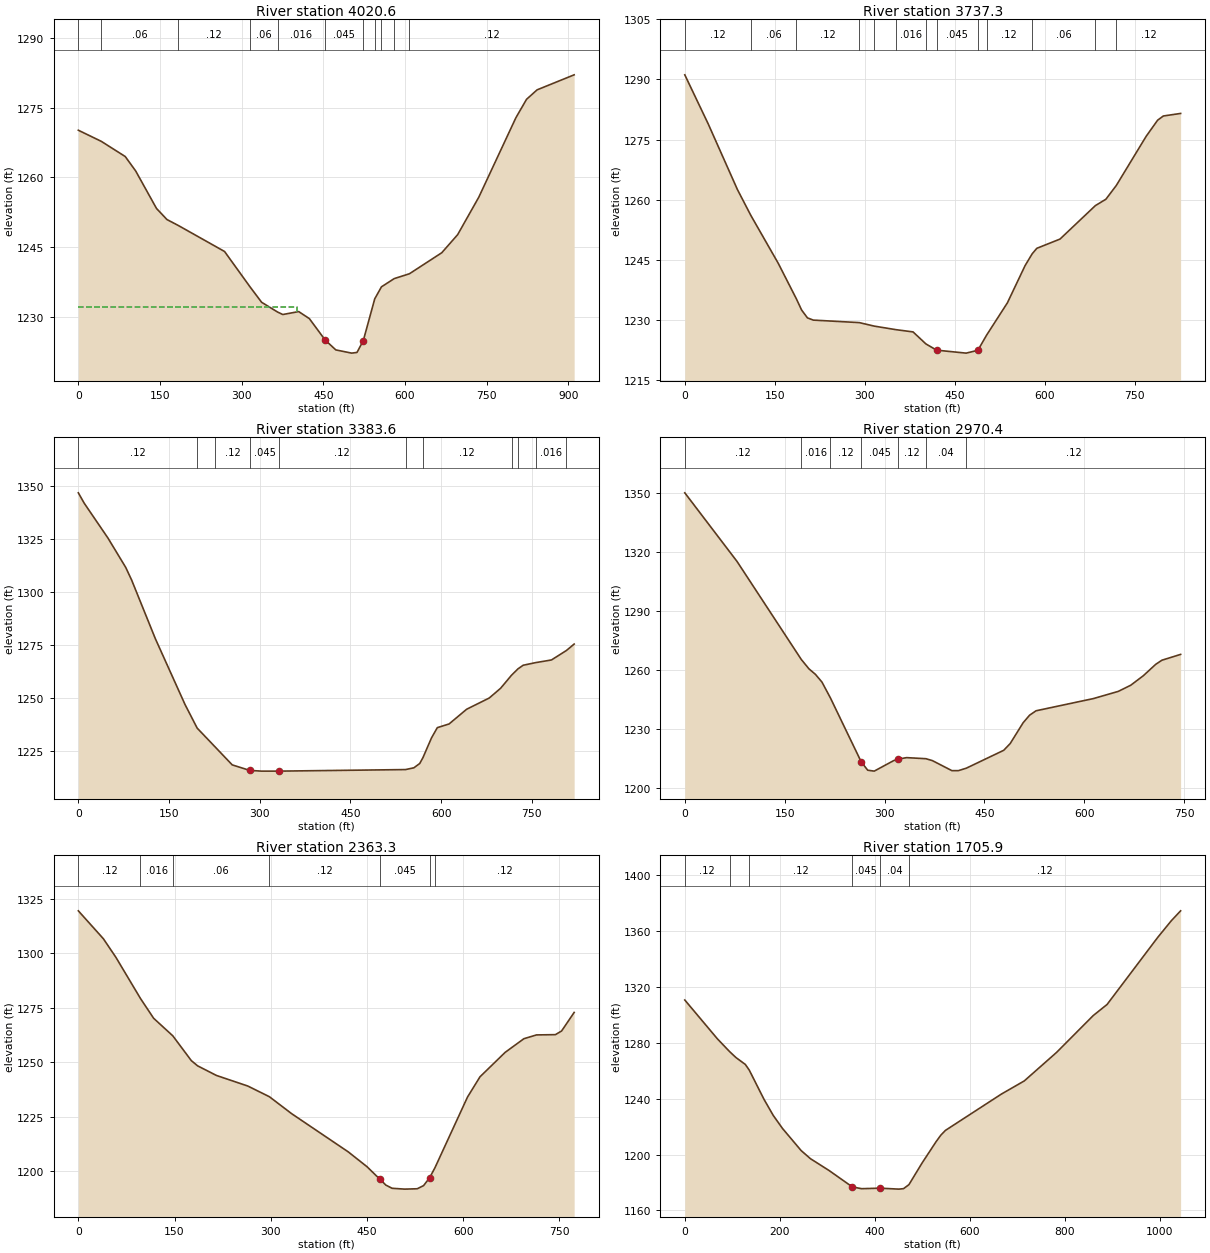
Type RM Length L Ch R = 1 ,4020.6  ,295.4,283.3,271.2
XS GIS Cut Line= 4
     1845860.493       258690.58     1845787.828      258918.709
     1846006.356      259228.964     1846107.526      259502.798
#Sta/Elev= 30
       0 1270.13   42.231267.737    86.2 1264.47   105.4 1261.36   143.6 1253.31
   162.8 1250.93  183.291249.673   268.6 1244.06  315.511236.442   336.7 1233.14
  365.941231.048   375.6 1230.51   404.8 1231.14   424.3 1229.64   453.5 1225.02
     473  1222.9   502.2 1222.21   511.9 1222.36  523.46  1224.9  544.511233.887
  556.81 1236.46  580.221238.229  608.251239.276   667.6 1243.79   696.8 1247.68
   735.7 1255.75   803.8 1272.82   823.3 1276.77   842.7 1278.81   910.8 1282.04
#Mann= 11 ,-1 , 0
       0     .12       0   42.23     .06       0  183.29     .12       0
  315.51     .06       0  365.94    .016       0   453.5    .045       0
  523.46     .04       0  544.51     .06       0  556.81     .08       0
  580.22    .016       0  608.25     .12       0
#XS Ineff= 2 , 0
          401.44 1232.06
Permanent Ineff=
       F       F
Bank Sta=453.5,523.46
XS Rating Curve= 0 ,0
Exp/Cntr=0.3,0.1

Type RM Length L Ch R = 1 ,3737.3  ,374.3,353.7,333.1
XS GIS Cut Line= 4
     1845326.833      259223.703     1845618.301      259240.218
     1845863.494      259420.799     1846078.569      259501.481
#Sta/Elev= 30
       0 1291.16    38.9 1278.97    87.6  1262.6  110.091256.117   155.7  1244.2
   186.11235.285   194.6 1232.56   204.4 1230.59   214.1 1230.04  290.791229.414
  315.731228.541  352.351227.644   380.3  1227.1  401.911224.089   419.6 1222.55
   468.8 1221.81   488.4 1222.52  502.851226.281   537.5 1234.33     567 1243.61
  578.77 1246.54   586.6 1247.93   625.2 1250.23  684.141258.566   701.7 1260.16
  718.961263.573   768.7 1275.82   787.9 1279.86   797.4  1280.9   826.2 1281.54
#Mann= 13 ,-1 , 0
       0     .12       0  110.09     .06       0   186.1     .12       0
  290.79     .06       0  315.73     .12       0  352.35    .016       0
  401.91     .12       0   419.6    .045       0   488.4     .04       0
  502.85     .12       0  578.77     .06       0  684.14    .016       0
  718.96     .12       0
Bank Sta=419.6,488.4
XS Rating Curve= 0 ,0
Exp/Cntr=0.3,0.1

Type RM Length L Ch R = 1 ,3383.6  ,426.8,413.2,377.6
XS GIS Cut Line= 4
     1845273.688      259697.525     1845480.285      259607.247
     1845895.216      259645.442     1846053.202      259563.844
#Sta/Elev= 30
       0 1347.01     9.8 1342.07      49 1325.64    78.4 1311.76    88.2 1305.77
   127.4 1278.07   176.4 1247.02  196.541235.836  226.681226.811   254.5 1218.46
   283.6 1215.84     303 1215.51     332 1215.51  541.12 1216.24   554.9 1217.08
   564.6 1219.11  569.861221.849     584 1231.16   593.7 1236.06   613.1 1237.79
   642.2 1244.75   679.6 1250.06   698.3 1254.64  716.48 1260.84  727.131263.844
   735.7 1265.54  756.241266.775   782.5 1268.04  807.241272.517     820 1275.55
#Mann= 11 ,-1 , 0
       0     .12       0  196.54    .016       0  226.68     .12       0
   283.6    .045       0     332     .12       0  541.12     .04       0
  569.86     .12       0  716.48     .06       0  727.13     .12       0
  756.24    .016       0  807.24     .12       0
Bank Sta=283.6,332
XS Rating Curve= 0 ,0
Exp/Cntr=0.3,0.1

Type RM Length L Ch R = 1 ,2970.4  ,586,607.1,649.8
XS GIS Cut Line= 4
     1845445.563      260053.428     1845718.132       259971.83
     1845909.105      259751.344      1846058.41      259673.219
#Sta/Elev= 30
       0 1350.34    78.5 1315.38  174.96 1265.49   186.4 1260.74   196.2 1257.91
     206 1253.98  218.791245.853   264.9  1213.4   274.7  1209.1   284.5 1208.63
   313.7 1213.98   320.3 1214.72   333.1  1215.5  362.221214.953     372 1213.96
   401.2 1208.87   410.9 1208.87  422.841210.132     479 1219.23   488.7 1222.66
   508.2 1233.28   517.9 1237.12   527.6 1239.36   613.7 1245.57   651.1 1249.24
   669.8 1252.37   688.6 1257.19   707.3 1263.01   716.6 1265.11   744.7 1268.07
#Mann= 7 ,-1 , 0
       0     .12       0  174.96    .016       0  218.79     .12       0
   264.9    .045       0   320.3     .12       0  362.22     .04       0
  422.84     .12       0
Bank Sta=264.9,320.3
XS Rating Curve= 0 ,0
Exp/Cntr=0.3,0.1

Type RM Length L Ch R = 1 ,2363.3  ,628.7,657.4,686.1
XS GIS Cut Line= 2
     1845540.181      260309.504     1846282.368       260525.65
#Sta/Elev= 30
       0 1319.49    39.1 1306.66    58.7 1298.09    96.91279.251   117.4 1270.18
  147.33 1262.11   176.1 1250.76   185.9 1248.36   215.3 1243.94   264.2 1239.08
  297.81 1234.19   332.7 1226.37   420.8 1208.87   450.1 1202.05   469.7 1196.43
   479.5 1193.61   489.2 1192.16   508.8 1191.77   528.4 1191.94   538.2 1193.37
   547.5 1196.91  556.021201.609   606.7    1234   626.2 1243.32   665.4 1254.53
   694.7 1260.81   714.3 1262.54   743.7 1262.66   753.4 1264.34     773 1272.86
#Mann= 7 ,-1 , 0
       0     .12       0    96.9    .016       0  147.33     .06       0
  297.81     .12       0   469.7    .045       0   547.5     .04       0
  556.02     .12       0
Bank Sta=469.7,547.5
XS Rating Curve= 0 ,0
Exp/Cntr=0.3,0.1

Type RM Length L Ch R = 1 ,1705.9  ,613,603.9,594.5
XS GIS Cut Line= 3
     1845381.327      260541.275     1845717.264      261116.796
     1846061.014      261273.046
#Sta/Elev= 30
       0 1310.72    68.6 1282.93   94.341273.766   107.8 1269.48   127.4 1264.58
  135.721260.522   166.6 1239.68   186.2 1228.07   205.8 1218.67     245 1202.87
   264.6 1197.05   303.8 1188.58   352.8 1176.83   372.4 1175.56   411.6 1175.93
   450.8 1175.25   460.6 1175.59   471.91178.452   499.8 1194.06   529.2 1209.28
     539 1213.87   548.8 1217.32   666.4 1243.29   714.8 1252.76   782.6 1273.12
     860 1299.58   889.1 1307.51   995.6 1355.49  1024.6 1367.58    1044  1374.6
#Mann= 6 ,-1 , 0
       0     .12       0   94.34    .016       0  135.72     .12       0
   352.8    .045       0   411.6     .04       0   471.9     .12       0
Bank Sta=352.8,411.6
XS Rating Curve= 0 ,0
Exp/Cntr=0.3,0.1

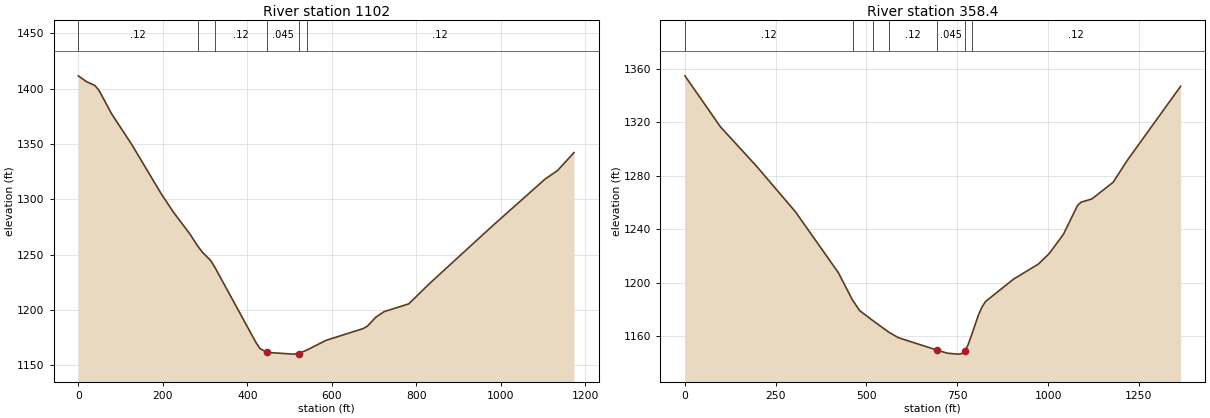
Type RM Length L Ch R = 1 ,1102    ,727.3,743.5,759.7
XS GIS Cut Line= 2
     1844758.931      260877.212     1845579.243      261715.754
#Sta/Elev= 30
       0 1411.49    19.6 1406.17    39.1 1402.79    48.9 1398.43    78.2 1377.53
   127.1 1349.05   195.5 1305.36   224.8 1288.45   263.9 1268.67  282.081257.964
   293.3 1252.26   312.8 1244.79  323.481238.311   420.4 1170.53   430.1 1165.02
     447 1161.61   508.3 1160.05   521.1 1160.53  540.221163.612   586.5 1172.54
   674.5  1183.2   684.3 1185.39   703.8 1193.36   723.4  1198.4     782 1205.46
   830.9 1223.72   977.6 1275.03  1104.6  1318.2    1134 1325.88  1173.1 1342.17
#Mann= 6 ,-1 , 0
       0     .12       0  282.08    .016       0  323.48     .12       0
     447    .045       0   521.1     .04       0  540.22     .12       0
Bank Sta=447,521.1
XS Rating Curve= 0 ,0
Exp/Cntr=0.3,0.1

Type RM Length L Ch R = 1 ,358.4   ,353.6,358.4,363.1
XS GIS Cut Line= 4
     1844639.139      261085.546     1844607.889      261624.608
     1844717.264        261931.9     1845071.431      262283.462
#Sta/Elev= 30
       0 1354.72    98.2  1316.4   196.4  1287.3   304.4 1252.91   422.2 1207.53
  461.561186.825   481.1 1178.98  516.721171.641  562.821162.562   587.9 1158.68
   693.5 1149.47   722.2  1147.1     751 1146.38   760.6 1146.56   770.2 1148.51
   779.8 1153.38  790.141161.215   808.6  1175.9   818.2 1181.68   827.8 1185.76
   905.3 1202.56   973.8 1213.88  1003.1 1221.61  1042.3 1236.03  1081.4 1257.76
  1091.2 1260.15  1120.6 1262.53  1179.3 1275.03  1218.4 1291.49  1365.2 1346.89
#Mann= 7 ,-1 , 0
       0     .12       0  461.56    .016       0  516.72     .06       0
  562.82     .12       0   693.5    .045       0   770.2     .04       0
  790.14     .12       0
Bank Sta=693.5,770.2
XS Rating Curve= 0 ,0
Exp/Cntr=0.3,0.1

Chan Stop Cuts=-1
Use User Specified Reach Order=0
Composite Channel Slope=5